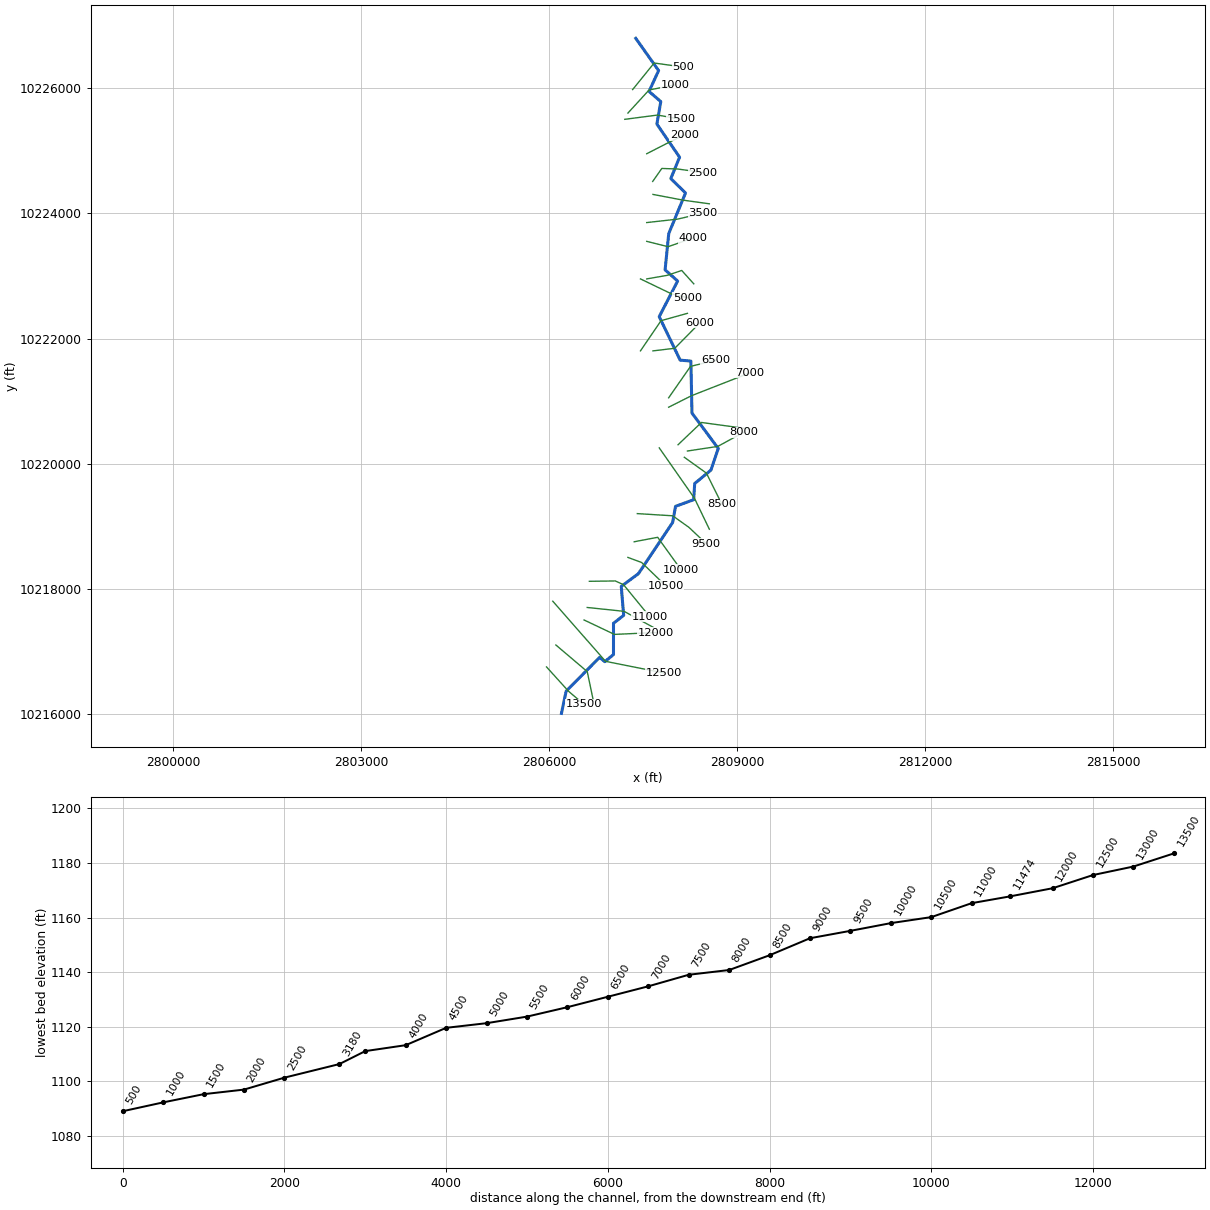
--- SANFERNANDO073.prj (project) ---

Proj Title=SANFERNANDO073 Base Level Engineering
Current Plan=p01
Default Exp/Contr=0.3,0.1
English Units
Geom File=g01
Flow File=f01
Plan File=p01
BEGIN DESCRIPTION:
SANFERNANDO073
END DESCRIPTION:

--- SANFERNANDO073.p01 (plan) ---

Plan Title=Multiple Run
Short Identifier=Multiple
Geom File=g01
Flow File=f01
Subcritical Flow
K Sum by GR= 0
Std Step Tol= 0.01
Critical Tol= 0.01
Num of Std Step Trials= 20
Max Error Tol= 0.3
Flow Tol Ratio= 0.001
Split Flow NTrial= 30
Split Flow Tol= 0.02
Split Flow Ratio= 0.02
Log Output Level= 0
Friction Slope Method= 1
Unsteady Friction Slope Method= 2
Unsteady Bridges Friction Slope Method= 1
Parabolic Critical Depth
Global Vel Dist=  1 , 1 , 1
Global Log Level= 0
CheckData=True
Encroach Param= -1, 0, 0, 0
BEGIN DESCRIPTION:
Multiple Run
END DESCRIPTION:

--- SANFERNANDO073.f01 (steady flow) ---

Flow Title=Multiple
Number of Profiles=7
Profile Names=10-year,25-year,50-year,1pct_min,100-year,1pct_plu,500-year
River Rch & RM= SANFERNANDO073,Reach-1,13500
     519     855    1863    1203    2663    5895    3933
River Rch & RM= SANFERNANDO073,Reach-1,3500
     638    1068    2190    1779    3133    5520    4600
Boundary for River Rch & Prof#=SANFERNANDO073,Reach-1,1
Up Type=0
Dn Type=3
Dn Slope=0.005
Boundary for River Rch & Prof#=SANFERNANDO073,Reach-1,2
Up Type=0
Dn Type=3
Dn Slope=0.005
Boundary for River Rch & Prof#=SANFERNANDO073,Reach-1,3
Up Type=0
Dn Type=3
Dn Slope=0.005
Boundary for River Rch & Prof#=SANFERNANDO073,Reach-1,4
Up Type=0
Dn Type=3
Dn Slope=0.005
Boundary for River Rch & Prof#=SANFERNANDO073,Reach-1,5
Up Type=0
Dn Type=3
Dn Slope=0.005
Boundary for River Rch & Prof#=SANFERNANDO073,Reach-1,6
Up Type=0
Dn Type=3
Dn Slope=0.005
Boundary for River Rch & Prof#=SANFERNANDO073,Reach-1,7
Up Type=0
Dn Type=3
Dn Slope=0.005

--- SANFERNANDO073.g01 (geometry) ---

Geom Title=Existing Conditions

River Reach=SANFERNANDO073,Reach-1
Reach XY= 30
      2806194.25     10216011.00      2806268.75     10216365.00
      2806803.25     10216906.00      2806886.50     10216837.00
      2807025.00     10216951.00      2807025.25     10217451.00
      2807187.50     10217577.00      2807149.00     10218040.00
      2807421.75     10218242.00      2807969.25     10219061.00
      2808015.50     10219319.00      2808305.25     10219425.00
      2808321.75     10219684.00      2808580.00     10219897.00
      2808698.00     10220244.00      2808278.25     10220809.00
      2808260.50     10221640.00      2808089.50     10221655.00
      2807755.25     10222350.00      2808049.00     10222919.00
      2807849.00     10223098.00      2807907.25     10223677.00
      2808175.00     10224326.00      2807940.50     10224557.00
      2808080.25     10224898.00      2807717.75     10225427.00
      2807780.25     10225786.00      2807592.25     10225949.00
      2807745.75     10226282.00      2807380.50     10226797.00

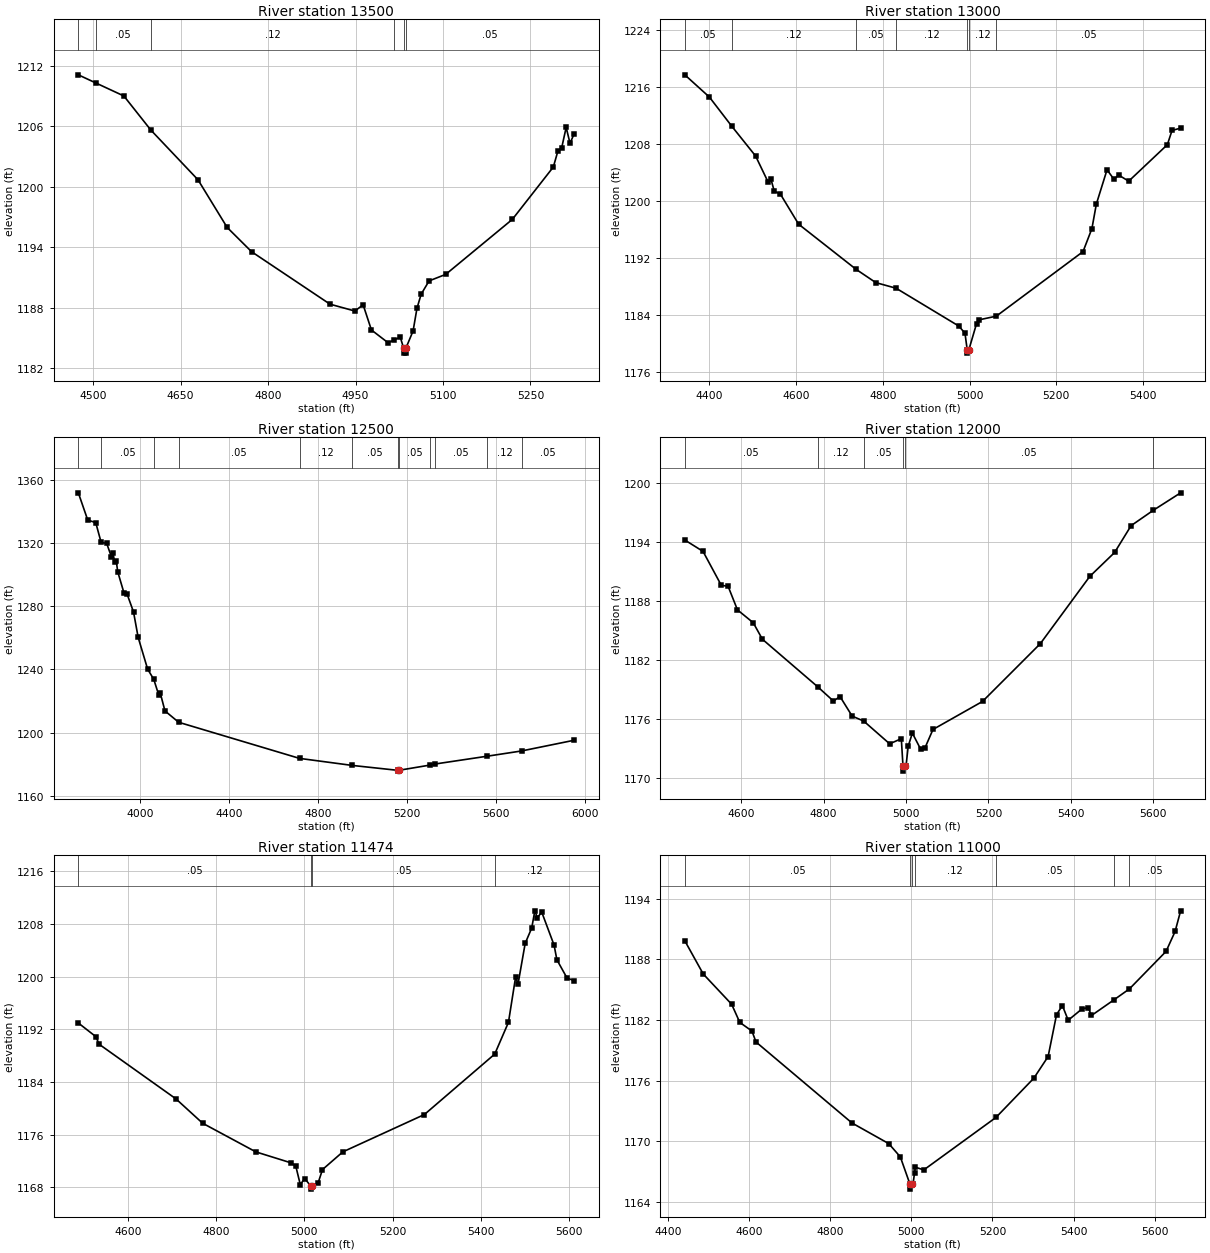
Type RM Length L Ch R = 1,13500,500,500,500
BEGIN DESCRIPTION:
SANFERNANDO073 27.0
END DESCRIPTION:
XS GIS Cut Line= 3
      2805955.66     10216753.14      2806308.07     10216363.45
      2806555.69     10216153.11
#Sta/Elev= 30
  4474.6 1211.13  4504.3 1210.33  4552.7 1209.03  4598.9 1205.65  4679.8 1200.71
  4729.8 1195.98  4771.7 1193.57  4906.2 1188.36  4948.8 1187.68  4963.0 1188.30
  4977.2 1185.80  5005.8 1184.53  5016.3 1184.81  5026.7 1185.09  5032.4 1184.00
  5032.7 1183.50  5036.2 1183.50  5036.4 1184.00  5048.7 1185.71  5055.3 1187.94
  5062.5 1189.35  5076.1 1190.67  5104.7 1191.32  5218.9 1196.78  5289.2 1201.98
  5296.9 1203.54  5303.5 1203.88  5311.2 1205.91  5317.8 1204.33  5324.9 1205.28
#Mann=6,-1,0
  4474.6    0.12       0  4504.3    0.05       0  4598.9    0.12       0
  5016.3    0.05       0  5032.4    0.07       0  5036.4    0.05       0
Bank Sta=5032.4,5036.4
Exp/Cntr=0.3,0.1

Type RM Length L Ch R = 1,13000,500,500,500
BEGIN DESCRIPTION:
SANFERNANDO073 26.0
END DESCRIPTION:
XS GIS Cut Line= 3
      2806105.68     10217103.11      2806605.85     10216678.96
      2806705.68     10216203.12
#Sta/Elev= 30
  4344.2 1217.76  4400.8 1214.64  4452.2 1210.56  4507.3 1206.36  4535.9 1202.73
  4542.5 1203.14  4550.2 1201.44  4564.5 1201.00  4606.4 1196.79  4738.8 1190.45
  4784.1 1188.59  4830.9 1187.80  4975.3 1182.49  4989.5 1181.49  4994.6 1179.19
  4994.9 1178.69  4998.6 1179.19  5016.2 1182.84  5022.4 1183.37  5061.7 1183.88
  5261.4 1192.94  5281.9 1196.18  5292.1 1199.62  5316.7 1204.43  5332.9 1203.07
  5343.2 1203.70  5366.6 1202.83  5455.6 1207.95  5466.4 1209.95  5486.2 1210.28
#Mann=7,-1,0
  4344.2    0.05       0  4452.2    0.12       0  4738.8    0.05       0
  4830.9    0.12       0  4994.6    0.07       0  4998.6    0.12       0
  5061.7    0.05       0
Bank Sta=4994.6,4998.6
Exp/Cntr=0.3,0.1

Type RM Length L Ch R = 1,12500,500,500,500
BEGIN DESCRIPTION:
SANFERNANDO073 25.0
END DESCRIPTION:
XS GIS Cut Line= 3
      2806055.71     10217803.09      2806898.36     10216842.24
      2807831.43     10216656.42
#Sta/Elev= 30
  3722.0 1351.59  3764.2 1334.39  3800.3 1332.72  3824.4 1320.30  3849.6 1319.56
  3870.5 1311.24  3878.1 1313.53  3884.7 1307.90  3892.3 1308.77  3899.0 1301.75
  3927.4 1288.19  3941.7 1287.36  3970.1 1276.28  3991.0 1260.17  4033.7 1240.03
  4061.1 1233.67  4083.1 1223.91  4090.6 1224.85  4111.5 1213.65  4173.1 1206.47
  4716.5 1183.63  4954.0 1179.17  5158.4 1176.07  5158.7 1175.57  5162.4 1176.07
  5303.8 1179.41  5325.9 1180.07  5561.0 1185.02  5714.7 1188.32  5951.4 1195.10
#Mann=12,-1,0
  3722.0    0.12       0  3824.4    0.05       0  4061.1    0.12       0
  4173.1    0.05       0  4716.5    0.12       0  4954.0    0.05       0
  5158.4    0.05       0  5162.4    0.05       0  5303.8    0.12       0
  5325.9    0.05       0  5561.0    0.12       0  5714.7    0.05       0
Bank Sta=5158.4,5162.4
Exp/Cntr=0.3,0.1

Type RM Length L Ch R = 1,12000,526,526,526
BEGIN DESCRIPTION:
SANFERNANDO073 24.0
END DESCRIPTION:
XS GIS Cut Line= 3
      2806555.72     10217503.09      2807040.34     10217272.92
      2807705.66     10217303.11
#Sta/Elev= 30
  4463.5 1194.25  4507.7 1193.09  4552.0 1189.64  4568.5 1189.54  4591.2 1187.14
  4629.5 1185.83  4651.7 1184.15  4785.9 1179.31  4824.0 1177.86  4839.9 1178.32
  4869.4 1176.33  4897.5 1175.82  4960.3 1173.51  4988.6 1174.03  4992.7 1171.23
  4992.9 1170.73  4996.7 1171.23  5000.0 1171.23  5005.3 1173.27  5015.4 1174.60
  5035.4 1172.97  5045.4 1173.04  5065.4 1174.97  5185.5 1177.82  5325.7 1183.70
  5445.8 1190.55  5505.9 1192.98  5545.9 1195.71  5600.0 1197.28  5666.0 1199.05
#Mann=6,-1,0
  4463.5    0.05       0  4785.9    0.12       0  4897.5    0.05       0
  4992.7    0.05       0  4996.7    0.05       0  5600.0    0.12       0
Bank Sta=4992.7,4996.7
Exp/Cntr=0.3,0.1

Type RM Length L Ch R = 1,11474,474,474,474
BEGIN DESCRIPTION:
SANFERNANDO073 23.0
END DESCRIPTION:
XS GIS Cut Line= 3
      2806605.73     10217703.11      2807194.56     10217641.49
      2807659.92     10217385.83
#Sta/Elev= 30
  4488.1 1192.96  4528.3 1190.86  4534.7 1189.76  4709.3 1181.44  4769.6 1177.75
  4890.2 1173.40  4970.7 1171.72  4980.7 1171.22  4990.8 1168.44  5000.8 1169.36
  5014.2 1168.25  5014.5 1167.75  5018.2 1168.25  5031.0 1168.65  5041.1 1170.72
  5087.1 1173.40  5271.9 1179.07  5431.2 1188.24  5462.3 1193.06  5478.4 1199.89
  5484.1 1198.91  5500.2 1205.05  5515.0 1207.37  5522.0 1209.98  5527.7 1208.96
  5537.8 1209.76  5565.6 1204.78  5572.0 1202.55  5594.9 1199.79  5611.1 1199.38
#Mann=4,-1,0
  4488.1    0.05       0  5014.2    0.03       0  5018.2    0.05       0
  5431.2    0.12       0
Bank Sta=5014.2,5018.2
Exp/Cntr=0.3,0.1

Type RM Length L Ch R = 1,11000,500,500,500
BEGIN DESCRIPTION:
SANFERNANDO073 22.0
END DESCRIPTION:
XS GIS Cut Line= 4
      2806640.19     10218121.18      2807053.82     10218126.93
      2807185.41     10218066.92      2807605.69     10217553.11
#Sta/Elev= 30
  4441.7 1189.83  4487.2 1186.54  4557.2 1183.55  4577.2 1181.76  4607.2 1180.90
  4617.2 1179.82  4853.8 1171.81  4944.4 1169.77  4972.9 1168.46  4996.6 1165.77
  4996.8 1165.27  5000.6 1165.77  5004.2 1165.77  5007.9 1166.85  5009.9 1167.44
  5030.8 1167.17  5208.7 1172.36  5302.0 1176.24  5337.2 1178.38  5358.0 1182.53
  5372.4 1183.42  5386.7 1181.97  5421.9 1183.13  5436.2 1183.20  5444.1 1182.44
  5498.5 1183.96  5537.6 1185.07  5627.9 1188.78  5650.2 1190.75  5663.8 1192.79
#Mann=7,-1,0
  4441.7    0.05       0  4996.6    0.05       0  5000.6    0.05       0
  5007.9    0.12       0  5208.7    0.05       0  5498.5    0.12       0
  5537.6    0.05       0
Bank Sta=4996.6,5000.6
Exp/Cntr=0.3,0.1

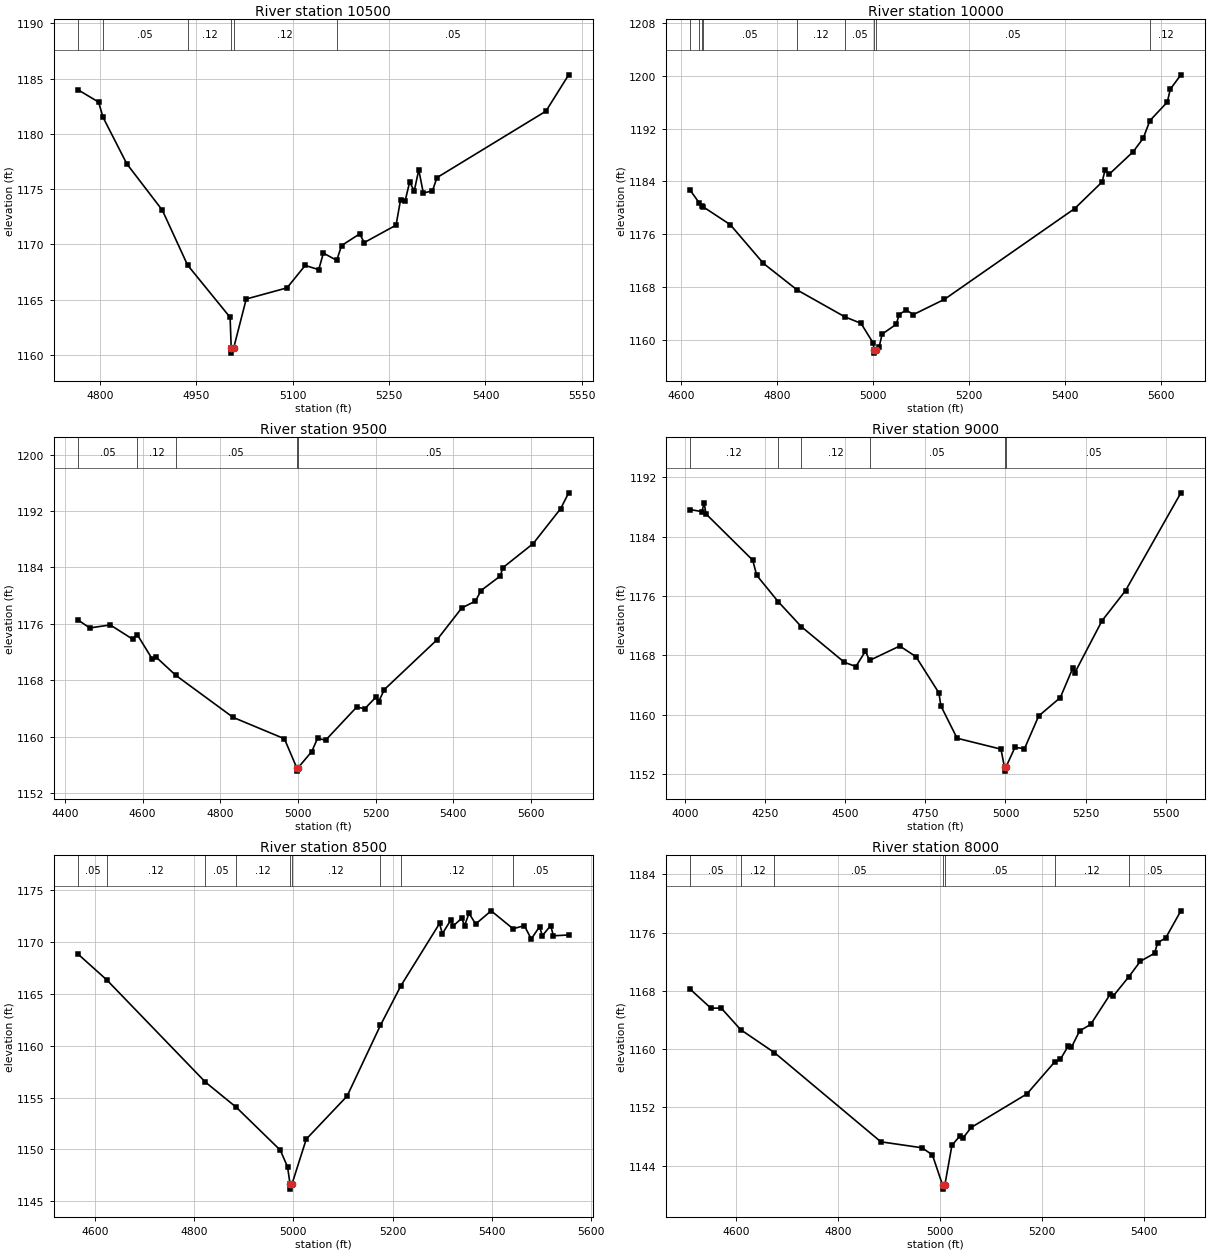
Type RM Length L Ch R = 1,10500,500,500,500
BEGIN DESCRIPTION:
SANFERNANDO073 21.0
END DESCRIPTION:
XS GIS Cut Line= 3
      2807255.66     10218503.12      2807475.25     10218421.40
      2807855.69     10218053.11
#Sta/Elev= 30
  4765.7 1183.99  4797.7 1182.88  4804.5 1181.51  4841.6 1177.29  4896.9 1173.09
  4936.2 1168.12  5002.4 1163.39  5004.1 1160.65  5004.4 1160.15  5008.1 1160.65
  5027.5 1165.05  5091.0 1166.06  5119.3 1168.09  5140.4 1167.71  5147.6 1169.21
  5168.4 1168.55  5175.9 1169.89  5204.2 1170.95  5211.2 1170.16  5260.8 1171.74
  5267.8 1174.05  5275.0 1173.96  5281.9 1175.64  5289.1 1174.84  5296.1 1176.75
  5303.2 1174.65  5317.4 1174.84  5324.4 1176.04  5494.1 1182.06  5529.5 1185.35
#Mann=6,-1,0
  4765.7    0.12       0  4804.5    0.05       0  4936.2    0.12       0
  5004.1    0.07       0  5008.1    0.12       0  5168.4    0.05       0
Bank Sta=5004.1,5008.1
Exp/Cntr=0.3,0.1

Type RM Length L Ch R = 1,10000,500,500,500
BEGIN DESCRIPTION:
SANFERNANDO073 20.0
END DESCRIPTION:
XS GIS Cut Line= 3
      2807355.66     10218753.11      2807730.31     10218824.51
      2808105.71     10218303.08
#Sta/Elev= 30
  4618.6 1182.64  4636.7 1180.80  4642.7 1180.31  4644.9 1180.17  4702.0 1177.44
  4771.3 1171.56  4841.9 1167.52  4941.6 1163.44  4974.9 1162.47  5000.0 1159.51
  5002.3 1158.45  5002.5 1157.95  5006.3 1158.45  5012.8 1158.89  5019.0 1160.84
  5048.4 1162.32  5054.6 1163.81  5069.3 1164.51  5084.0 1163.79  5149.0 1166.11
  5420.7 1179.87  5478.0 1183.91  5484.2 1185.69  5492.7 1185.08  5543.0 1188.51
  5563.9 1190.55  5577.8 1193.22  5614.2 1196.04  5620.4 1197.99  5642.5 1200.17
#Mann=9,-1,0
  4618.6    0.12       0  4636.7    0.05       0  4642.7    0.12       0
  4644.9    0.05       0  4841.9    0.12       0  4941.6    0.05       0
  5002.3    0.03       0  5006.3    0.05       0  5577.8    0.12       0
Bank Sta=5002.3,5006.3
Exp/Cntr=0.3,0.1

Type RM Length L Ch R = 1,9500,500,500,500
BEGIN DESCRIPTION:
SANFERNANDO073 19.0
END DESCRIPTION:
XS GIS Cut Line= 4
      2807405.66     10219203.11      2807970.47     10219167.95
      2808228.91     10218983.78      2808504.99     10218723.33
#Sta/Elev= 30
  4434.1 1176.55  4464.2 1175.42  4516.9 1175.85  4574.4 1173.84  4586.5 1174.47
  4624.5 1171.06  4634.5 1171.31  4685.7 1168.70  4833.2 1162.74  4965.2 1159.71
  4996.7 1155.62  4997.0 1155.12  5000.7 1155.62  5035.6 1157.89  5050.4 1159.77
  5071.3 1159.51  5151.2 1164.20  5172.1 1163.97  5201.6 1165.66  5207.8 1164.98
  5222.5 1166.69  5357.9 1173.74  5421.8 1178.26  5457.0 1179.23  5471.2 1180.72
  5520.5 1182.77  5527.8 1183.98  5605.5 1187.38  5676.3 1192.34  5696.9 1194.58
#Mann=5,-1,0
  4434.1    0.05       0  4586.5    0.12       0  4685.7    0.05       0
  4996.7    0.05       0  5000.7    0.05       0
Bank Sta=4996.7,5000.7
Exp/Cntr=0.3,0.1

Type RM Length L Ch R = 1,9000,500,500,500
BEGIN DESCRIPTION:
SANFERNANDO073 18.0
END DESCRIPTION:
XS GIS Cut Line= 3
      2807755.71     10220253.07      2808318.68     10219446.64
      2808555.69     10218953.10
#Sta/Elev= 30
  4016.5 1187.63  4053.0 1187.36  4059.6 1188.53  4065.7 1187.04  4211.4 1180.82
  4223.8 1178.78  4290.5 1175.25  4362.7 1171.88  4497.5 1167.06  4533.3 1166.50
  4563.0 1168.56  4576.0 1167.32  4670.2 1169.26  4720.8 1167.82  4792.4 1162.94
  4798.5 1161.20  4849.1 1156.84  4986.0 1155.37  4997.1 1152.91  4997.4 1152.41
  5001.1 1152.91  5029.7 1155.61  5059.4 1155.43  5103.8 1159.84  5171.1 1162.31
  5210.8 1166.34  5216.4 1165.65  5301.4 1172.66  5374.9 1176.73  5547.5 1189.89
#Mann=6,-1,0
  4016.5    0.12       0  4290.5    0.05       0  4362.7    0.12       0
  4576.0    0.05       0  4997.1    0.05       0  5001.1    0.05       0
Bank Sta=4997.1,5001.1
Exp/Cntr=0.3,0.1

Type RM Length L Ch R = 1,8500,500,500,500
BEGIN DESCRIPTION:
SANFERNANDO073 17.0
END DESCRIPTION:
XS GIS Cut Line= 3
      2808155.72     10220103.09      2808508.37     10219850.12
      2808755.66     10219353.15
#Sta/Elev= 30
  4566.0 1168.85  4623.5 1166.38  4822.7 1156.50  4885.4 1154.05  4973.7 1149.93
  4988.4 1148.31  4993.3 1146.67  4993.5 1146.17  4997.3 1146.67  5026.1 1151.00
  5108.4 1155.15  5175.5 1161.97  5217.0 1165.81  5294.8 1171.81  5300.4 1170.82
  5317.2 1172.12  5322.8 1171.59  5339.6 1172.32  5345.2 1171.59  5354.1 1172.79
  5367.6 1171.76  5398.8 1173.03  5443.0 1171.30  5465.8 1171.60  5479.6 1170.31
  5496.4 1171.50  5502.0 1170.62  5518.8 1171.61  5524.3 1170.62  5555.1 1170.70
#Mann=9,-1,0
  4566.0    0.05       0  4623.5    0.12       0  4822.7    0.05       0
  4885.4    0.12       0  4993.3    0.07       0  4997.3    0.12       0
  5175.5    0.05       0  5217.0    0.12       0  5443.0    0.05       0
Bank Sta=4993.3,4997.3
Exp/Cntr=0.3,0.1

Type RM Length L Ch R = 1,8000,500,500,500
BEGIN DESCRIPTION:
SANFERNANDO073 16.0
END DESCRIPTION:
XS GIS Cut Line= 3
      2808205.69     10220203.11      2808690.61     10220276.83
      2809105.65     10220503.09
#Sta/Elev= 30
  4509.5 1168.22  4550.0 1165.62  4570.2 1165.64  4608.4 1162.67  4674.8 1159.51
  4883.7 1147.26  4964.7 1146.44  4984.9 1145.45  5005.1 1141.26  5005.3 1140.76
  5009.1 1141.26  5023.2 1146.78  5039.4 1148.11  5045.0 1147.80  5061.2 1149.24
  5170.4 1153.84  5225.5 1158.28  5235.9 1158.58  5252.0 1160.47  5257.7 1160.23
  5273.8 1162.49  5295.7 1163.40  5333.7 1167.51  5339.4 1167.25  5370.7 1169.96
  5393.0 1172.06  5421.0 1173.17  5427.2 1174.63  5442.8 1175.26  5472.7 1179.00
#Mann=7,-1,0
  4509.5    0.05       0  4608.4    0.12       0  4674.8    0.05       0
  5005.1    0.05       0  5009.1    0.05       0  5225.5    0.12       0
  5370.7    0.05       0
Bank Sta=5005.1,5009.1
Exp/Cntr=0.3,0.1

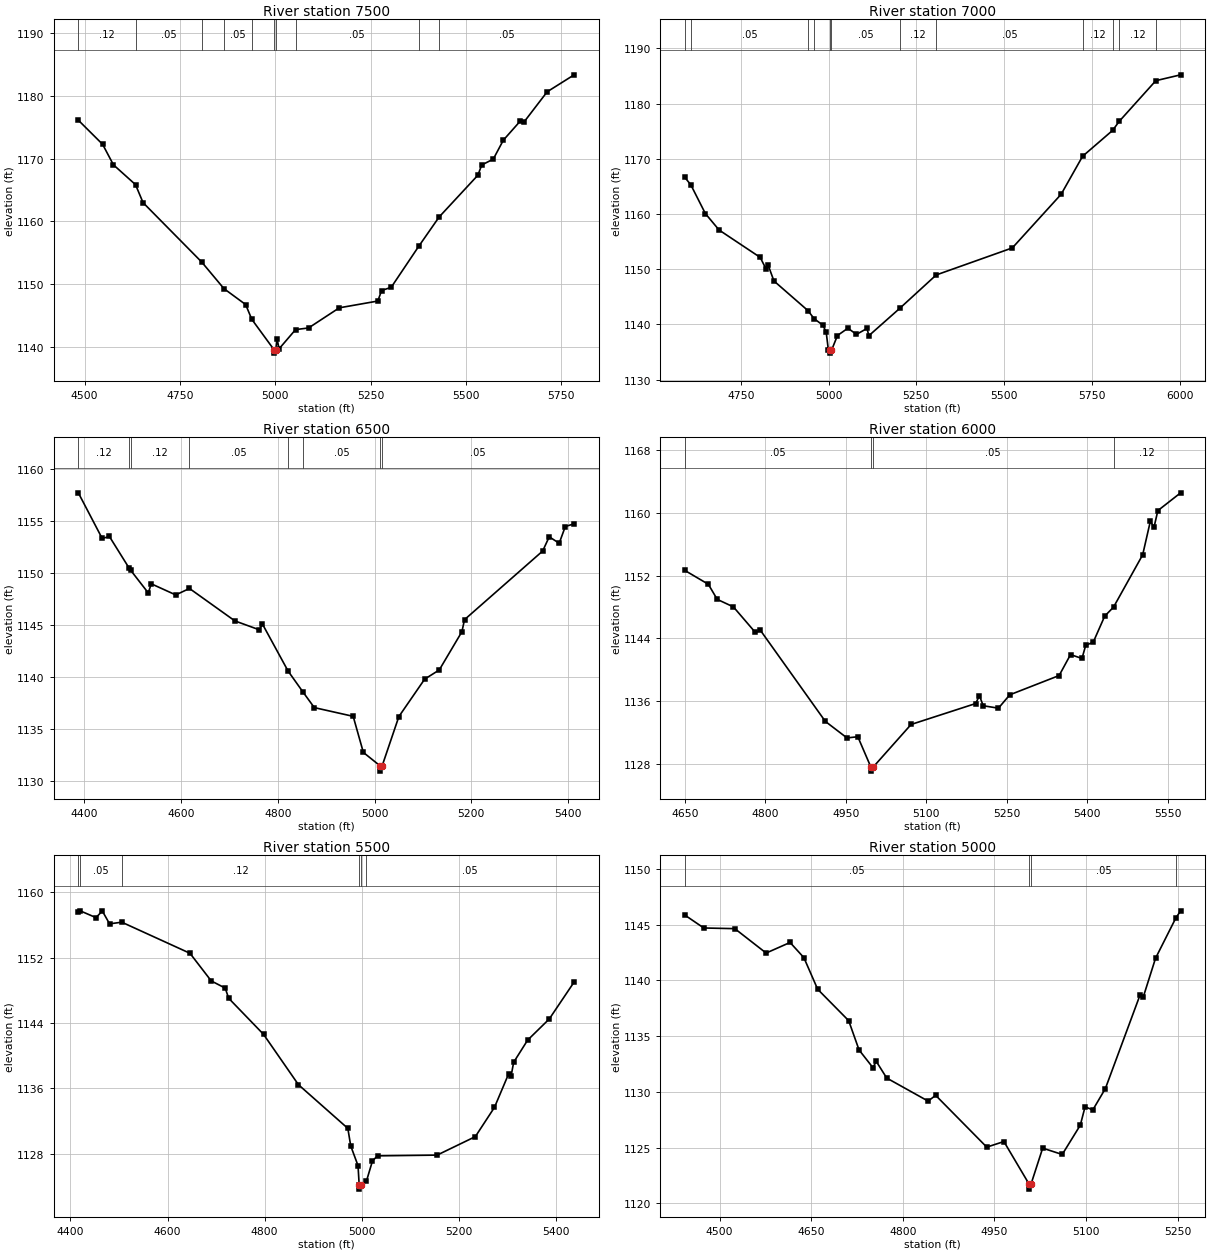
Type RM Length L Ch R = 1,7500,500,500,500
BEGIN DESCRIPTION:
SANFERNANDO073 15.0
END DESCRIPTION:
XS GIS Cut Line= 3
      2808055.67     10220303.10      2808429.44     10220659.28
      2809205.72     10220553.11
#Sta/Elev= 30
  4483.7 1176.14  4547.4 1172.29  4575.7 1169.03  4633.6 1165.87  4653.4 1163.00
  4807.5 1153.51  4865.4 1149.30  4922.3 1146.76  4938.5 1144.40  4997.2 1139.52
  4997.4 1139.02  5001.2 1139.52  5004.9 1141.21  5010.0 1139.71  5053.2 1142.77
  5087.2 1143.03  5167.8 1146.24  5268.7 1147.32  5278.8 1149.00  5303.9 1149.51
  5375.8 1156.02  5429.6 1160.72  5531.1 1167.37  5541.2 1169.00  5571.5 1169.94
  5597.9 1172.96  5642.2 1176.00  5652.3 1175.87  5712.8 1180.67  5783.5 1183.37
#Mann=10,-1,0
  4483.7    0.12       0  4633.6    0.05       0  4807.5    0.12       0
  4865.4    0.05       0  4938.5    0.12       0  4997.2    0.07       0
  5001.2    0.12       0  5053.2    0.05       0  5375.8    0.12       0
  5429.6    0.05       0
Bank Sta=4997.2,5001.2
Exp/Cntr=0.3,0.1

Type RM Length L Ch R = 1,7000,500,500,500
BEGIN DESCRIPTION:
SANFERNANDO073 14.0
END DESCRIPTION:
XS GIS Cut Line= 3
      2807905.66     10220903.10      2808271.83     10221087.09
      2809205.66     10221453.10
#Sta/Elev= 30
  4590.2 1166.63  4607.4 1165.27  4648.8 1160.07  4687.9 1157.09  4805.1 1152.13
  4821.9 1150.00  4827.5 1150.76  4844.2 1147.86  4941.3 1142.48  4958.5 1141.04
  4983.8 1139.84  4993.1 1138.58  4999.4 1135.31  5004.2 1135.29  5004.4 1134.79
  5008.2 1135.29  5025.2 1137.98  5055.0 1139.31  5079.3 1138.18  5109.3 1139.26
  5114.7 1137.95  5202.3 1142.88  5306.6 1148.95  5523.5 1153.85  5662.6 1163.57
  5723.7 1170.45  5809.1 1175.13  5828.0 1176.77  5932.3 1184.14  6003.0 1185.20
#Mann=12,-1,0
  4590.2    0.12       0  4607.4    0.05       0  4941.3    0.12       0
  4958.5    0.05       0  5004.2    0.05       0  5008.2    0.05       0
  5202.3    0.12       0  5306.6    0.05       0  5723.7    0.12       0
  5809.1    0.05       0  5828.0    0.12       0  5932.3    0.05       0
Bank Sta=5004.2,5008.2
Exp/Cntr=0.3,0.1

Type RM Length L Ch R = 1,6500,500,500,500
BEGIN DESCRIPTION:
SANFERNANDO073 13.0
END DESCRIPTION:
XS GIS Cut Line= 3
      2807905.66     10221053.08      2808255.06     10221555.41
      2808655.72     10221653.12
#Sta/Elev= 30
  4388.1 1157.73  4437.4 1153.34  4452.3 1153.53  4493.4 1150.46  4495.9 1150.30
  4532.6 1148.10  4538.7 1148.98  4589.3 1147.91  4617.7 1148.53  4711.5 1145.41
  4762.2 1144.55  4768.3 1145.12  4821.5 1140.58  4852.8 1138.53  4875.6 1137.07
  4955.9 1136.23  4976.9 1132.76  5011.7 1131.46  5012.0 1130.96  5015.7 1131.46
  5050.3 1136.21  5103.6 1139.81  5133.7 1140.69  5180.5 1144.37  5185.9 1145.53
  5347.3 1152.13  5360.9 1153.50  5381.5 1152.88  5394.1 1154.49  5412.4 1154.75
#Mann=8,-1,0
  4388.1    0.12       0  4493.4    0.05       0  4495.9    0.12       0
  4617.7    0.05       0  4821.5    0.12       0  4852.8    0.05       0
  5011.7    0.05       0  5015.7    0.05       0
Bank Sta=5011.7,5015.7
Exp/Cntr=0.3,0.1

Type RM Length L Ch R = 1,6000,500,500,500
BEGIN DESCRIPTION:
SANFERNANDO073 12.0
END DESCRIPTION:
XS GIS Cut Line= 3
      2807655.68     10221803.11      2808003.23     10221844.43
      2808405.70     10222253.13
#Sta/Elev= 30
  4650.0 1152.65  4693.8 1150.89  4710.4 1148.97  4740.6 1148.01  4781.5 1144.76
  4791.0 1145.02  4911.8 1133.46  4952.1 1131.36  4972.3 1131.51  4996.7 1127.64
  4997.0 1127.14  5000.7 1127.64  5071.5 1133.07  5191.8 1135.73  5198.8 1136.73
  5205.9 1135.45  5234.2 1135.14  5255.4 1136.84  5347.3 1139.29  5368.5 1141.95
  5389.8 1141.46  5396.8 1143.12  5410.9 1143.54  5432.2 1146.84  5448.6 1147.98
  5502.9 1154.63  5517.1 1158.87  5524.1 1158.16  5531.2 1160.25  5573.6 1162.51
#Mann=4,-1,0
  4650.0    0.05       0  4996.7    0.05       0  5000.7    0.05       0
  5448.6    0.12       0
Bank Sta=4996.7,5000.7
Exp/Cntr=0.3,0.1

Type RM Length L Ch R = 1,5500,500,500,500
BEGIN DESCRIPTION:
SANFERNANDO073 11.0
END DESCRIPTION:
XS GIS Cut Line= 3
      2807455.70     10221803.14      2807784.37     10222285.51
      2808205.66     10222403.11
#Sta/Elev= 30
  4416.3 1157.60  4420.1 1157.71  4452.6 1156.88  4465.7 1157.69  4480.6 1156.12
  4505.8 1156.32  4646.2 1152.52  4690.0 1149.14  4718.8 1148.26  4725.9 1147.02
  4797.8 1142.60  4869.6 1136.45  4971.3 1131.11  4977.3 1128.96  4992.3 1126.55
  4994.7 1124.18  4995.0 1123.68  4998.7 1124.18  5009.5 1124.63  5022.1 1127.14
  5032.5 1127.75  5155.2 1127.84  5233.9 1130.10  5273.3 1133.68  5302.2 1137.74
  5307.4 1137.47  5312.8 1139.19  5341.6 1141.90  5386.2 1144.49  5437.4 1149.01
#Mann=6,-1,0
  4416.3    0.12       0  4420.1    0.05       0  4505.8    0.12       0
  4994.7    0.07       0  4998.7    0.12       0  5009.5    0.05       0
Bank Sta=4994.7,4998.7
Exp/Cntr=0.3,0.1

Type RM Length L Ch R = 1,5000,500,500,500
BEGIN DESCRIPTION:
SANFERNANDO073 10.0
END DESCRIPTION:
XS GIS Cut Line= 3
      2807455.68     10222953.11      2807957.37     10222711.13
      2808205.68     10222653.11
#Sta/Elev= 30
  4443.0 1145.87  4474.1 1144.71  4524.9 1144.65  4576.2 1142.46  4615.4 1143.41
  4638.0 1142.05  4660.6 1139.21  4711.4 1136.39  4728.4 1133.76  4751.0 1132.18
  4756.6 1132.73  4773.7 1131.24  4841.5 1129.17  4853.8 1129.69  4937.5 1125.04
  4965.6 1125.54  5006.3 1121.77  5006.6 1121.27  5010.3 1121.77  5029.1 1124.95
  5061.1 1124.38  5090.7 1127.01  5098.5 1128.66  5111.2 1128.38  5131.8 1130.30
  5188.7 1138.72  5193.8 1138.51  5213.9 1141.99  5247.1 1145.60  5255.0 1146.25
#Mann=4,-1,0
  4443.0    0.05       0  5006.3    0.05       0  5010.3    0.05       0
  5247.1    0.12       0
Bank Sta=5006.3,5010.3
Exp/Cntr=0.3,0.1

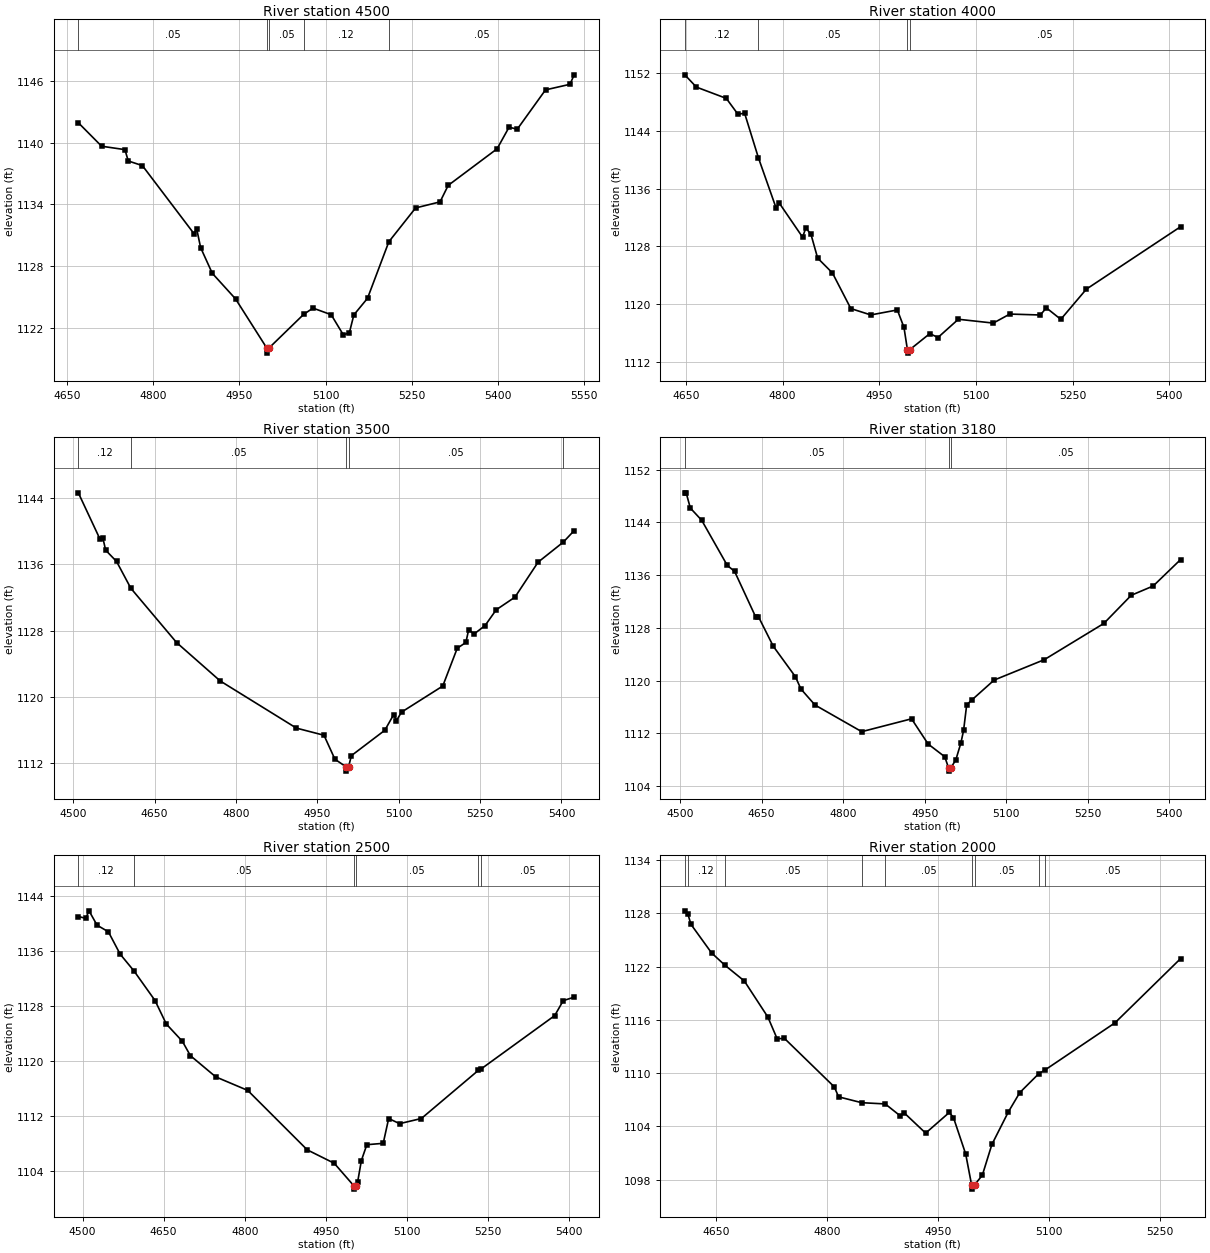
Type RM Length L Ch R = 1,4500,500,500,500
BEGIN DESCRIPTION:
SANFERNANDO073 9.0
END DESCRIPTION:
XS GIS Cut Line= 4
      2807555.69     10222953.11      2807881.62     10223009.70
      2808114.33     10223087.94      2808307.07     10222874.37
#Sta/Elev= 30
  4669.2 1141.93  4709.8 1139.65  4750.4 1139.32  4756.2 1138.22  4780.8 1137.77
  4870.5 1131.18  4875.5 1131.61  4882.3 1129.81  4902.6 1127.32  4943.2 1124.83
  4997.5 1120.07  4997.8 1119.57  5001.5 1120.07  5061.8 1123.33  5078.1 1123.94
  5109.8 1123.30  5130.9 1121.35  5141.4 1121.53  5149.3 1123.28  5173.1 1124.89
  5210.3 1130.38  5256.9 1133.66  5299.5 1134.25  5313.7 1135.85  5398.9 1139.40
  5419.8 1141.50  5434.0 1141.30  5483.3 1145.12  5525.9 1145.66  5533.2 1146.58
#Mann=5,-1,0
  4669.2    0.05       0  4997.5    0.05       0  5001.5    0.05       0
  5061.8    0.12       0  5210.3    0.05       0
Bank Sta=4997.5,5001.5
Exp/Cntr=0.3,0.1

Type RM Length L Ch R = 1,4000,500,500,500
BEGIN DESCRIPTION:
SANFERNANDO073 8.0
END DESCRIPTION:
XS GIS Cut Line= 3
      2807555.69     10223553.11      2807897.03     10223467.57
      2808291.28     10223605.57
#Sta/Elev= 30
  4648.1 1151.75  4666.1 1150.05  4712.5 1148.49  4730.6 1146.29  4740.9 1146.44
  4762.4 1140.25  4789.7 1133.34  4794.8 1133.98  4830.9 1129.27  4836.0 1130.55
  4844.0 1129.64  4854.3 1126.37  4877.2 1124.32  4905.8 1119.38  4936.8 1118.50
  4978.0 1119.19  4988.3 1116.77  4993.6 1113.71  4993.9 1113.21  4997.6 1113.71
  5028.5 1115.92  5041.0 1115.37  5072.7 1117.90  5126.9 1117.37  5152.6 1118.62
  5199.9 1118.49  5209.3 1119.48  5231.7 1117.89  5271.4 1122.07  5417.7 1130.72
#Mann=4,-1,0
  4648.1    0.12       0  4762.4    0.05       0  4993.6    0.05       0
  4997.6    0.05       0
Bank Sta=4993.6,4997.6
Exp/Cntr=0.3,0.1

Type RM Length L Ch R = 1,3500,320,320,320
BEGIN DESCRIPTION:
SANFERNANDO073 7.0
END DESCRIPTION:
XS GIS Cut Line= 3
      2807555.71     10223853.11      2808043.20     10223907.39
      2808455.64     10224003.10
#Sta/Elev= 30
  4509.5 1144.63  4549.7 1139.00  4554.7 1139.19  4559.8 1137.71  4579.9 1136.35
  4606.3 1133.11  4690.6 1126.56  4771.1 1121.92  4911.5 1116.23  4962.3 1115.37
  4982.4 1112.48  5003.4 1111.54  5003.6 1111.04  5007.5 1111.54  5012.8 1112.91
  5074.4 1115.97  5090.7 1117.86  5095.9 1117.14  5105.2 1118.16  5181.2 1121.31
  5207.9 1125.87  5223.8 1126.57  5229.0 1128.12  5238.7 1127.58  5259.2 1128.61
  5279.7 1130.51  5314.3 1132.04  5356.9 1136.26  5403.4 1138.68  5423.4 1140.07
#Mann=5,-1,0
  4509.5    0.12       0  4606.3    0.05       0  5003.4    0.03       0
  5007.5    0.05       0  5403.4    0.12       0
Bank Sta=5003.4,5007.5
Exp/Cntr=0.3,0.1

Type RM Length L Ch R = 1,3180,680,680,680
BEGIN DESCRIPTION:
SANFERNANDO073 6.0
END DESCRIPTION:
XS GIS Cut Line= 3
      2807655.71     10224303.11      2808138.50     10224211.00
      2808555.70     10224153.11
#Sta/Elev= 30
  4508.5 1148.47  4511.0 1148.47  4518.7 1146.16  4539.6 1144.31  4586.7 1137.47
  4600.1 1136.57  4638.8 1129.69  4643.9 1129.72  4671.4 1125.21  4712.1 1120.60
  4722.3 1118.73  4748.2 1116.31  4834.2 1112.27  4925.9 1114.22  4956.4 1110.40
  4987.0 1108.47  4994.0 1106.79  4994.2 1106.29  4998.1 1106.79  5007.3 1107.97
  5016.7 1110.55  5021.7 1112.47  5027.4 1116.35  5037.5 1117.12  5077.9 1120.09
  5170.2 1123.18  5279.8 1128.67  5330.3 1132.94  5370.7 1134.35  5421.2 1138.36
#Mann=3,-1,0
  4508.5    0.05       0  4994.0    0.05       0  4998.1    0.05       0
Bank Sta=4994,4998.1
Exp/Cntr=0.3,0.1

Type RM Length L Ch R = 1,2500,500,500,500
BEGIN DESCRIPTION:
SANFERNANDO073 5.0
END DESCRIPTION:
XS GIS Cut Line= 4
      2807650.77     10224509.80      2807796.62     10224718.15
      2808049.93     10224709.08      2808455.69     10224653.11
#Sta/Elev= 30
  4492.2 1141.07  4505.9 1140.81  4512.0 1141.90  4526.8 1139.81  4547.8 1138.84
  4569.5 1135.59  4595.3 1133.12  4634.1 1128.82  4655.0 1125.39  4684.7 1122.87
  4699.5 1120.78  4746.5 1117.68  4805.6 1115.71  4915.7 1107.04  4965.7 1105.08
  5001.8 1101.81  5002.1 1101.31  5006.0 1101.81  5009.0 1102.36  5015.9 1105.48
  5026.0 1107.79  5056.3 1107.99  5066.4 1111.61  5086.6 1110.86  5126.9 1111.61
  5232.3 1118.63  5238.0 1118.87  5373.6 1126.62  5389.4 1128.80  5409.6 1129.31
#Mann=6,-1,0
  4492.2    0.12       0  4595.3    0.05       0  5001.8    0.05       0
  5006.0    0.05       0  5232.3    0.12       0  5238.0    0.05       0
Bank Sta=5001.8,5006
Exp/Cntr=0.3,0.1

Type RM Length L Ch R = 1,2000,500,500,500
BEGIN DESCRIPTION:
SANFERNANDO073 4.0
END DESCRIPTION:
XS GIS Cut Line= 3
      2807555.64     10224953.09      2807904.93     10225132.14
      2808155.67     10225253.11
#Sta/Elev= 30
  4607.5 1128.29  4611.7 1127.92  4615.8 1126.77  4643.7 1123.55  4661.5 1122.18
  4688.0 1120.39  4719.9 1116.32  4732.4 1113.88  4742.4 1113.91  4809.8 1108.45
  4815.6 1107.33  4846.8 1106.67  4878.7 1106.53  4898.8 1105.20  4904.4 1105.52
  4933.4 1103.24  4965.4 1105.57  4971.0 1105.00  4987.6 1100.88  4995.5 1097.43
  4995.7 1096.93  4999.8 1097.43  5010.1 1098.50  5023.0 1101.96  5045.3 1105.63
  5060.8 1107.81  5086.5 1109.94  5094.8 1110.35  5189.6 1115.67  5278.4 1122.91
#Mann=9,-1,0
  4607.5    0.05       0  4611.7    0.12       0  4661.5    0.05       0
  4846.8    0.12       0  4878.7    0.05       0  4995.5    0.05       0
  4999.8    0.05       0  5086.5    0.12       0  5094.8    0.05       0
Bank Sta=4995.5,4999.8
Exp/Cntr=0.3,0.1

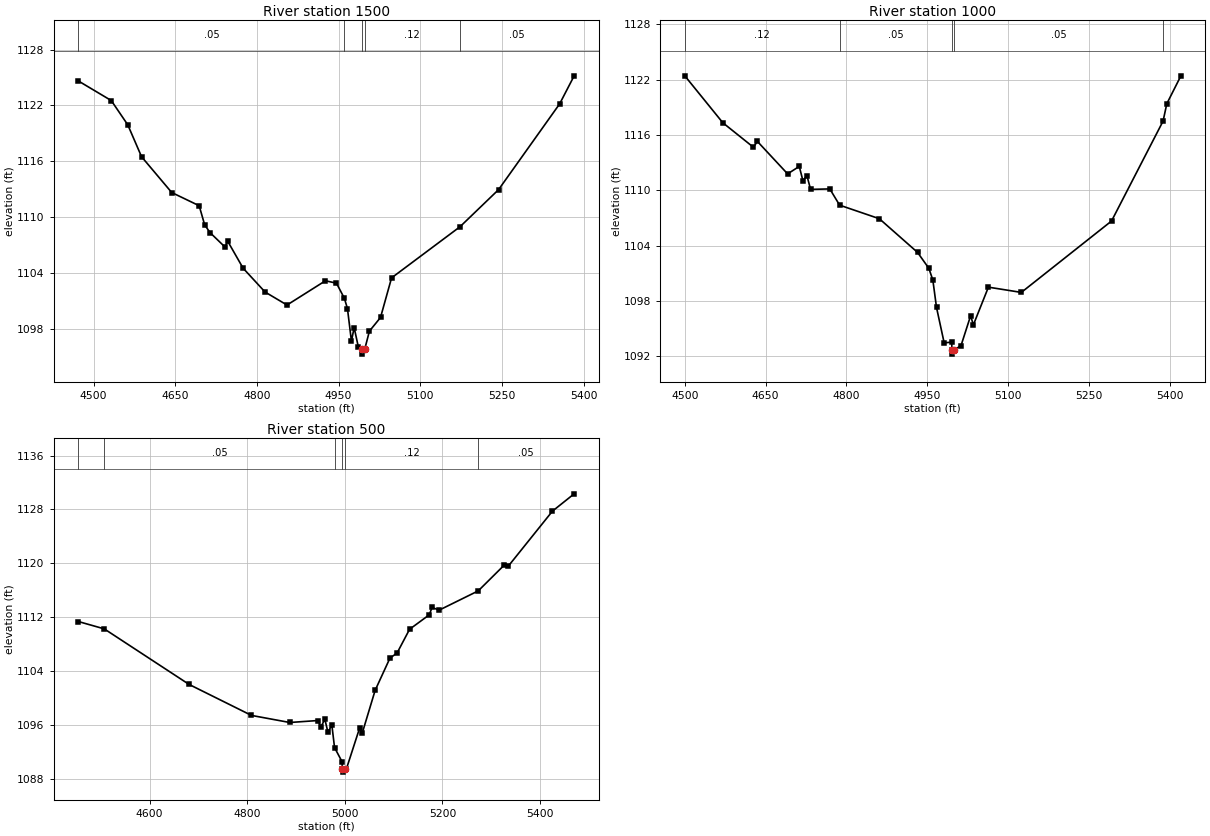
Type RM Length L Ch R = 1,1500,500,500,500
BEGIN DESCRIPTION:
SANFERNANDO073 3.0
END DESCRIPTION:
XS GIS Cut Line= 3
      2807205.66     10225503.11      2807729.15     10225571.23
      2808105.64     10225503.12
#Sta/Elev= 30
  4472.1 1124.63  4532.6 1122.52  4562.9 1119.91  4588.2 1116.48  4643.6 1112.63
  4694.0 1111.21  4704.1 1109.15  4714.1 1108.31  4741.4 1106.77  4746.4 1107.39
  4774.7 1104.49  4815.0 1101.93  4855.3 1100.53  4925.9 1103.14  4946.1 1102.88
  4960.6 1101.26  4966.3 1100.15  4973.6 1096.65  4978.6 1098.11  4986.4 1095.99
  4993.5 1095.75  4993.8 1095.25  4997.9 1095.75  5006.6 1097.72  5027.0 1099.19
  5047.3 1103.45  5173.0 1108.95  5243.8 1112.94  5355.9 1122.16  5382.6 1125.18
#Mann=5,-1,0
  4472.1    0.05       0  4960.6    0.12       0  4993.5    0.07       0
  4997.9    0.12       0  5173.0    0.05       0
Bank Sta=4993.5,4997.9
Exp/Cntr=0.3,0.1

Type RM Length L Ch R = 1,1000,500,500,500
BEGIN DESCRIPTION:
SANFERNANDO073 2.0
END DESCRIPTION:
XS GIS Cut Line= 3
      2807255.71     10225603.14      2807593.34     10225971.65
      2808005.67     10226053.11
#Sta/Elev= 30
  4500.2 1122.41  4570.8 1117.32  4627.5 1114.67  4634.9 1115.30  4691.0 1111.78
  4712.6 1112.59  4719.4 1111.04  4726.8 1111.60  4733.6 1110.10  4769.3 1110.15
  4787.5 1108.39  4861.2 1106.92  4932.1 1103.27  4953.1 1101.54  4960.5 1100.27
  4967.3 1097.30  4981.5 1093.46  4995.6 1093.54  4995.8 1092.74  4996.1 1092.24
  5000.2 1092.74  5012.6 1093.13  5030.6 1096.40  5035.7 1095.41  5063.6 1099.50
  5124.7 1098.93  5292.1 1106.67  5387.7 1117.50  5394.7 1119.39  5420.3 1122.35
#Mann=5,-1,0
  4500.2    0.12       0  4787.5    0.05       0  4995.8    0.05       0
  5000.2    0.05       0  5387.7    0.12       0
Bank Sta=4995.8,5000.2
Exp/Cntr=0.3,0.1

Type RM Length L Ch R = 1,500,0,0,0
BEGIN DESCRIPTION:
SANFERNANDO073 1.0
END DESCRIPTION:
XS GIS Cut Line= 3
      2807330.72     10225978.15      2807674.20     10226402.83
      2808139.72     10226338.03
#Sta/Elev= 30
  4453.8 1111.36  4506.9 1110.27  4680.8 1102.02  4808.7 1097.42  4887.1 1096.37
  4944.6 1096.66  4951.0 1095.70  4959.0 1096.86  4965.4 1094.91  4973.4 1096.00
  4978.9 1092.65  4994.2 1090.56  4995.0 1089.50  4995.3 1089.00  4999.5 1089.50
  5003.3 1089.50  5030.5 1095.59  5035.5 1094.75  5062.1 1101.14  5092.4 1105.92
  5107.1 1106.69  5132.7 1110.21  5173.1 1112.36  5178.7 1113.45  5193.3 1113.05
  5273.4 1115.91  5327.0 1119.76  5334.7 1119.55  5425.5 1127.75  5470.0 1130.32
#Mann=6,-1,0
  4453.8    0.12       0  4506.9    0.05       0  4978.9    0.12       0
  4995.0    0.07       0  4999.5    0.12       0  5273.4    0.05       0
Bank Sta=4995,4999.5
Exp/Cntr=0.3,0.1

Chan Stop Cuts=-1