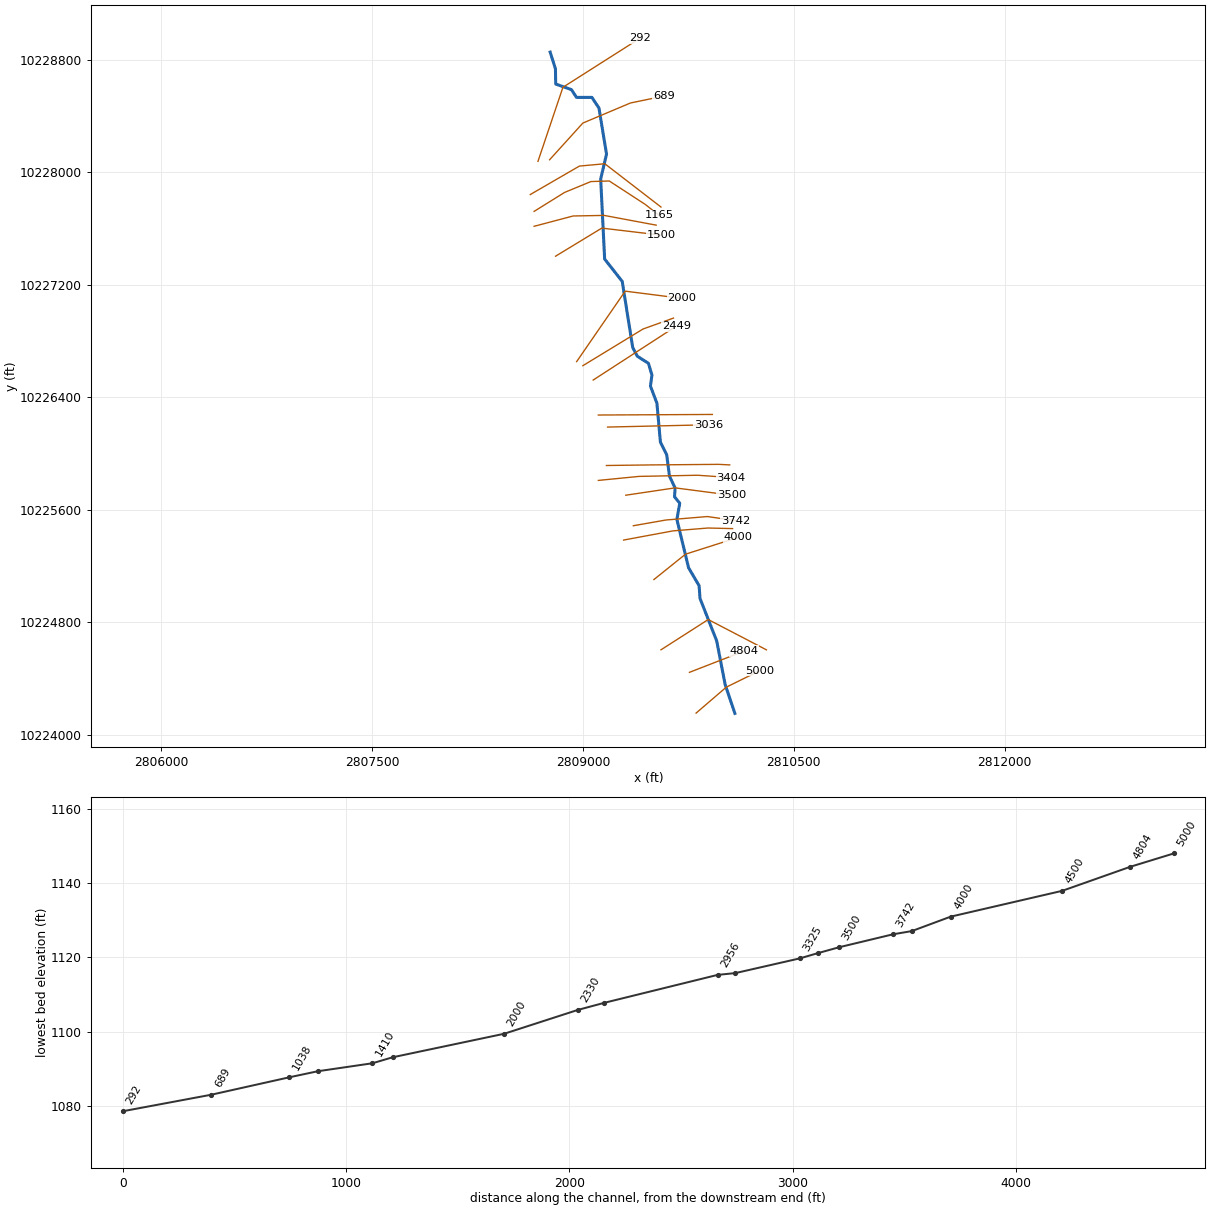
--- SANFERNANDO074.prj (project) ---

Proj Title=SANFERNANDO074 Base Level Engineering
Current Plan=p01
Default Exp/Contr=0.3,0.1
English Units
Geom File=g01
Flow File=f01
Plan File=p01
BEGIN DESCRIPTION:
SANFERNANDO074
END DESCRIPTION:

--- SANFERNANDO074.p01 (plan) ---

Plan Title=Multiple Run
Short Identifier=Multiple
Geom File=g01
Flow File=f01
Subcritical Flow
K Sum by GR= 0
Std Step Tol= 0.01
Critical Tol= 0.01
Num of Std Step Trials= 20
Max Error Tol= 0.3
Flow Tol Ratio= 0.001
Split Flow NTrial= 30
Split Flow Tol= 0.02
Split Flow Ratio= 0.02
Log Output Level= 0
Friction Slope Method= 1
Unsteady Friction Slope Method= 2
Unsteady Bridges Friction Slope Method= 1
Parabolic Critical Depth
Global Vel Dist=  1 , 1 , 1
Global Log Level= 0
CheckData=True
Encroach Param= -1, 0, 0, 0
BEGIN DESCRIPTION:
Multiple Run
END DESCRIPTION:

--- SANFERNANDO074.f01 (steady flow) ---

Flow Title=Multiple
Number of Profiles=7
Profile Names=10-year,25-year,50-year,1pct_min,100-year,1pct_plu,500-year
River Rch & RM= SANFERNANDO074,Reach-1,5000
     186     285     328     197     420     892     574
Boundary for River Rch & Prof#=SANFERNANDO074,Reach-1,1
Up Type=0
Dn Type=3
Dn Slope=0.005
Boundary for River Rch & Prof#=SANFERNANDO074,Reach-1,2
Up Type=0
Dn Type=3
Dn Slope=0.005
Boundary for River Rch & Prof#=SANFERNANDO074,Reach-1,3
Up Type=0
Dn Type=3
Dn Slope=0.005
Boundary for River Rch & Prof#=SANFERNANDO074,Reach-1,4
Up Type=0
Dn Type=3
Dn Slope=0.005
Boundary for River Rch & Prof#=SANFERNANDO074,Reach-1,5
Up Type=0
Dn Type=3
Dn Slope=0.005
Boundary for River Rch & Prof#=SANFERNANDO074,Reach-1,6
Up Type=0
Dn Type=3
Dn Slope=0.005
Boundary for River Rch & Prof#=SANFERNANDO074,Reach-1,7
Up Type=0
Dn Type=3
Dn Slope=0.005

--- SANFERNANDO074.g01 (geometry) ---

Geom Title=Existing Conditions

River Reach=SANFERNANDO074,Reach-1
Reach XY= 30
      2810081.50     10224151.00      2810012.50     10224355.00
      2809952.00     10224667.00      2809833.25     10224969.00
      2809827.00     10225059.00      2809752.00     10225187.00
      2809669.00     10225530.00      2809689.25     10225646.00
      2809652.00     10225692.00      2809656.25     10225755.00
      2809616.50     10225837.00      2809596.25     10225991.00
      2809551.75     10226080.00      2809526.75     10226358.00
      2809480.75     10226479.00      2809491.50     10226558.00
      2809466.50     10226641.00      2809387.25     10226692.00
      2809354.75     10226753.00      2809280.00     10227224.00
      2809155.00     10227383.00      2809126.75     10227952.00
      2809168.50     10228130.00      2809114.50     10228457.00
      2809064.25     10228533.00      2808954.75     10228533.00
      2808918.75     10228588.00      2808806.75     10228628.00
      2808805.00     10228736.00      2808767.50     10228855.00

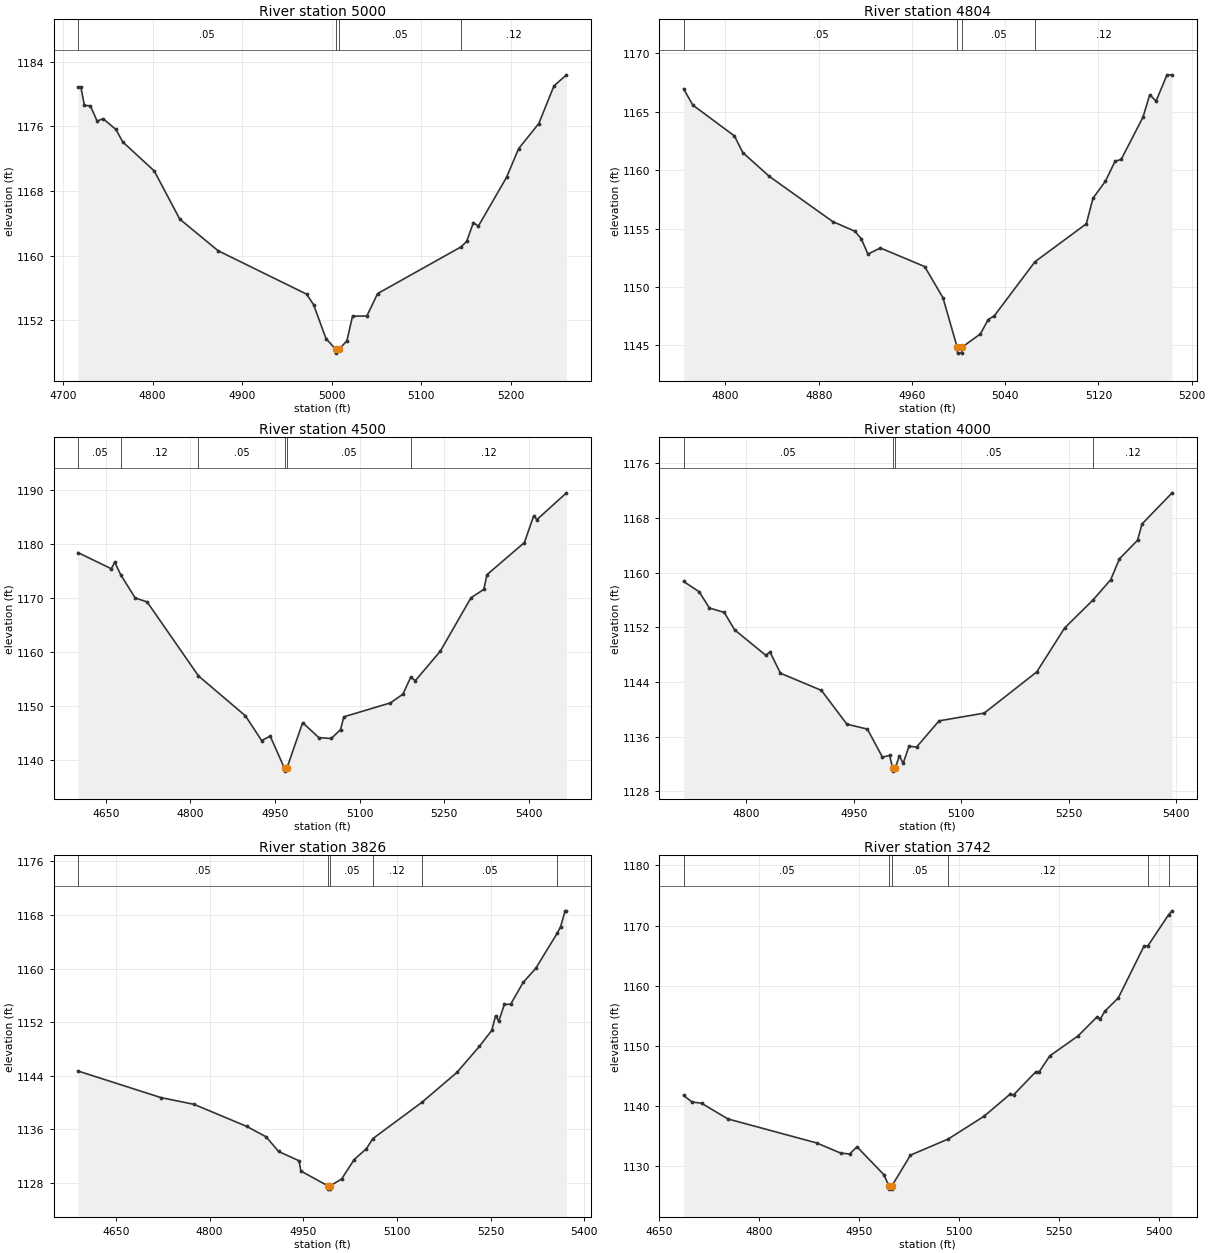
Type RM Length L Ch R = 1,5000,196,196,196
BEGIN DESCRIPTION:
SANFERNANDO074 10.0
END DESCRIPTION:
XS GIS Cut Line= 3
      2809805.65     10224153.08      2810020.58     10224337.64
      2810255.66     10224453.10
#Sta/Elev= 30
  4716.7 1180.81  4720.0 1180.81  4723.9 1178.58  4730.5 1178.53  4738.1 1176.64
  4744.7 1176.94  4759.0 1175.61  4766.7 1174.06  4801.8 1170.48  4830.3 1164.52
  4873.1 1160.61  4971.9 1155.24  4979.6 1153.95  4993.5 1149.75  5004.2 1148.45
  5004.4 1147.95  5008.2 1148.45  5016.8 1149.46  5023.1 1152.52  5039.1 1152.54
  5051.1 1155.31  5144.4 1161.10  5150.5 1161.77  5158.0 1164.09  5163.5 1163.65
  5195.1 1169.71  5208.5 1173.24  5231.0 1176.34  5247.9 1180.99  5261.9 1182.36
#Mann=4,-1,0
  4716.7    0.05       0  5004.2    0.05       0  5008.2    0.05       0
  5144.4    0.12       0
Bank Sta=5004.2,5008.2
Exp/Cntr=0.3,0.1

Type RM Length L Ch R = 1,4804,304,304,304
BEGIN DESCRIPTION:
Mapping XS ab2dd619
END DESCRIPTION:
XS GIS Cut Line= 2
      2809758.35     10224442.99      2810148.95     10224594.89
#Sta/Elev= 30
  4764.1 1166.96  4772.0 1165.57  4807.7 1162.93  4814.9 1161.50  4837.6 1159.47
  4892.0 1155.60  4911.1 1154.77  4916.5 1154.13  4922.2 1152.82  4932.9 1153.34
  4970.9 1151.75  4986.6 1149.08  4998.8 1144.84  4999.1 1144.34  5002.6 1144.34
  5002.8 1144.84  5018.7 1145.98  5025.3 1147.20  5030.7 1147.54  5065.5 1152.16
  5109.6 1155.41  5115.3 1157.60  5126.0 1159.06  5134.2 1160.76  5139.5 1160.92
  5158.2 1164.54  5164.0 1166.46  5169.4 1165.91  5178.8 1168.16  5183.2 1168.16
#Mann=4,-1,0
  4764.1    0.05       0  4998.8    0.05       0  5002.8    0.05       0
  5065.5    0.12       0
Bank Sta=4998.8,5002.8
Exp/Cntr=0.3,0.1

Type RM Length L Ch R = 1,4500,500,500,500
BEGIN DESCRIPTION:
SANFERNANDO074 9.0
END DESCRIPTION:
XS GIS Cut Line= 3
      2809555.72     10224603.14      2809891.95     10224818.52
      2810305.72     10224603.09
#Sta/Elev= 30
  4600.7 1178.41  4659.8 1175.41  4665.8 1176.65  4676.5 1174.29  4702.1 1170.00
  4723.3 1169.26  4814.3 1155.54  4897.6 1148.13  4926.2 1143.56  4941.4 1144.38
  4966.8 1138.39  4967.1 1137.89  4970.8 1138.39  4998.9 1146.88  5027.5 1144.11
  5049.6 1143.94  5066.0 1145.59  5071.9 1147.96  5154.4 1150.54  5176.5 1152.15
  5190.4 1155.30  5198.6 1154.67  5242.8 1160.12  5297.3 1170.05  5319.9 1171.58
  5325.6 1174.32  5391.9 1180.27  5408.4 1185.24  5414.0 1184.52  5466.5 1189.49
#Mann=6,-1,0
  4600.7    0.05       0  4676.5    0.12       0  4814.3    0.05       0
  4966.8    0.05       0  4970.8    0.05       0  5190.4    0.12       0
Bank Sta=4966.8,4970.8
Exp/Cntr=0.3,0.1

Type RM Length L Ch R = 1,4000,174,174,174
BEGIN DESCRIPTION:
SANFERNANDO074 8.0
END DESCRIPTION:
XS GIS Cut Line= 3
      2809505.68     10225103.11      2809729.97     10225283.29
      2810105.72     10225403.12
#Sta/Elev= 30
  4712.3 1158.70  4733.9 1157.20  4748.3 1154.82  4769.1 1154.16  4783.5 1151.62
  4826.7 1147.92  4833.1 1148.34  4847.5 1145.27  4904.7 1142.76  4940.3 1137.81
  4968.9 1137.09  4989.9 1132.99  5000.0 1133.24  5004.0 1131.44  5004.3 1130.94
  5008.0 1131.44  5013.6 1133.19  5018.8 1132.07  5027.0 1134.58  5037.5 1134.46
  5069.0 1138.30  5132.0 1139.43  5205.4 1145.46  5244.2 1151.88  5284.2 1156.02
  5308.6 1158.95  5320.9 1162.02  5346.1 1164.73  5352.4 1167.12  5394.4 1171.67
#Mann=4,-1,0
  4712.3    0.05       0  5004.0    0.05       0  5008.0    0.05       0
  5284.2    0.12       0
Bank Sta=5004,5008
Exp/Cntr=0.3,0.1

Type RM Length L Ch R = 1,3826,84,84,84
BEGIN DESCRIPTION:
Mapping XS 7a20927b
END DESCRIPTION:
XS GIS Cut Line= 4
      2809289.81     10225383.88      2809640.75     10225449.17
      2809889.66     10225469.57      2810065.11     10225465.49
#Sta/Elev= 30
  4589.2 1144.70  4722.0 1140.73  4774.8 1139.73  4859.6 1136.42  4890.5 1134.87
  4910.5 1132.68  4943.2 1131.29  4946.1 1129.76  4989.2 1127.56  4989.5 1127.06
  4993.0 1127.06  4993.2 1127.56  5011.3 1128.57  5031.4 1131.47  5051.0 1133.10
  5061.3 1134.60  5139.7 1140.01  5195.9 1144.48  5231.9 1148.38  5251.9 1150.78
  5257.9 1152.97  5262.9 1152.13  5271.9 1154.64  5282.0 1154.67  5302.0 1157.93
  5322.0 1160.01  5356.9 1165.33  5362.0 1166.26  5369.2 1168.62  5371.4 1168.62
#Mann=6,-1,0
  4589.2    0.05       0  4989.2    0.03       0  4993.2    0.05       0
  5061.3    0.12       0  5139.7    0.05       0  5356.9    0.12       0
Bank Sta=4989.2,4993.2
Exp/Cntr=0.3,0.1

Type RM Length L Ch R = 1,3742,242,242,242
BEGIN DESCRIPTION:
Mapping XS f242a0ed
END DESCRIPTION:
XS GIS Cut Line= 4
      2809359.16     10225485.89      2809591.79     10225526.70
      2809885.58     10225551.18      2810085.56     10225522.61
#Sta/Elev= 30
  4686.4 1141.78  4698.7 1140.70  4713.3 1140.47  4753.0 1137.86  4885.9 1133.88
  4922.0 1132.19  4935.5 1132.04  4946.6 1133.23  4986.7 1128.62  4994.7 1126.70
  4995.0 1126.20  4998.5 1126.20  4998.7 1126.70  5026.8 1131.85  5083.3 1134.52
  5137.2 1138.31  5176.4 1141.99  5181.4 1141.85  5214.9 1145.71  5220.0 1145.71
  5235.9 1148.35  5278.1 1151.65  5306.6 1154.81  5311.6 1154.47  5318.5 1155.78
  5338.7 1157.99  5377.3 1166.62  5383.2 1166.66  5414.2 1171.82  5419.4 1172.45
#Mann=6,-1,0
  4686.4    0.05       0  4994.7    0.03       0  4998.7    0.05       0
  5083.3    0.12       0  5383.2    0.05       0  5414.2    0.12       0
Bank Sta=4994.7,4998.7
Exp/Cntr=0.3,0.1

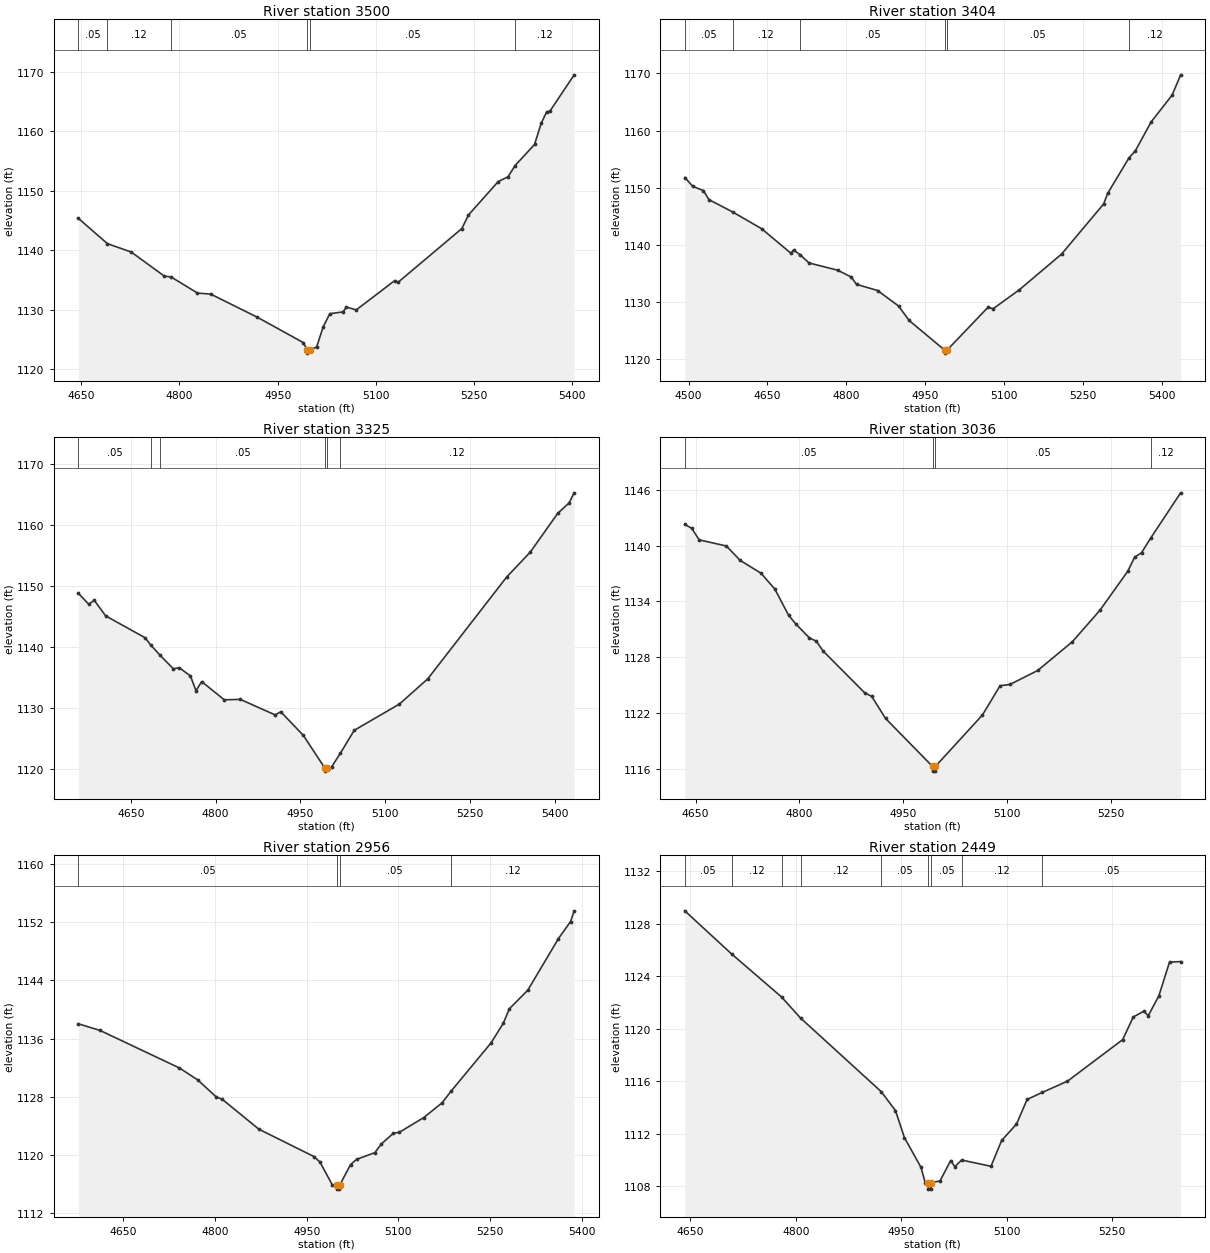
Type RM Length L Ch R = 1,3500,96,96,96
BEGIN DESCRIPTION:
SANFERNANDO074 7.0
END DESCRIPTION:
XS GIS Cut Line= 3
      2809305.65     10225703.11      2809656.19     10225755.23
      2810055.71     10225703.11
#Sta/Elev= 30
  4645.6 1145.39  4690.0 1141.13  4726.5 1139.71  4777.1 1135.65  4787.1 1135.54
  4827.6 1132.81  4847.8 1132.64  4918.6 1128.77  4989.4 1124.47  4995.2 1123.21
  4995.5 1122.71  4999.2 1123.21  5009.6 1123.75  5019.7 1127.17  5029.7 1129.34
  5049.9 1129.65  5055.0 1130.46  5070.1 1129.98  5128.9 1134.92  5134.0 1134.63
  5231.4 1143.67  5241.5 1145.96  5286.9 1151.57  5302.0 1152.39  5312.6 1154.26
  5342.4 1157.81  5352.5 1161.35  5360.9 1163.30  5365.9 1163.42  5402.9 1169.53
#Mann=6,-1,0
  4645.6    0.05       0  4690.0    0.12       0  4787.1    0.05       0
  4995.2    0.05       0  4999.2    0.05       0  5312.6    0.12       0
Bank Sta=4995.2,4999.2
Exp/Cntr=0.3,0.1

Type RM Length L Ch R = 1,3404,79,79,79
BEGIN DESCRIPTION:
Mapping XS b7dac223
END DESCRIPTION:
XS GIS Cut Line= 4
      2809110.34     10225808.26      2809400.00     10225836.82
      2809816.21     10225844.98      2810051.79     10225828.73
#Sta/Elev= 30
  4492.7 1151.79  4508.1 1150.23  4528.2 1149.51  4538.3 1147.94  4583.6 1145.78
  4638.8 1142.85  4694.5 1138.57  4699.6 1139.12  4711.6 1138.34  4729.2 1136.86
  4783.8 1135.59  4809.5 1134.40  4819.5 1133.12  4859.5 1132.05  4899.5 1129.34
  4919.5 1126.82  4987.5 1121.61  4987.7 1121.11  4991.5 1121.61  5069.5 1129.10
  5079.5 1128.87  5129.5 1132.19  5209.6 1138.41  5289.7 1147.17  5297.3 1149.01
  5337.7 1155.19  5349.9 1156.43  5380.0 1161.49  5420.1 1166.20  5436.2 1169.73
#Mann=6,-1,0
  4492.7    0.05       0  4583.6    0.12       0  4711.6    0.05       0
  4987.5    0.05       0  4991.5    0.05       0  5337.7    0.12       0
Bank Sta=4987.5,4991.5
Exp/Cntr=0.3,0.1

Type RM Length L Ch R = 1,3325,289,289,289
BEGIN DESCRIPTION:
Mapping XS 2d665aa7
END DESCRIPTION:
XS GIS Cut Line= 4
      2809167.42     10225914.35      2809481.61     10225918.43
      2809967.19     10225922.51      2810044.77     10225918.43
#Sta/Elev= 30
  4557.2 1148.83  4575.5 1147.06  4585.5 1147.67  4605.5 1145.14  4675.5 1141.55
  4685.0 1140.40  4701.5 1138.73  4725.5 1136.46  4735.5 1136.67  4755.5 1135.32
  4765.5 1132.89  4775.5 1134.38  4815.5 1131.40  4843.8 1131.47  4905.5 1128.93
  4915.5 1129.44  4955.5 1125.57  4993.5 1120.23  4993.7 1119.73  4997.5 1120.23
  5005.5 1120.43  5021.1 1122.68  5045.5 1126.41  5125.5 1130.71  5175.5 1134.82
  5315.5 1151.52  5357.0 1155.56  5405.6 1161.91  5425.6 1163.60  5434.7 1165.27
#Mann=6,-1,0
  4557.2    0.05       0  4685.0    0.12       0  4701.5    0.05       0
  4993.5    0.05       0  4997.5    0.05       0  5021.1    0.12       0
Bank Sta=4993.5,4997.5
Exp/Cntr=0.3,0.1

Type RM Length L Ch R = 1,3036,80,80,80
BEGIN DESCRIPTION:
Mapping XS b8eabacc
END DESCRIPTION:
XS GIS Cut Line= 2
      2809175.59     10226187.74      2809892.21     10226204.03
#Sta/Elev= 30
  4634.5 1142.26  4644.6 1141.85  4655.2 1140.61  4694.6 1139.95  4714.6 1138.40
  4744.6 1137.03  4764.6 1135.33  4784.6 1132.51  4794.6 1131.61  4814.6 1130.08
  4824.6 1129.73  4834.6 1128.66  4894.7 1124.17  4904.7 1123.80  4924.7 1121.43
  4992.7 1116.27  4992.9 1115.77  4996.4 1115.77  4996.7 1116.27  5064.7 1121.79
  5090.3 1124.94  5104.7 1125.08  5144.7 1126.58  5194.7 1129.66  5234.7 1133.05
  5274.8 1137.23  5284.8 1138.75  5294.8 1139.23  5308.3 1140.83  5351.3 1145.66
#Mann=4,-1,0
  4634.5    0.05       0  4992.7    0.05       0  4996.7    0.05       0
  5308.3    0.12       0
Bank Sta=4992.7,4996.7
Exp/Cntr=0.3,0.1

Type RM Length L Ch R = 1,2956,507,507,507
BEGIN DESCRIPTION:
Mapping XS ecc85370
END DESCRIPTION:
XS GIS Cut Line= 2
      2809110.25     10226273.43      2809921.54     10226277.51
#Sta/Elev= 30
  4576.3 1138.04  4611.7 1137.13  4741.7 1131.96  4771.7 1130.31  4801.7 1127.99
  4811.7 1127.65  4871.7 1123.53  4961.7 1119.77  4971.7 1119.01  4991.7 1115.89
  4999.7 1115.78  5000.0 1115.28  5003.5 1115.28  5003.7 1115.78  5021.7 1118.66
  5031.7 1119.38  5061.7 1120.31  5071.7 1121.47  5091.7 1122.96  5101.7 1123.11
  5141.7 1125.14  5171.7 1127.18  5186.1 1128.75  5251.7 1135.42  5271.7 1138.12
  5281.7 1140.12  5311.7 1142.66  5361.7 1149.74  5381.7 1152.12  5387.6 1153.59
#Mann=4,-1,0
  4576.3    0.05       0  4999.7    0.05       0  5003.7    0.05       0
  5186.1    0.12       0
Bank Sta=4999.7,5003.7
Exp/Cntr=0.3,0.1

Type RM Length L Ch R = 1,2449,119,119,119
BEGIN DESCRIPTION:
Mapping XS 399e72cb
END DESCRIPTION:
XS GIS Cut Line= 2
      2809073.59     10226522.36      2809665.24     10226905.91
#Sta/Elev= 30
  4642.1 1129.00  4708.7 1125.71  4779.7 1122.43  4806.8 1120.82  4921.3 1115.22
  4941.7 1113.77  4954.4 1111.71  4978.0 1109.44  4983.9 1108.28  4988.2 1108.28
  4988.5 1107.78  4992.0 1107.78  4992.2 1108.28  5005.0 1108.40  5020.2 1109.96
  5026.1 1109.49  5035.8 1110.00  5077.5 1109.52  5092.7 1111.49  5113.8 1112.74
  5128.9 1114.62  5150.3 1115.15  5186.3 1116.01  5264.8 1119.18  5279.9 1120.91
  5295.1 1121.35  5301.1 1121.00  5316.2 1122.51  5331.4 1125.09  5347.2 1125.13
#Mann=9,-1,0
  4642.1    0.05       0  4708.7    0.12       0  4779.7    0.05       0
  4806.8    0.12       0  4921.3    0.05       0  4988.2    0.03       0
  4992.2    0.05       0  5035.8    0.12       0  5150.3    0.05       0
Bank Sta=4988.2,4992.2
Exp/Cntr=0.3,0.1

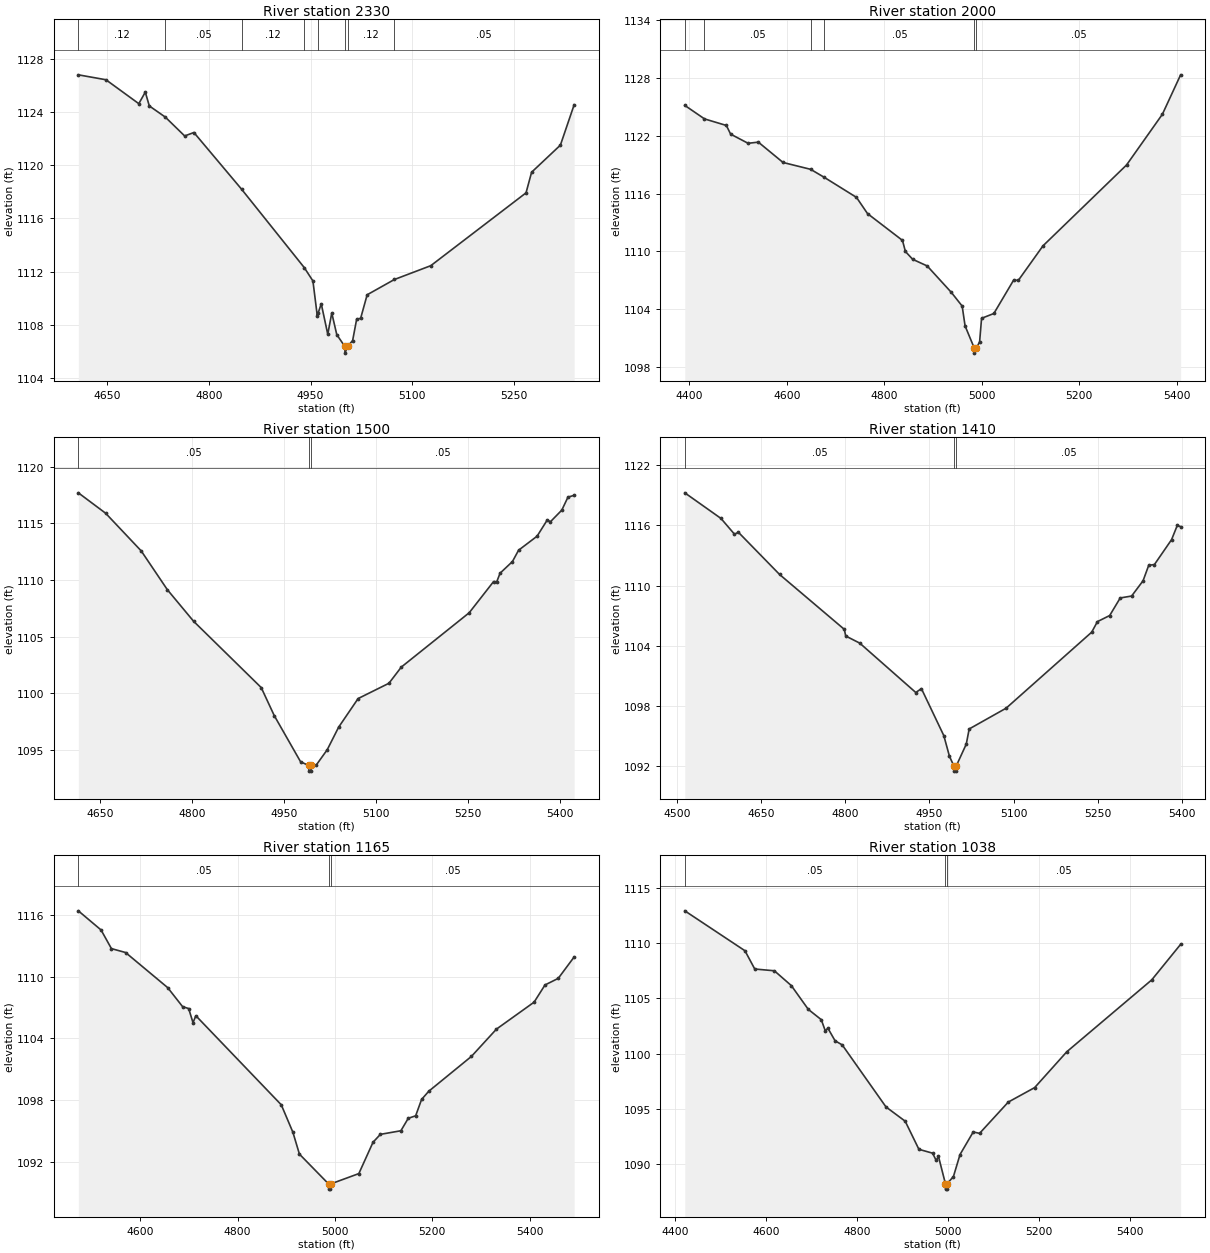
Type RM Length L Ch R = 1,2330,330,330,330
BEGIN DESCRIPTION:
Mapping XS 3124d77f
END DESCRIPTION:
XS GIS Cut Line= 3
      2809000.12     10226624.35      2809428.57     10226885.51
      2809644.82     10226963.03
#Sta/Elev= 30
  4607.3 1126.80  4648.0 1126.43  4696.5 1124.63  4706.1 1125.50  4712.0 1124.46
  4735.6 1123.62  4764.2 1122.20  4777.8 1122.46  4848.2 1118.19  4940.7 1112.29
  4953.4 1111.29  4959.8 1108.68  4960.9 1108.85  4965.7 1109.57  4975.3 1107.28
  4981.2 1108.88  4988.6 1107.25  5000.5 1106.36  5000.7 1105.86  5004.5 1106.36
  5012.0 1106.81  5017.9 1108.41  5023.8 1108.48  5033.4 1110.25  5073.6 1111.40
  5127.3 1112.44  5267.8 1117.92  5276.0 1119.47  5318.5 1121.51  5338.8 1124.55
#Mann=8,-1,0
  4607.3    0.12       0  4735.6    0.05       0  4848.2    0.12       0
  4940.7    0.05       0  4960.9    0.12       0  5000.5    0.07       0
  5004.5    0.12       0  5073.6    0.05       0
Bank Sta=5000.5,5004.5
Exp/Cntr=0.3,0.1

Type RM Length L Ch R = 1,2000,500,500,500
BEGIN DESCRIPTION:
SANFERNANDO074 4.0
END DESCRIPTION:
XS GIS Cut Line= 3
      2808955.70     10226653.13      2809301.13     10227154.69
      2809705.66     10227103.11
#Sta/Elev= 30
  4391.0 1125.14  4431.4 1123.74  4476.2 1123.06  4485.0 1122.16  4520.8 1121.21
  4541.8 1121.33  4592.5 1119.22  4649.1 1118.51  4677.3 1117.67  4743.1 1115.60
  4765.7 1113.92  4837.4 1111.14  4843.4 1109.99  4858.3 1109.18  4888.1 1108.49
  4937.4 1105.76  4959.8 1104.33  4965.8 1102.27  4984.8 1099.95  4985.0 1099.45
  4988.8 1099.95  4995.6 1100.63  4999.6 1103.06  5024.8 1103.56  5065.1 1107.00
  5075.2 1107.01  5125.6 1110.58  5296.9 1118.96  5370.4 1124.22  5407.8 1128.31
#Mann=6,-1,0
  4391.0    0.12       0  4431.4    0.05       0  4649.1    0.12       0
  4677.3    0.05       0  4984.8    0.05       0  4988.8    0.05       0
Bank Sta=4984.8,4988.8
Exp/Cntr=0.3,0.1

Type RM Length L Ch R = 1,1500,90,90,90
BEGIN DESCRIPTION:
SANFERNANDO074 3.0
END DESCRIPTION:
XS GIS Cut Line= 3
      2808805.71     10227403.13      2809134.89     10227603.19
      2809555.72     10227553.11
#Sta/Elev= 30
  4614.8 1117.70  4659.3 1115.90  4717.4 1112.57  4760.1 1109.14  4802.8 1106.36
  4913.2 1100.50  4934.5 1098.02  4977.5 1093.94  4990.7 1093.62  4990.9 1093.12
  4994.4 1093.12  4994.7 1093.62  5002.9 1093.65  5020.9 1095.01  5039.5 1097.00
  5071.3 1099.53  5121.6 1100.88  5141.8 1102.31  5252.6 1107.11  5292.3 1109.86
  5297.4 1109.83  5302.9 1110.60  5323.1 1111.63  5333.1 1112.63  5363.3 1113.87
  5380.0 1115.31  5385.0 1115.14  5403.6 1116.17  5413.7 1117.32  5423.8 1117.48
#Mann=3,-1,0
  4614.8    0.05       0  4990.7    0.05       0  4994.7    0.05       0
Bank Sta=4990.7,4994.7
Exp/Cntr=0.3,0.1

Type RM Length L Ch R = 1,1410,245,245,245
BEGIN DESCRIPTION:
Mapping XS c8a2563e
END DESCRIPTION:
XS GIS Cut Line= 4
      2808653.29     10227615.92      2808930.75     10227689.36
      2809151.09     10227693.44      2809521.59     10227624.23
#Sta/Elev= 30
  4513.7 1119.24  4578.2 1116.69  4602.3 1115.12  4609.3 1115.31  4682.7 1111.11
  4798.2 1105.64  4800.7 1104.98  4825.7 1104.27  4925.7 1099.35  4935.7 1099.74
  4975.7 1095.05  4985.7 1093.00  4993.7 1092.02  4993.9 1091.52  4997.4 1091.52
  4997.7 1092.02  5015.7 1094.21  5020.9 1095.72  5086.8 1097.79  5239.4 1105.36
  5249.6 1106.41  5271.5 1107.02  5290.3 1108.77  5310.6 1108.96  5331.0 1110.48
  5341.1 1112.02  5351.3 1112.10  5381.9 1114.58  5392.0 1115.99  5398.0 1115.87
#Mann=3,-1,0
  4513.7    0.05       0  4993.7    0.05       0  4997.7    0.05       0
Bank Sta=4993.7,4997.7
Exp/Cntr=0.3,0.1

Type RM Length L Ch R = 1,1165,127,127,127
BEGIN DESCRIPTION:
Mapping XS 4a80fda8
END DESCRIPTION:
XS GIS Cut Line= 6
      2808653.26     10227722.00      2808869.54     10227856.66
      2809057.24     10227934.19      2809187.82     10227938.27
      2809444.89     10227770.97      2809541.79     10227694.26
#Sta/Elev= 30
  4472.6 1116.40  4519.3 1114.54  4540.6 1112.73  4569.7 1112.35  4656.2 1108.94
  4686.9 1107.09  4699.3 1106.91  4708.2 1105.54  4714.1 1106.21  4889.6 1097.56
  4913.5 1094.89  4926.9 1092.77  4986.9 1089.87  4987.2 1089.37  4990.7 1089.37
  4990.9 1089.87  5049.0 1090.88  5078.1 1093.92  5093.2 1094.69  5135.4 1095.04
  5150.5 1096.25  5165.7 1096.49  5177.9 1098.08  5192.7 1098.88  5280.3 1102.26
  5331.7 1104.91  5409.1 1107.53  5431.5 1109.20  5458.7 1109.84  5491.4 1111.92
#Mann=3,-1,0
  4472.6    0.05       0  4986.9    0.05       0  4990.9    0.05       0
Bank Sta=4986.9,4990.9
Exp/Cntr=0.3,0.1

Type RM Length L Ch R = 1,1038,349,349,349
BEGIN DESCRIPTION:
SANFERNANDO074 2.0
END DESCRIPTION:
XS GIS Cut Line= 4
      2808626.12     10227841.96      2808975.63     10228044.37
      2809156.26     10228060.84      2809555.70     10227753.10
#Sta/Elev= 30
  4421.0 1112.91  4553.2 1109.30  4574.7 1107.65  4617.8 1107.49  4655.1 1106.15
  4692.4 1104.00  4720.9 1103.07  4729.7 1102.06  4735.4 1102.30  4751.2 1101.16
  4766.9 1100.79  4863.1 1095.18  4905.3 1093.89  4935.4 1091.35  4965.5 1091.00
  4973.4 1090.34  4978.4 1090.71  4993.6 1088.25  4993.9 1087.75  4997.4 1087.75
  4997.6 1088.25  5011.3 1088.89  5025.8 1090.88  5054.8 1092.92  5068.7 1092.79
  5131.8 1095.62  5189.8 1096.93  5260.4 1100.17  5447.1 1106.67  5510.5 1109.88
#Mann=3,-1,0
  4421.0    0.05       0  4993.6    0.05       0  4997.6    0.05       0
Bank Sta=4993.6,4997.6
Exp/Cntr=0.3,0.1

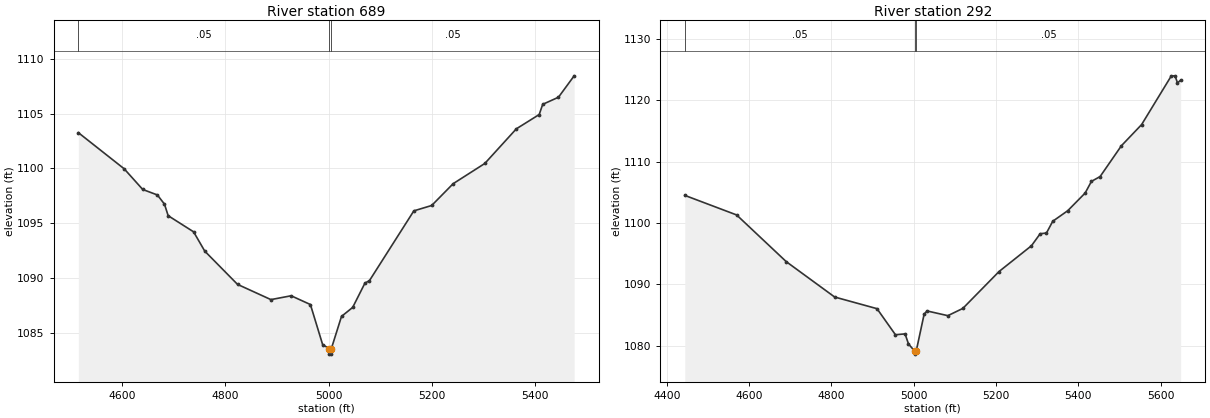
Type RM Length L Ch R = 1,689,397,397,397
BEGIN DESCRIPTION:
Mapping XS 0e3528f1
END DESCRIPTION:
XS GIS Cut Line= 4
      2808763.47     10228089.28      2809000.12     10228350.40
      2809338.80     10228493.22      2809575.42     10228542.18
#Sta/Elev= 30
  4514.8 1103.26  4603.8 1099.96  4639.7 1098.08  4668.1 1097.58  4681.9 1096.74
  4689.0 1095.69  4738.3 1094.22  4760.0 1092.46  4823.5 1089.43  4888.3 1088.04
  4927.5 1088.39  4964.9 1087.59  4988.6 1083.94  5001.5 1083.57  5001.7 1083.07
  5005.2 1083.07  5005.5 1083.57  5025.2 1086.51  5046.9 1087.33  5070.6 1089.54
  5079.4 1089.77  5165.5 1096.13  5200.1 1096.62  5241.8 1098.61  5303.1 1100.45
  5364.3 1103.61  5408.6 1104.91  5415.4 1105.84  5446.0 1106.49  5476.4 1108.44
#Mann=3,-1,0
  4514.8    0.05       0  5001.5    0.05       0  5005.5    0.05       0
Bank Sta=5001.5,5005.5
Exp/Cntr=0.3,0.1

Type RM Length L Ch R = 1,292,0,0,0
BEGIN DESCRIPTION:
SANFERNANDO074 1.0
END DESCRIPTION:
XS GIS Cut Line= 3
      2808680.69     10228078.12      2808858.25     10228605.00
      2809405.65     10228953.09
#Sta/Elev= 30
  4444.0 1104.50  4569.9 1101.31  4690.6 1093.69  4808.1 1087.93  4911.0 1086.03
  4955.8 1081.78  4979.2 1081.92  4987.5 1080.28  5002.3 1079.12  5002.6 1078.62
  5006.3 1079.12  5025.5 1085.13  5032.5 1085.66  5083.1 1084.89  5119.5 1086.07
  5207.6 1092.09  5286.3 1096.29  5307.5 1098.25  5322.7 1098.36  5338.0 1100.28
  5374.4 1102.00  5416.7 1104.88  5432.0 1106.78  5453.1 1107.57  5504.8 1112.59
  5553.9 1116.04  5625.9 1123.96  5635.2 1123.99  5641.1 1122.83  5648.7 1123.28
#Mann=3,-1,0
  4444.0    0.05       0  5002.3    0.05       0  5006.3    0.05       0
Bank Sta=5002.3,5006.3
Exp/Cntr=0.3,0.1

Chan Stop Cuts=-1