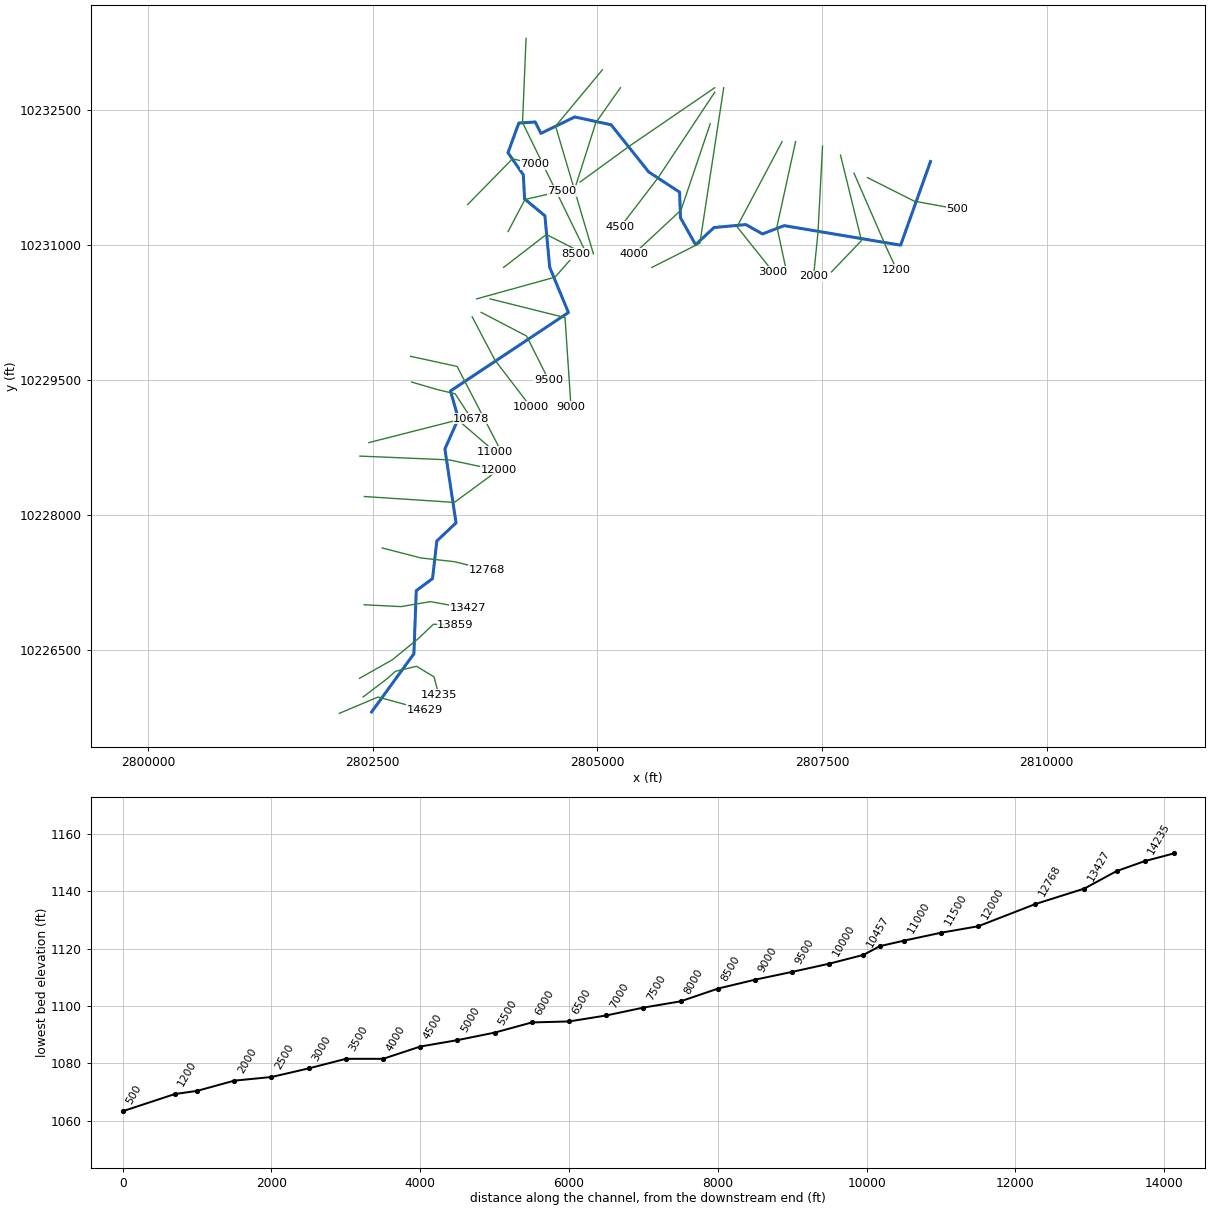
--- SANFERNANDO075.prj (project) ---

Proj Title=SANFERNANDO075 Base Level Engineering
Current Plan=p01
Default Exp/Contr=0.3,0.1
English Units
Geom File=g01
Flow File=f01
Plan File=p01
BEGIN DESCRIPTION:
SANFERNANDO075
END DESCRIPTION:

--- SANFERNANDO075.p01 (plan) ---

Plan Title=Multiple Run
Short Identifier=Multiple
Geom File=g01
Flow File=f01
Subcritical Flow
K Sum by GR= 0
Std Step Tol= 0.01
Critical Tol= 0.01
Num of Std Step Trials= 20
Max Error Tol= 0.3
Flow Tol Ratio= 0.001
Split Flow NTrial= 30
Split Flow Tol= 0.02
Split Flow Ratio= 0.02
Log Output Level= 0
Friction Slope Method= 1
Unsteady Friction Slope Method= 2
Unsteady Bridges Friction Slope Method= 1
Parabolic Critical Depth
Global Vel Dist=  1 , 1 , 1
Global Log Level= 0
CheckData=True
Encroach Param= -1, 0, 0, 0
BEGIN DESCRIPTION:
Multiple Run
END DESCRIPTION:

--- SANFERNANDO075.f01 (steady flow) ---

Flow Title=Multiple
Number of Profiles=7
Profile Names=10-year,25-year,50-year,1pct_min,100-year,1pct_plu,500-year
River Rch & RM= SANFERNANDO075,Reach-1,14629
     511     843     922     560    1211    2620    1637
River Rch & RM= SANFERNANDO075,Reach-1,2500
     563     935    1013     586    1334    3036    1802
River Rch & RM= SANFERNANDO075,Reach-1,500
    2770    5104    8727    7528   12705   21444   17803
Boundary for River Rch & Prof#=SANFERNANDO075,Reach-1,1
Up Type=0
Dn Type=3
Dn Slope=0.005
Boundary for River Rch & Prof#=SANFERNANDO075,Reach-1,2
Up Type=0
Dn Type=3
Dn Slope=0.005
Boundary for River Rch & Prof#=SANFERNANDO075,Reach-1,3
Up Type=0
Dn Type=3
Dn Slope=0.005
Boundary for River Rch & Prof#=SANFERNANDO075,Reach-1,4
Up Type=0
Dn Type=3
Dn Slope=0.005
Boundary for River Rch & Prof#=SANFERNANDO075,Reach-1,5
Up Type=0
Dn Type=3
Dn Slope=0.005
Boundary for River Rch & Prof#=SANFERNANDO075,Reach-1,6
Up Type=0
Dn Type=3
Dn Slope=0.005
Boundary for River Rch & Prof#=SANFERNANDO075,Reach-1,7
Up Type=0
Dn Type=3
Dn Slope=0.005

--- SANFERNANDO075.g01 (geometry) ---

Geom Title=Existing Conditions

River Reach=SANFERNANDO075,Reach-1
Reach XY= 30
      2802486.50     10225805.00      2802957.25     10226453.00
      2802983.25     10227155.00      2803164.50     10227289.00
      2803212.50     10227708.00      2803426.25     10227910.00
      2803302.25     10228732.00      2803452.00     10229070.00
      2803364.50     10229378.00      2804677.00     10230251.00
      2804468.75     10230755.00      2804415.25     10231328.00
      2804189.50     10231515.00      2804175.00     10231785.00
      2804004.25     10232030.00      2804125.00     10232360.00
      2804308.25     10232372.00      2804370.75     10232245.00
      2804748.00     10232428.00      2805152.00     10232341.00
      2805570.75     10231816.00      2805914.50     10231591.00
      2805925.00     10231305.00      2806092.50     10231006.00
      2806298.00     10231197.00      2806652.00     10231230.00
      2806837.50     10231126.00      2807079.25     10231218.00
      2808375.00     10231001.00      2808707.50     10231932.00

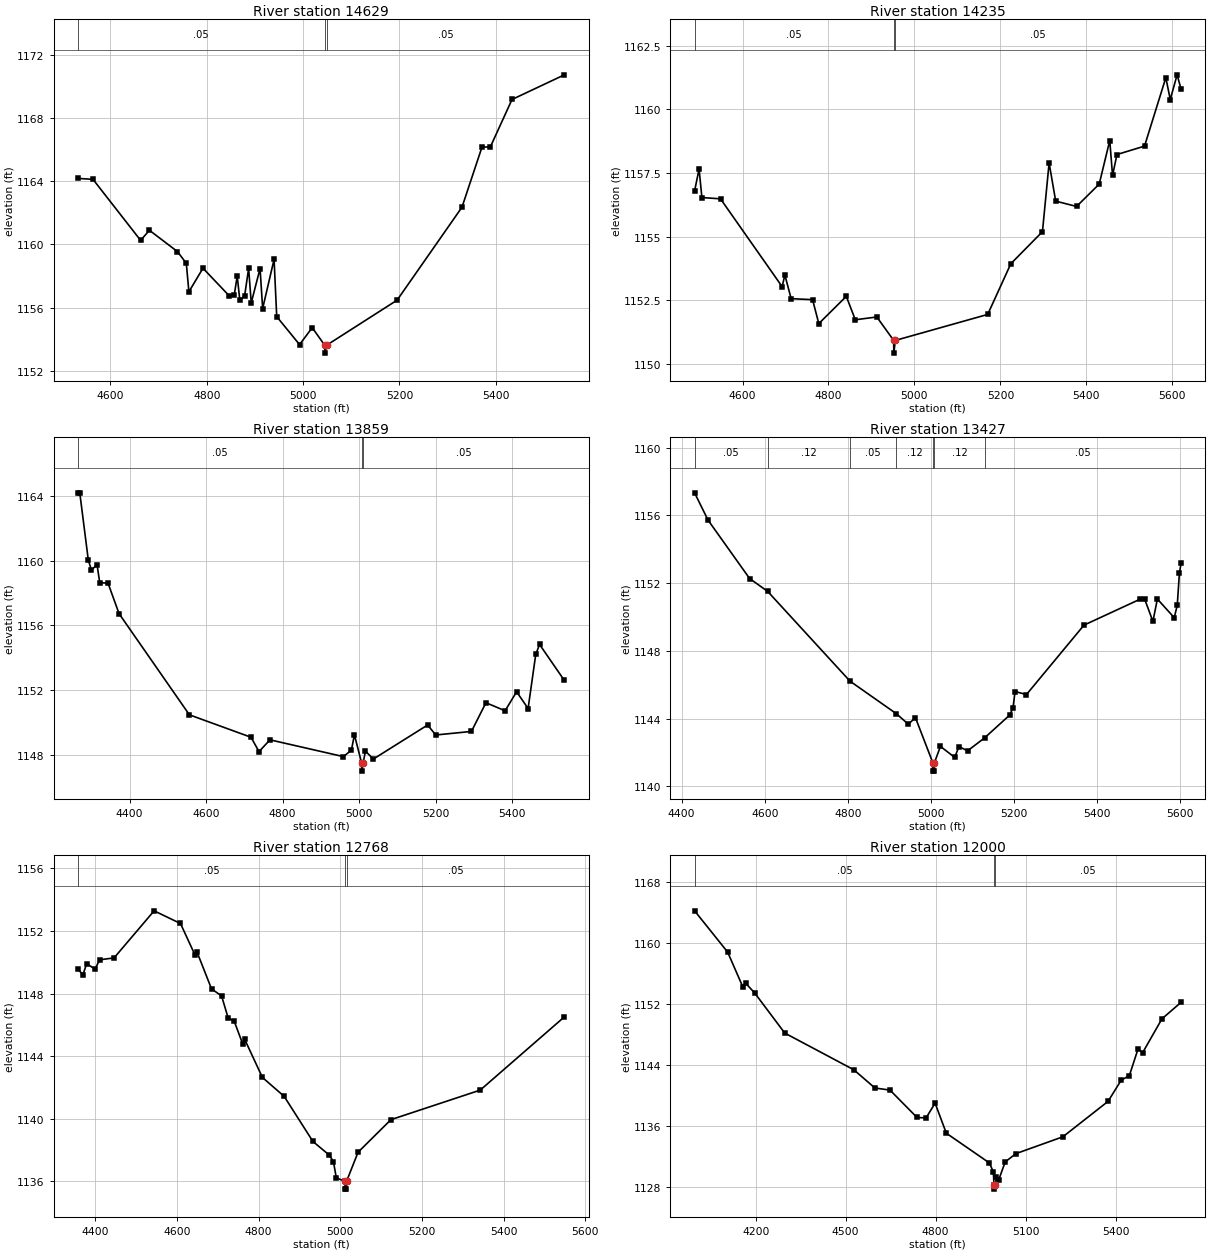
Type RM Length L Ch R = 1,14629,394,394,394
BEGIN DESCRIPTION:
SANFERNANDO075 29.0
END DESCRIPTION:
XS GIS Cut Line= 3
      2802126.72     10225789.13      2802557.50     10225971.00
      2803080.64     10225828.12
#Sta/Elev= 30
  4532.4 1164.18  4563.8 1164.12  4662.7 1160.26  4680.9 1160.90  4739.2 1159.55
  4757.5 1158.81  4762.9 1157.01  4792.1 1158.50  4846.1 1156.77  4856.9 1156.78
  4863.2 1158.00  4868.6 1156.48  4878.6 1156.76  4886.9 1158.49  4892.3 1156.31
  4910.6 1158.48  4916.0 1155.95  4939.7 1159.06  4945.2 1155.44  4992.6 1153.67
  5018.9 1154.74  5044.8 1153.63  5045.1 1153.13  5048.8 1153.63  5195.1 1156.48
  5329.8 1162.36  5371.3 1166.16  5388.7 1166.17  5433.6 1169.17  5542.3 1170.73
#Mann=3,-1,0
  4532.4    0.05       0  5044.8    0.05       0  5048.8    0.05       0
Bank Sta=5044.8,5048.8
Exp/Cntr=0.3,0.1

Type RM Length L Ch R = 1,14235,376,376,376
BEGIN DESCRIPTION:
Mapping XS 9925d0cd
END DESCRIPTION:
XS GIS Cut Line= 6
      2802392.15     10225972.03      2802662.01     10226177.21
      2802751.22     10226257.50      2802987.64     10226313.26
      2803181.67     10226195.05      2803232.97     10225998.78
#Sta/Elev= 30
  4488.5 1156.79  4498.9 1157.65  4505.5 1156.53  4548.8 1156.48  4692.2 1153.03
  4698.5 1153.49  4713.1 1152.56  4763.0 1152.52  4777.5 1151.58  4841.5 1152.65
  4862.4 1151.73  4912.5 1151.84  4951.7 1150.92  4952.0 1150.42  4955.7 1150.92
  5170.5 1151.94  5224.3 1153.93  5297.9 1155.19  5313.4 1157.89  5328.7 1156.39
  5377.3 1156.18  5430.0 1157.06  5454.5 1158.77  5461.0 1157.40  5471.3 1158.22
  5535.4 1158.55  5585.0 1161.24  5595.3 1160.38  5611.2 1161.35  5620.5 1160.79
#Mann=3,-1,0
  4488.5    0.05       0  4951.7    0.03       0  4955.7    0.05       0
Bank Sta=4951.7,4955.7
Exp/Cntr=0.3,0.1

Type RM Length L Ch R = 1,13859,432,432,432
BEGIN DESCRIPTION:
Mapping XS 69079103
END DESCRIPTION:
XS GIS Cut Line= 5
      2802352.01     10226179.45      2802715.53     10226384.63
      2803003.25     10226618.81      2803174.98     10226781.63
      2803420.28     10226770.48
#Sta/Elev= 30
  4265.1 1164.22  4270.1 1164.22  4292.3 1160.06  4300.5 1159.43  4315.2 1159.77
  4322.2 1158.65  4343.9 1158.62  4372.7 1156.73  4556.4 1150.46  4717.3 1149.07
  4738.2 1148.18  4766.9 1148.91  4958.6 1147.87  4979.5 1148.27  4987.4 1149.22
  5006.2 1147.47  5006.4 1146.97  5010.2 1147.47  5016.1 1148.21  5036.9 1147.72
  5178.6 1149.83  5199.7 1149.21  5293.0 1149.43  5330.9 1151.21  5380.9 1150.71
  5411.0 1151.89  5441.0 1150.85  5461.0 1154.21  5471.0 1154.82  5535.7 1152.59
#Mann=3,-1,0
  4265.1    0.05       0  5006.2    0.03       0  5010.2    0.05       0
Bank Sta=5006.2,5010.2
Exp/Cntr=0.3,0.1

Type RM Length L Ch R = 1,13427,659,659,659
BEGIN DESCRIPTION:
Mapping XS 1b3de034
END DESCRIPTION:
XS GIS Cut Line= 4
      2802403.43     10226998.32      2802813.11     10226977.49
      2803139.50     10227033.05      2803561.89     10226956.88
#Sta/Elev= 30
  4431.3 1157.33  4463.6 1155.72  4563.7 1152.27  4607.1 1151.51  4805.3 1146.21
  4916.7 1144.29  4945.6 1143.67  4962.6 1144.06  5004.4 1141.40  5004.7 1140.90
  5008.2 1140.90  5008.4 1141.40  5022.8 1142.36  5057.1 1141.71  5067.3 1142.35
  5088.1 1142.10  5128.9 1142.86  5189.0 1144.20  5197.3 1144.62  5202.3 1145.60
  5229.7 1145.42  5368.2 1149.52  5504.0 1151.06  5514.2 1151.05  5534.0 1149.74
  5544.7 1151.06  5585.3 1149.96  5592.6 1150.69  5597.7 1152.58  5601.8 1153.18
#Mann=7,-1,0
  4431.3    0.05       0  4607.1    0.12       0  4805.3    0.05       0
  4916.7    0.12       0  5004.4    0.07       0  5008.4    0.12       0
  5128.9    0.05       0
Bank Sta=5004.4,5008.4
Exp/Cntr=0.3,0.1

Type RM Length L Ch R = 1,12768,768,768,768
BEGIN DESCRIPTION:
Mapping XS 7c1850b1
END DESCRIPTION:
XS GIS Cut Line= 4
      2802604.78     10227630.27      2803035.33     10227519.16
      2803410.33     10227477.49      2803769.22     10227387.77
#Sta/Elev= 30
  4357.0 1149.56  4369.5 1149.21  4378.6 1149.91  4399.2 1149.56  4410.2 1150.16
  4445.7 1150.28  4543.8 1153.29  4608.4 1152.48  4643.9 1150.47  4649.0 1150.65
  4684.5 1148.30  4709.1 1147.85  4725.2 1146.44  4740.1 1146.23  4760.7 1144.79
  4765.8 1145.07  4809.1 1142.64  4862.4 1141.43  4932.8 1138.55  4973.1 1137.67
  4983.1 1137.26  4990.2 1136.22  5011.3 1136.00  5011.6 1135.50  5015.1 1135.50
  5015.3 1136.00  5043.5 1137.86  5124.0 1139.94  5342.8 1141.83  5548.9 1146.51
#Mann=3,-1,0
  4357.0    0.05       0  5011.3    0.05       0  5015.3    0.05       0
Bank Sta=5011.3,5015.3
Exp/Cntr=0.3,0.1

Type RM Length L Ch R = 1,12000,500,500,500
BEGIN DESCRIPTION:
SANFERNANDO075 24.0
END DESCRIPTION:
XS GIS Cut Line= 3
      2802405.73     10228203.11      2803407.09     10228137.52
      2803905.71     10228503.13
#Sta/Elev= 30
  3996.5 1164.24  4106.7 1158.83  4156.8 1154.31  4166.8 1154.75  4196.9 1153.47
  4297.1 1148.22  4527.3 1143.41  4597.7 1141.02  4647.8 1140.75  4738.0 1137.16
  4768.1 1137.10  4798.2 1139.04  4835.6 1135.10  4978.6 1131.22  4992.2 1130.07
  4994.8 1128.27  4995.0 1127.77  4998.8 1128.27  5002.7 1129.42  5010.7 1129.03
  5032.0 1131.34  5067.6 1132.42  5224.3 1134.63  5374.8 1139.27  5418.7 1142.05
  5445.8 1142.64  5475.1 1146.18  5489.8 1145.63  5554.6 1150.09  5618.3 1152.25
#Mann=3,-1,0
  3996.5    0.05       0  4994.8    0.05       0  4998.8    0.05       0
Bank Sta=4994.8,4998.8
Exp/Cntr=0.3,0.1

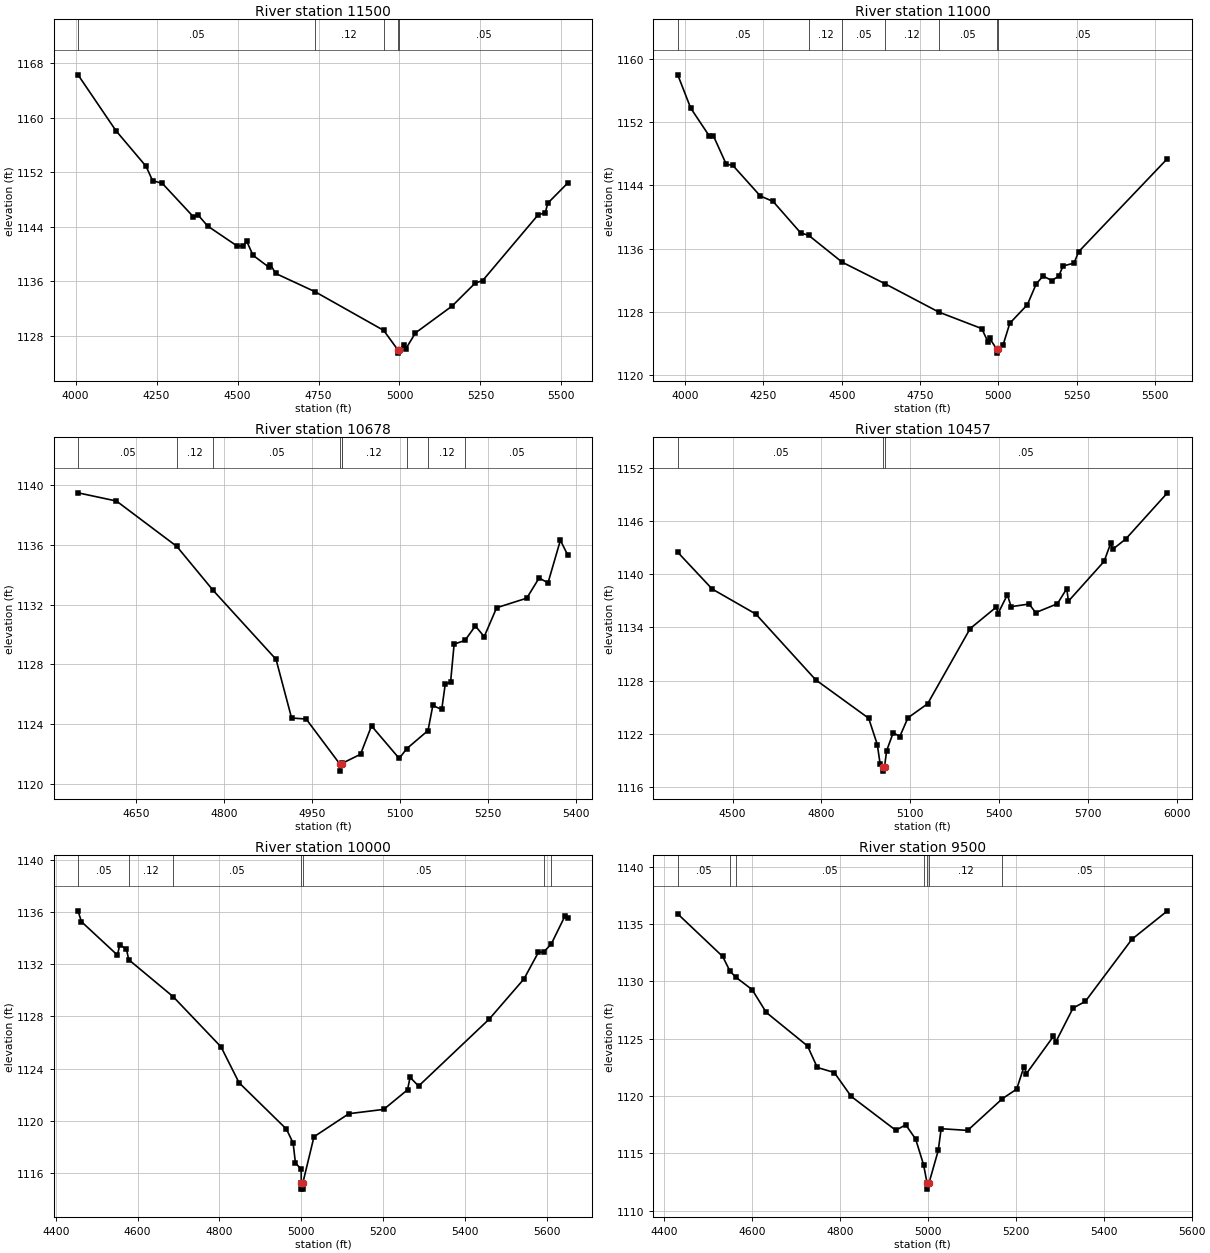
Type RM Length L Ch R = 1,11500,500,500,500
BEGIN DESCRIPTION:
SANFERNANDO075 23.0
END DESCRIPTION:
XS GIS Cut Line= 3
      2802355.66     10228653.11      2803347.48     10228611.23
      2803855.70     10228503.11
#Sta/Elev= 30
  4007.3 1166.25  4124.1 1158.09  4217.5 1152.85  4237.5 1150.76  4267.6 1150.36
  4362.7 1145.51  4377.7 1145.75  4407.7 1144.11  4497.8 1141.22  4517.8 1141.16
  4527.8 1141.93  4547.8 1139.83  4596.4 1138.10  4601.4 1138.46  4617.9 1137.17
  4739.2 1134.50  4951.2 1128.84  4994.6 1126.01  4994.8 1125.51  4998.6 1126.01
  5014.2 1126.70  5019.4 1126.12  5049.3 1128.47  5163.0 1132.42  5233.3 1135.74
  5257.1 1136.14  5427.6 1145.72  5450.3 1146.09  5458.2 1147.47  5519.6 1150.41
#Mann=5,-1,0
  4007.3    0.05       0  4739.2    0.12       0  4951.2    0.05       0
  4994.6    0.05       0  4998.6    0.05       0
Bank Sta=4994.6,4998.6
Exp/Cntr=0.3,0.1

Type RM Length L Ch R = 1,11000,322,322,322
BEGIN DESCRIPTION:
SANFERNANDO075 22.0
END DESCRIPTION:
XS GIS Cut Line= 3
      2802455.66     10228803.11      2803447.18     10229055.34
      2803855.69     10228703.11
#Sta/Elev= 30
  3976.9 1158.03  4018.2 1153.81  4076.6 1150.33  4090.4 1150.31  4131.7 1146.69
  4152.3 1146.56  4240.3 1142.67  4281.2 1141.97  4369.0 1137.99  4394.8 1137.67
  4501.6 1134.27  4638.1 1131.54  4809.6 1127.95  4946.9 1125.85  4966.5 1124.18
  4971.7 1124.64  4994.6 1123.24  4994.9 1122.74  4998.6 1123.24  5014.5 1123.72
  5036.4 1126.53  5092.4 1128.88  5120.9 1131.54  5142.8 1132.52  5170.2 1131.94
  5192.2 1132.49  5206.4 1133.79  5241.5 1134.16  5255.8 1135.59  5539.4 1147.41
#Mann=7,-1,0
  3976.9    0.05       0  4394.8    0.12       0  4501.6    0.05       0
  4638.1    0.12       0  4809.6    0.05       0  4994.6    0.03       0
  4998.6    0.05       0
Bank Sta=4994.6,4998.6
Exp/Cntr=0.3,0.1

Type RM Length L Ch R = 1,10678,221,221,221
BEGIN DESCRIPTION:
Mapping XS 118fcb27
END DESCRIPTION:
XS GIS Cut Line= 4
      2802931.21     10229477.48      2803215.89     10229394.16
      2803417.28     10229345.55      2803597.73     10229067.93
#Sta/Elev= 30
  4550.5 1139.49  4616.0 1138.94  4718.9 1135.90  4780.9 1132.95  4888.1 1128.33
  4914.6 1124.40  4939.5 1124.33  4996.4 1121.34  4996.7 1120.84  5000.4 1121.34
  5000.7 1121.36  5032.1 1121.97  5050.9 1123.87  5098.1 1121.69  5110.8 1122.34
  5147.2 1123.56  5155.4 1125.24  5170.6 1124.97  5176.5 1126.65  5185.7 1126.81
  5191.7 1129.35  5210.3 1129.60  5227.9 1130.57  5243.0 1129.85  5264.2 1131.79
  5315.5 1132.43  5336.6 1133.78  5351.8 1133.46  5372.9 1136.31  5385.4 1135.32
#Mann=9,-1,0
  4550.5    0.05       0  4718.9    0.12       0  4780.9    0.05       0
  4996.4    0.05       0  5000.4    0.05       0  5000.7    0.12       0
  5110.8    0.05       0  5147.2    0.12       0  5210.3    0.05       0
Bank Sta=4996.4,5000.4
Exp/Cntr=0.3,0.1

Type RM Length L Ch R = 1,10457,457,457,457
BEGIN DESCRIPTION:
SANFERNANDO075 21.0
END DESCRIPTION:
XS GIS Cut Line= 3
      2802920.49     10229763.54      2803438.11     10229651.10
      2803955.68     10228653.12
#Sta/Elev= 30
  4314.7 1142.46  4431.0 1138.32  4578.4 1135.50  4780.5 1128.09  4959.5 1123.76
  4988.6 1120.80  4998.1 1118.63  5009.1 1118.30  5009.3 1117.80  5013.1 1118.30
  5020.2 1120.10  5042.4 1122.14  5064.5 1121.69  5092.2 1123.81  5158.6 1125.39
  5302.2 1133.86  5390.7 1136.29  5396.4 1135.56  5427.9 1137.67  5440.6 1136.33
  5501.4 1136.63  5523.5 1135.66  5596.9 1136.66  5628.5 1138.36  5634.1 1136.95
  5754.6 1141.43  5777.1 1143.49  5783.4 1142.79  5827.6 1143.95  5968.6 1149.16
#Mann=3,-1,0
  4314.7    0.05       0  5009.1    0.05       0  5013.1    0.05       0
Bank Sta=5009.1,5013.1
Exp/Cntr=0.3,0.1

Type RM Length L Ch R = 1,10000,500,500,500
BEGIN DESCRIPTION:
SANFERNANDO075 20.0
END DESCRIPTION:
XS GIS Cut Line= 3
      2803605.67     10230203.15      2803859.77     10229720.55
      2804255.66     10229203.14
#Sta/Elev= 30
  4454.6 1136.11  4462.8 1135.28  4551.0 1132.71  4556.6 1133.51  4573.0 1133.16
  4578.5 1132.36  4687.1 1129.52  4804.1 1125.67  4848.1 1122.92  4963.9 1119.36
  4980.3 1118.29  4986.0 1116.76  5000.0 1116.28  5000.3 1115.25  5000.5 1114.75
  5004.0 1114.75  5004.3 1115.25  5031.3 1118.77  5116.6 1120.54  5201.8 1120.87
  5259.9 1122.37  5266.2 1123.33  5287.0 1122.66  5459.3 1127.79  5544.5 1130.88
  5579.9 1132.93  5592.8 1132.95  5611.2 1133.56  5644.3 1135.68  5651.5 1135.57
#Mann=7,-1,0
  4454.6    0.05       0  4578.5    0.12       0  4687.1    0.05       0
  5000.3    0.05       0  5004.3    0.05       0  5592.8    0.12       0
  5611.2    0.05       0
Bank Sta=5000.3,5004.3
Exp/Cntr=0.3,0.1

Type RM Length L Ch R = 1,9500,500,500,500
BEGIN DESCRIPTION:
SANFERNANDO075 19.0
END DESCRIPTION:
XS GIS Cut Line= 3
      2803705.69     10230253.11      2804210.68     10229989.82
      2804455.68     10229503.11
#Sta/Elev= 30
  4430.5 1135.88  4532.7 1132.17  4549.5 1130.88  4562.7 1130.36  4599.7 1129.28
  4631.9 1127.29  4725.9 1124.36  4748.0 1122.49  4786.6 1122.05  4825.1 1119.97
  4926.7 1117.01  4949.3 1117.49  4971.8 1116.25  4989.9 1114.01  4998.0 1112.38
  4998.3 1111.88  5002.0 1112.38  5023.3 1115.25  5029.9 1117.15  5090.2 1117.00
  5169.3 1119.77  5201.8 1120.60  5218.5 1122.57  5224.1 1121.96  5285.5 1125.21
  5291.1 1124.74  5330.1 1127.67  5358.0 1128.25  5464.0 1133.67  5544.9 1136.15
#Mann=7,-1,0
  4430.5    0.05       0  4549.5    0.12       0  4562.7    0.05       0
  4989.9    0.12       0  4998.0    0.07       0  5002.0    0.12       0
  5169.3    0.05       0
Bank Sta=4998,5002
Exp/Cntr=0.3,0.1

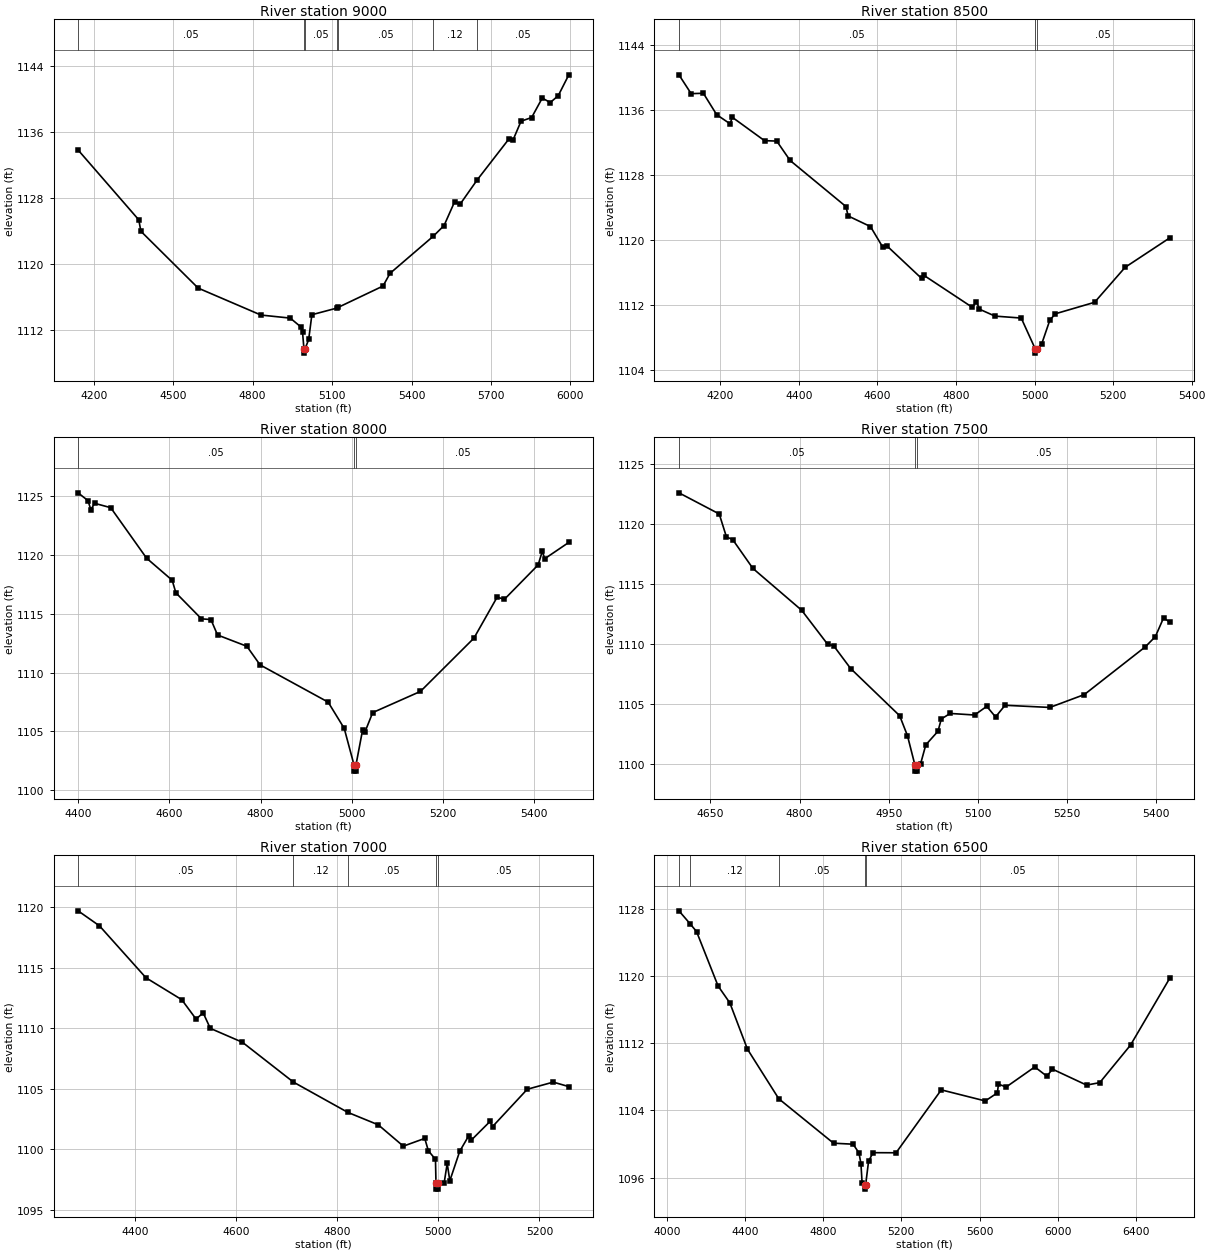
Type RM Length L Ch R = 1,9000,500,500,500
BEGIN DESCRIPTION:
SANFERNANDO075 18.0
END DESCRIPTION:
XS GIS Cut Line= 3
      2803805.70     10230403.11      2804639.31     10230194.56
      2804705.69     10229203.08
#Sta/Elev= 30
  4140.7 1133.81  4370.0 1125.33  4377.8 1123.95  4594.2 1117.05  4831.3 1113.78
  4941.9 1113.41  4983.1 1112.31  4988.2 1111.73  4993.6 1109.66  4993.8 1109.16
  4997.6 1109.66  5011.5 1110.82  5023.5 1113.82  5118.4 1114.63  5122.7 1114.71
  5292.1 1117.30  5318.6 1118.84  5481.4 1123.33  5522.6 1124.64  5562.7 1127.54
  5582.8 1127.21  5648.2 1130.20  5768.6 1135.19  5783.2 1135.03  5813.3 1137.30
  5853.4 1137.75  5893.4 1140.11  5923.7 1139.57  5953.6 1140.39  5993.7 1142.93
#Mann=7,-1,0
  4140.7    0.05       0  4993.6    0.05       0  4997.6    0.05       0
  5118.4    0.12       0  5122.7    0.05       0  5481.4    0.12       0
  5648.2    0.05       0
Bank Sta=4993.6,4997.6
Exp/Cntr=0.3,0.1

Type RM Length L Ch R = 1,8500,500,500,500
BEGIN DESCRIPTION:
SANFERNANDO075 17.0
END DESCRIPTION:
XS GIS Cut Line= 3
      2803655.70     10230403.12      2804528.44     10230644.86
      2804755.68     10230903.11
#Sta/Elev= 30
  4094.4 1140.33  4125.5 1138.01  4156.6 1138.06  4190.5 1135.42  4224.8 1134.29
  4230.0 1135.11  4312.3 1132.22  4343.4 1132.17  4377.5 1129.78  4519.8 1124.10
  4525.1 1122.95  4582.1 1121.64  4613.2 1119.12  4623.6 1119.28  4712.1 1115.26
  4717.3 1115.66  4841.5 1111.69  4851.9 1112.40  4859.7 1111.46  4899.2 1110.61
  4966.0 1110.37  5001.9 1106.55  5002.1 1106.05  5005.9 1106.55  5018.1 1107.18
  5039.0 1110.13  5053.2 1110.90  5152.8 1112.31  5230.6 1116.62  5344.0 1120.24
#Mann=3,-1,0
  4094.4    0.05       0  5001.9    0.05       0  5005.9    0.05       0
Bank Sta=5001.9,5005.9
Exp/Cntr=0.3,0.1

Type RM Length L Ch R = 1,8000,500,500,500
BEGIN DESCRIPTION:
SANFERNANDO075 16.0
END DESCRIPTION:
XS GIS Cut Line= 3
      2803955.68     10230753.11      2804431.12     10231119.94
      2804855.66     10230903.13
#Sta/Elev= 30
  4399.5 1125.26  4421.2 1124.60  4427.6 1123.82  4435.7 1124.37  4471.1 1124.00
  4549.9 1119.71  4606.0 1117.84  4614.2 1116.77  4670.3 1114.56  4691.1 1114.50
  4705.6 1113.19  4770.0 1112.23  4799.0 1110.65  4948.4 1107.49  4983.7 1105.26
  5005.4 1102.13  5005.6 1101.63  5009.1 1101.63  5009.4 1102.13  5024.0 1105.12
  5029.6 1104.99  5046.2 1106.60  5151.1 1108.40  5268.4 1112.92  5319.5 1116.41
  5335.1 1116.21  5409.4 1119.14  5418.4 1120.29  5424.0 1119.67  5476.7 1121.05
#Mann=3,-1,0
  4399.5    0.05       0  5005.4    0.05       0  5009.4    0.05       0
Bank Sta=5005.4,5009.4
Exp/Cntr=0.3,0.1

Type RM Length L Ch R = 1,7500,500,500,500
BEGIN DESCRIPTION:
SANFERNANDO075 15.0
END DESCRIPTION:
XS GIS Cut Line= 3
      2804005.69     10231153.12      2804193.62     10231509.50
      2804605.72     10231603.12
#Sta/Elev= 30
  4597.1 1122.60  4664.9 1120.84  4677.0 1118.93  4687.5 1118.71  4721.5 1116.31
  4803.5 1112.83  4847.5 1109.98  4857.1 1109.89  4885.9 1107.98  4968.4 1104.05
  4981.5 1102.39  4994.1 1099.94  4994.3 1099.44  4997.8 1099.44  4998.1 1099.94
  5003.6 1100.05  5012.4 1101.63  5032.9 1102.76  5038.4 1103.78  5053.4 1104.24
  5094.4 1104.11  5114.9 1104.83  5129.7 1103.95  5145.7 1104.92  5221.0 1104.74
  5279.0 1105.81  5381.5 1109.78  5398.5 1110.63  5412.3 1112.19  5422.6 1111.85
#Mann=3,-1,0
  4597.1    0.05       0  4994.1    0.05       0  4998.1    0.05       0
Bank Sta=4994.1,4998.1
Exp/Cntr=0.3,0.1

Type RM Length L Ch R = 1,7000,500,500,500
BEGIN DESCRIPTION:
SANFERNANDO075 14.0
END DESCRIPTION:
XS GIS Cut Line= 3
      2803555.71     10231453.13      2804054.49     10231962.34
      2804305.70     10231903.11
#Sta/Elev= 30
  4287.2 1119.69  4329.5 1118.45  4421.5 1114.16  4492.3 1112.35  4520.6 1110.75
  4534.7 1111.26  4548.8 1109.98  4612.4 1108.83  4713.3 1105.54  4820.9 1103.04
  4881.2 1102.01  4930.7 1100.25  4973.1 1100.89  4980.2 1099.87  4994.3 1099.16
  4995.3 1097.20  4995.5 1096.70  4999.0 1096.70  4999.3 1097.20  5011.5 1097.22
  5017.5 1098.82  5022.7 1097.39  5042.3 1099.83  5059.9 1101.09  5065.0 1100.74
  5102.2 1102.29  5107.3 1101.87  5175.9 1104.95  5227.3 1105.54  5258.1 1105.17
#Mann=5,-1,0
  4287.2    0.05       0  4713.3    0.12       0  4820.9    0.05       0
  4995.3    0.05       0  4999.3    0.05       0
Bank Sta=4995.3,4999.3
Exp/Cntr=0.3,0.1

Type RM Length L Ch R = 1,6500,500,500,500
BEGIN DESCRIPTION:
SANFERNANDO075 13.0
END DESCRIPTION:
XS GIS Cut Line= 3
      2804205.69     10233303.14      2804166.22     10232366.27
      2804855.69     10230953.09
#Sta/Elev= 30
  4062.3 1127.76  4119.2 1126.22  4152.4 1125.29  4262.5 1118.81  4322.6 1116.80
  4412.6 1111.29  4573.0 1105.38  4853.0 1100.09  4953.1 1099.97  4983.1 1098.94
  4993.2 1097.66  4999.1 1095.38  5013.2 1095.12  5013.4 1094.62  5017.2 1095.12
  5032.2 1097.93  5054.7 1098.96  5172.9 1098.95  5404.1 1106.44  5629.1 1105.12
  5691.1 1106.08  5696.6 1107.12  5736.1 1106.78  5882.5 1109.17  5944.5 1108.06
  5972.6 1108.91  6147.2 1107.01  6214.8 1107.30  6372.1 1111.77  6572.4 1119.72
#Mann=5,-1,0
  4062.3    0.05       0  4119.2    0.12       0  4573.0    0.05       0
  5013.2    0.03       0  5017.2    0.05       0
Bank Sta=5013.2,5017.2
Exp/Cntr=0.3,0.1

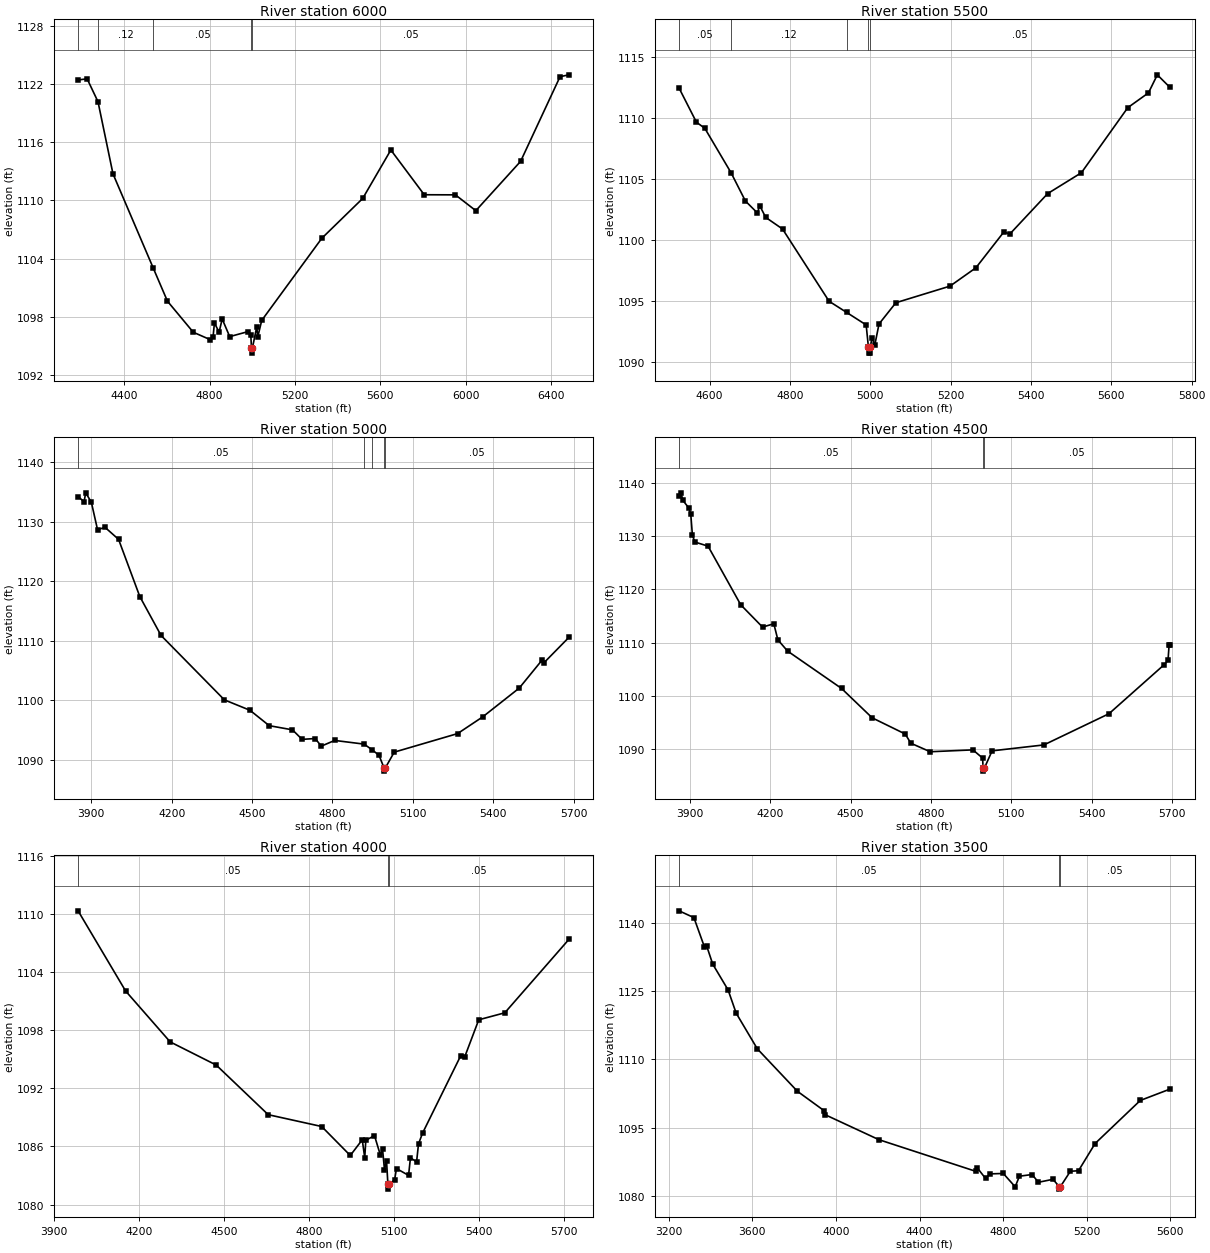
Type RM Length L Ch R = 1,6000,500,500,500
BEGIN DESCRIPTION:
SANFERNANDO075 12.0
END DESCRIPTION:
XS GIS Cut Line= 3
      2805055.69     10232953.12      2804534.07     10232325.35
      2804955.68     10230903.13
#Sta/Elev= 30
  4183.8 1122.40  4226.1 1122.52  4277.1 1120.16  4347.2 1112.74  4535.7 1103.04
  4602.4 1099.62  4723.5 1096.42  4801.6 1095.67  4816.0 1095.92  4822.5 1097.36
  4844.6 1096.44  4858.9 1097.79  4894.1 1095.97  4978.7 1096.48  4993.0 1096.09
  4996.2 1094.77  4996.5 1094.27  5000.2 1094.77  5020.6 1096.96  5025.8 1095.96
  5044.1 1097.64  5325.7 1106.10  5517.2 1110.20  5649.0 1115.19  5805.5 1110.58
  5951.5 1110.57  6047.1 1108.94  6256.9 1114.02  6441.7 1122.74  6483.4 1122.93
#Mann=5,-1,0
  4183.8    0.05       0  4277.1    0.12       0  4535.7    0.05       0
  4996.2    0.05       0  5000.2    0.05       0
Bank Sta=4996.2,5000.2
Exp/Cntr=0.3,0.1

Type RM Length L Ch R = 1,5500,500,500,500
BEGIN DESCRIPTION:
SANFERNANDO075 11.0
END DESCRIPTION:
XS GIS Cut Line= 3
      2805255.67     10232753.10      2804981.93     10232363.93
      2804755.67     10231653.07
#Sta/Elev= 30
  4524.2 1112.44  4567.3 1109.65  4588.2 1109.15  4653.5 1105.51  4689.3 1103.19
  4718.9 1102.22  4725.0 1102.80  4739.8 1101.85  4781.6 1100.90  4897.5 1094.98
  4941.0 1094.07  4989.8 1093.04  4995.4 1091.23  4995.7 1090.73  4999.2 1090.73
  4999.4 1091.23  5005.1 1091.96  5011.4 1091.41  5021.8 1093.12  5063.8 1094.86
  5198.5 1096.22  5262.9 1097.72  5332.6 1100.66  5347.2 1100.48  5441.6 1103.80
  5525.6 1105.51  5641.0 1110.84  5692.4 1112.05  5714.5 1113.53  5746.0 1112.50
#Mann=5,-1,0
  4524.2    0.05       0  4653.5    0.12       0  4941.0    0.05       0
  4995.4    0.05       0  4999.4    0.05       0
Bank Sta=4995.4,4999.4
Exp/Cntr=0.3,0.1

Type RM Length L Ch R = 1,5000,500,500,500
BEGIN DESCRIPTION:
SANFERNANDO075 10.0
END DESCRIPTION:
XS GIS Cut Line= 3
      2806305.66     10232753.09      2805357.37     10232104.29
      2804805.71     10231703.13
#Sta/Elev= 30
  3851.0 1134.26  3873.3 1133.39  3879.4 1134.89  3900.4 1133.32  3923.7 1128.67
  3951.2 1129.10  4002.0 1127.07  4081.2 1117.46  4160.4 1110.92  4396.7 1100.09
  4492.2 1098.34  4564.0 1095.75  4650.7 1095.05  4686.6 1093.45  4735.5 1093.59
  4758.3 1092.31  4808.2 1093.27  4917.9 1092.65  4948.6 1091.67  4973.6 1090.77
  4992.6 1088.61  4992.9 1088.11  4996.6 1088.61  5030.3 1091.30  5266.7 1094.42
  5360.7 1097.24  5496.7 1102.07  5582.8 1106.83  5589.0 1106.33  5682.1 1110.60
#Mann=5,-1,0
  3851.0    0.05       0  4917.9    0.12       0  4948.6    0.05       0
  4992.6    0.03       0  4996.6    0.05       0
Bank Sta=4992.6,4996.6
Exp/Cntr=0.3,0.1

Type RM Length L Ch R = 1,4500,500,500,500
BEGIN DESCRIPTION:
SANFERNANDO075 9.0
END DESCRIPTION:
XS GIS Cut Line= 3
      2806305.69     10232703.12      2805676.25     10231752.64
      2805255.68     10231203.10
#Sta/Elev= 30
  3860.0 1137.46  3867.5 1138.14  3873.5 1136.76  3896.0 1135.31  3903.6 1134.11
  3909.6 1130.21  3918.7 1128.90  3968.0 1128.13  4090.1 1117.11  4171.4 1112.93
  4213.5 1113.55  4228.6 1110.54  4264.7 1108.43  4466.2 1101.41  4580.5 1095.89
  4703.9 1092.85  4724.9 1091.12  4797.1 1089.52  4956.6 1089.87  4992.7 1088.33
  4994.7 1086.38  4995.0 1085.88  4998.7 1086.38  5028.2 1089.69  5221.4 1090.80
  5464.4 1096.66  5670.2 1105.86  5684.7 1106.69  5688.8 1109.58  5692.0 1109.58
#Mann=3,-1,0
  3860.0    0.05       0  4994.7    0.03       0  4998.7    0.05       0
Bank Sta=4994.7,4998.7
Exp/Cntr=0.3,0.1

Type RM Length L Ch R = 1,4000,500,500,500
BEGIN DESCRIPTION:
SANFERNANDO075 8.0
END DESCRIPTION:
XS GIS Cut Line= 3
      2806255.67     10232353.07      2805930.50     10231390.94
      2805405.70     10230903.13
#Sta/Elev= 30
  3984.4 1110.31  4152.1 1102.04  4309.3 1096.79  4471.8 1094.40  4655.3 1089.28
  4844.0 1088.06  4944.9 1085.07  4987.1 1086.69  4995.9 1084.84  4999.7 1086.64
  5030.3 1087.12  5051.3 1085.09  5058.6 1085.78  5065.5 1083.62  5072.8 1084.54
  5077.6 1082.10  5077.9 1081.60  5081.6 1082.10  5101.1 1082.55  5108.0 1083.72
  5150.5 1083.02  5157.3 1084.84  5178.8 1084.40  5185.6 1086.26  5199.8 1087.37
  5334.2 1095.34  5348.4 1095.22  5398.2 1099.07  5490.1 1099.79  5716.5 1107.37
#Mann=3,-1,0
  3984.4    0.05       0  5077.6    0.03       0  5081.6    0.05       0
Bank Sta=5077.6,5081.6
Exp/Cntr=0.3,0.1

Type RM Length L Ch R = 1,3500,500,500,500
BEGIN DESCRIPTION:
SANFERNANDO075 7.0
END DESCRIPTION:
XS GIS Cut Line= 3
      2806405.69     10232753.15      2806140.32     10231022.68
      2805605.64     10230753.09
#Sta/Elev= 30
  3249.3 1142.56  3320.2 1141.07  3370.7 1134.63  3380.9 1134.92  3410.2 1130.89
  3483.7 1125.24  3522.5 1120.14  3623.7 1112.33  3815.9 1103.02  3942.2 1098.82
  3947.4 1097.92  4205.7 1092.43  4669.3 1085.50  4675.8 1086.29  4716.3 1083.93
  4737.6 1084.94  4801.0 1085.03  4857.9 1082.11  4878.2 1084.43  4938.9 1084.80
  4969.2 1083.10  5038.8 1083.75  5069.8 1082.10  5070.0 1081.60  5073.8 1082.10
  5122.0 1085.51  5161.0 1085.63  5240.4 1091.59  5456.6 1101.02  5598.8 1103.51
#Mann=3,-1,0
  3249.3    0.05       0  5069.8    0.03       0  5073.8    0.05       0
Bank Sta=5069.8,5073.8
Exp/Cntr=0.3,0.1

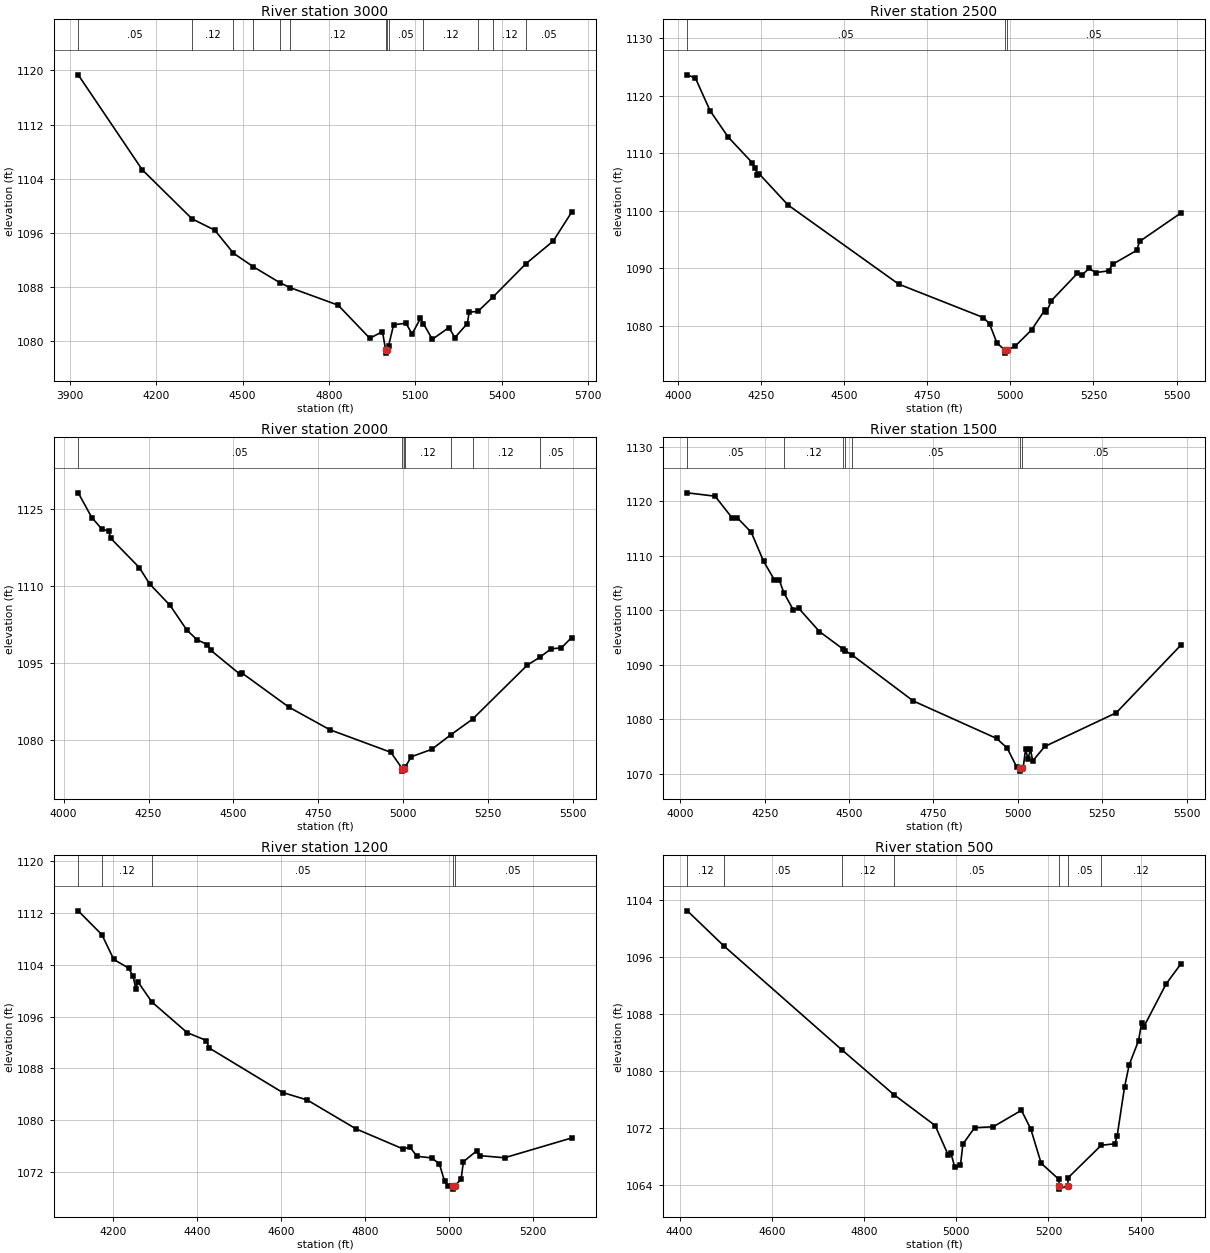
Type RM Length L Ch R = 1,3000,500,500,500
BEGIN DESCRIPTION:
SANFERNANDO075 6.0
END DESCRIPTION:
XS GIS Cut Line= 3
      2807055.68     10232153.11      2806553.97     10231205.99
      2806955.66     10230703.14
#Sta/Elev= 30
  3928.2 1119.33  4150.7 1105.33  4323.8 1098.09  4403.3 1096.40  4467.9 1093.01
  4536.1 1091.04  4629.3 1088.66  4665.2 1087.93  4832.0 1085.34  4942.0 1080.46
  4986.0 1081.45  4996.8 1078.77  4997.0 1078.27  5000.8 1078.77  5007.0 1079.30
  5024.8 1082.46  5067.7 1082.68  5088.9 1081.09  5117.7 1083.38  5128.6 1082.61
  5159.3 1080.31  5217.0 1082.04  5237.8 1080.56  5281.0 1082.63  5287.4 1084.31
  5317.9 1084.43  5371.7 1086.61  5485.2 1091.48  5579.6 1094.80  5643.6 1099.06
#Mann=13,-1,0
  3928.2    0.05       0  4323.8    0.12       0  4467.9    0.05       0
  4536.1    0.12       0  4629.3    0.05       0  4665.2    0.12       0
  4996.8    0.07       0  5000.8    0.12       0  5007.0    0.05       0
  5128.6    0.12       0  5317.9    0.05       0  5371.7    0.12       0
  5485.2    0.05       0
Bank Sta=4996.8,5000.8
Exp/Cntr=0.3,0.1

Type RM Length L Ch R = 1,2500,500,500,500
BEGIN DESCRIPTION:
SANFERNANDO075 5.0
END DESCRIPTION:
XS GIS Cut Line= 3
      2807205.69     10232153.12      2806997.98     10231204.29
      2807105.68     10230703.14
#Sta/Elev= 30
  4028.7 1123.67  4053.2 1123.08  4097.1 1117.43  4151.6 1112.84  4223.2 1108.42
  4233.4 1107.49  4238.9 1106.17  4244.0 1106.49  4331.7 1101.02  4664.3 1087.27
  4919.3 1081.45  4937.6 1080.35  4960.3 1076.97  4984.6 1075.77  4984.8 1075.27
  4988.6 1075.77  5014.7 1076.48  5064.1 1079.32  5103.2 1082.71  5108.3 1082.35
  5123.9 1084.42  5202.0 1089.16  5216.0 1088.85  5236.5 1090.00  5256.9 1089.28
  5295.6 1089.58  5308.1 1090.74  5379.7 1093.12  5389.2 1094.71  5512.6 1099.62
#Mann=3,-1,0
  4028.7    0.05       0  4984.6    0.03       0  4988.6    0.05       0
Bank Sta=4984.6,4988.6
Exp/Cntr=0.3,0.1

Type RM Length L Ch R = 1,2000,500,500,500
BEGIN DESCRIPTION:
SANFERNANDO075 4.0
END DESCRIPTION:
XS GIS Cut Line= 3
      2807505.68     10232103.09      2807455.56     10231147.31
      2807405.68     10230653.12
#Sta/Elev= 30
  4042.9 1128.10  4082.9 1123.30  4113.0 1121.03  4133.0 1120.65  4138.2 1119.30
  4223.1 1113.56  4253.2 1110.40  4313.3 1106.24  4363.3 1101.40  4393.4 1099.52
  4423.4 1098.61  4433.4 1097.50  4519.4 1092.84  4524.4 1093.12  4663.7 1086.44
  4783.9 1082.06  4964.1 1077.66  4997.5 1074.50  4997.8 1074.00  5001.6 1074.50
  5006.5 1074.81  5024.3 1076.79  5084.6 1078.24  5139.9 1081.02  5204.9 1084.11
  5366.0 1094.60  5403.3 1096.15  5436.4 1097.78  5466.6 1097.96  5496.7 1099.97
#Mann=7,-1,0
  4042.9    0.05       0  4997.5    0.05       0  5001.6    0.05       0
  5006.5    0.12       0  5139.9    0.05       0  5204.9    0.12       0
  5403.3    0.05       0
Bank Sta=4997.5,5001.6
Exp/Cntr=0.3,0.1

Type RM Length L Ch R = 1,1500,300,300,300
BEGIN DESCRIPTION:
SANFERNANDO075 3.0
END DESCRIPTION:
XS GIS Cut Line= 3
      2807705.70     10232003.07      2807939.31     10231052.14
      2807605.71     10230703.14
#Sta/Elev= 30
  4020.8 1121.51  4103.1 1120.89  4154.6 1116.82  4168.8 1116.93  4210.3 1114.26
  4246.7 1108.96  4278.2 1105.59  4293.4 1105.45  4307.1 1103.12  4335.0 1100.02
  4350.3 1100.36  4412.1 1096.06  4482.6 1092.82  4487.9 1092.53  4509.3 1091.74
  4690.1 1083.32  4937.2 1076.44  4968.5 1074.67  4996.9 1071.18  5007.0 1070.94
  5007.2 1070.44  5011.1 1070.94  5015.9 1071.06  5023.2 1074.53  5030.1 1072.59
  5037.3 1074.44  5044.3 1072.32  5079.8 1074.96  5291.8 1081.15  5482.8 1093.54
#Mann=7,-1,0
  4020.8    0.05       0  4307.1    0.12       0  4482.6    0.05       0
  4487.9    0.12       0  4509.3    0.05       0  5007.0    0.05       0
  5011.1    0.05       0
Bank Sta=5007,5011.1
Exp/Cntr=0.3,0.1

Type RM Length L Ch R = 1,1200,700,700,700
BEGIN DESCRIPTION:
SANFERNANDO075 2.0
END DESCRIPTION:
XS GIS Cut Line= 3
      2807855.69     10231803.11      2808208.25     10230993.00
      2808330.68     10230728.13
#Sta/Elev= 30
  4116.5 1112.36  4173.0 1108.66  4201.2 1104.84  4236.5 1103.51  4247.4 1102.22
  4253.6 1100.32  4259.0 1101.36  4291.9 1098.27  4376.2 1093.52  4421.9 1092.31
  4428.5 1091.15  4603.5 1084.27  4661.8 1083.12  4778.4 1078.64  4890.8 1075.53
  4906.5 1075.83  4923.5 1074.41  4958.8 1074.15  4976.8 1073.23  4989.0 1070.59
  4997.2 1069.85  5009.0 1069.83  5009.3 1069.33  5013.2 1069.83  5028.5 1070.84
  5034.0 1073.57  5066.0 1075.26  5074.4 1074.50  5132.1 1074.18  5291.8 1077.24
#Mann=5,-1,0
  4116.5    0.05       0  4173.0    0.12       0  4291.9    0.05       0
  5009.0    0.03       0  5013.2    0.05       0
Bank Sta=5009,5013.2
Exp/Cntr=0.3,0.1

Type RM Length L Ch R = 1,500,0,0,0
BEGIN DESCRIPTION:
SANFERNANDO075 1.0
END DESCRIPTION:
XS GIS Cut Line= 3
      2808005.66     10231753.13      2808526.70     10231490.69
      2809005.66     10231403.12
#Sta/Elev= 30
  4416.6 1102.47  4495.8 1097.54  4751.3 1082.96  4864.3 1076.65  4954.1 1072.29
  4982.8 1068.10  4988.4 1068.42  4996.6 1066.44  5009.1 1066.71  5014.3 1069.67
  5039.6 1071.98  5080.3 1072.12  5141.3 1074.43  5161.6 1071.80  5184.1 1066.99
  5222.6 1064.72  5222.9 1063.85  5223.4 1063.35  5241.5 1063.85  5242.9 1064.97
  5314.5 1069.52  5343.7 1069.72  5348.8 1070.76  5364.9 1077.67  5375.1 1080.84
  5395.4 1084.22  5402.0 1086.73  5407.1 1086.21  5455.2 1092.20  5486.9 1094.98
#Mann=7,-1,0
  4416.6    0.12       0  4495.8    0.05       0  4751.3    0.12       0
  4864.3    0.05       0  5222.9    0.05       0  5241.5    0.05       0
  5314.5    0.12       0
Bank Sta=5222.9,5241.5
Exp/Cntr=0.3,0.1

Chan Stop Cuts=-1