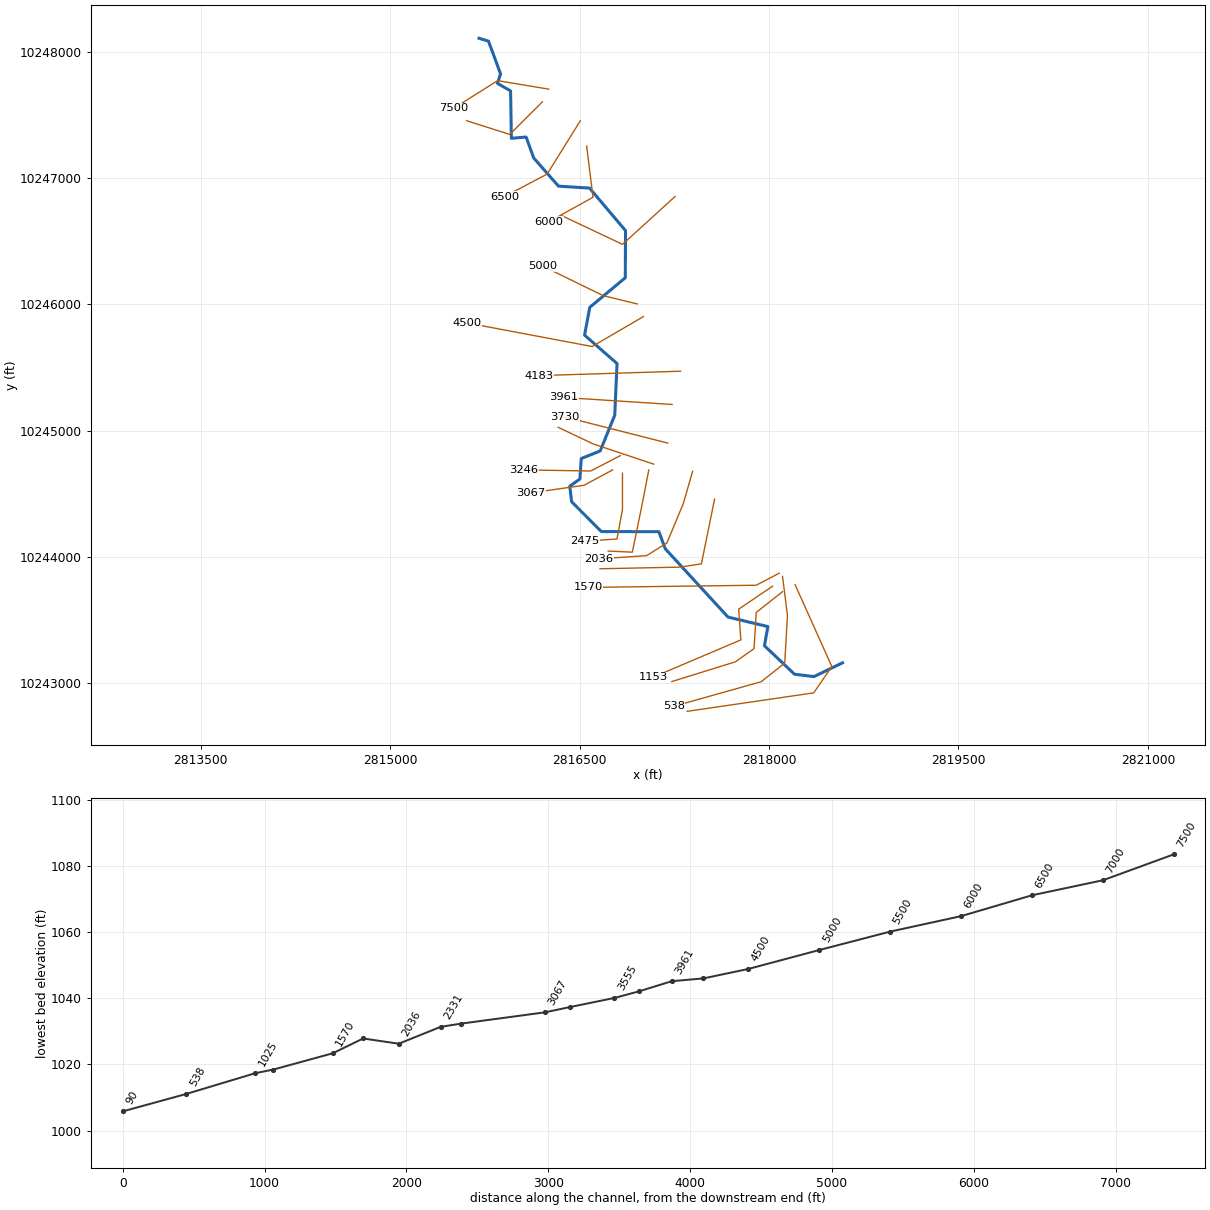
--- SANFERNANDO076.prj (project) ---

Proj Title=SANFERNANDO076 Base Level Engineering
Current Plan=p01
Default Exp/Contr=0.3,0.1
English Units
Geom File=g01
Flow File=f01
Plan File=p01
BEGIN DESCRIPTION:
SANFERNANDO076
END DESCRIPTION:

--- SANFERNANDO076.p01 (plan) ---

Plan Title=Multiple Run
Short Identifier=Multiple
Geom File=g01
Flow File=f01
Subcritical Flow
K Sum by GR= 0
Std Step Tol= 0.01
Critical Tol= 0.01
Num of Std Step Trials= 20
Max Error Tol= 0.3
Flow Tol Ratio= 0.001
Split Flow NTrial= 30
Split Flow Tol= 0.02
Split Flow Ratio= 0.02
Log Output Level= 0
Friction Slope Method= 1
Unsteady Friction Slope Method= 2
Unsteady Bridges Friction Slope Method= 1
Parabolic Critical Depth
Global Vel Dist=  1 , 1 , 1
Global Log Level= 0
CheckData=True
Encroach Param= -1, 0, 0, 0
BEGIN DESCRIPTION:
Multiple Run
END DESCRIPTION:

--- SANFERNANDO076.f01 (steady flow) ---

Flow Title=Multiple
Number of Profiles=7
Profile Names=10-year,25-year,50-year,1pct_min,100-year,1pct_plu,500-year
River Rch & RM= SANFERNANDO076,Reach-1,7500
     350     564     815     518    1098    2327    1553
Boundary for River Rch & Prof#=SANFERNANDO076,Reach-1,1
Up Type=0
Dn Type=3
Dn Slope=0.005
Boundary for River Rch & Prof#=SANFERNANDO076,Reach-1,2
Up Type=0
Dn Type=3
Dn Slope=0.005
Boundary for River Rch & Prof#=SANFERNANDO076,Reach-1,3
Up Type=0
Dn Type=3
Dn Slope=0.005
Boundary for River Rch & Prof#=SANFERNANDO076,Reach-1,4
Up Type=0
Dn Type=3
Dn Slope=0.005
Boundary for River Rch & Prof#=SANFERNANDO076,Reach-1,5
Up Type=0
Dn Type=3
Dn Slope=0.005
Boundary for River Rch & Prof#=SANFERNANDO076,Reach-1,6
Up Type=0
Dn Type=3
Dn Slope=0.005
Boundary for River Rch & Prof#=SANFERNANDO076,Reach-1,7
Up Type=0
Dn Type=3
Dn Slope=0.005

--- SANFERNANDO076.g01 (geometry) ---

Geom Title=Existing Conditions

River Reach=SANFERNANDO076,Reach-1
Reach XY= 30
      2815703.25     10248106.00      2815778.25     10248083.00
      2815874.00     10247824.00      2815849.00     10247749.00
      2815953.25     10247689.00      2815959.50     10247314.00
      2816076.25     10247324.00      2816136.50     10247158.00
      2816332.75     10246935.00      2816578.25     10246920.00
      2816863.50     10246583.00      2816861.50     10246210.00
      2816580.25     10245976.00      2816539.00     10245756.00
      2816796.25     10245531.00      2816778.00     10245122.00
      2816663.00     10244839.00      2816513.00     10244779.00
      2816502.00     10244617.00      2816422.00     10244560.00
      2816436.50     10244437.00      2816672.25     10244201.00
      2817127.50     10244200.00      2817178.00     10244065.00
      2817675.25     10243524.00      2817990.50     10243449.00
      2817963.50     10243297.00      2818201.25     10243072.00
      2818355.25     10243053.00      2818581.75     10243162.00

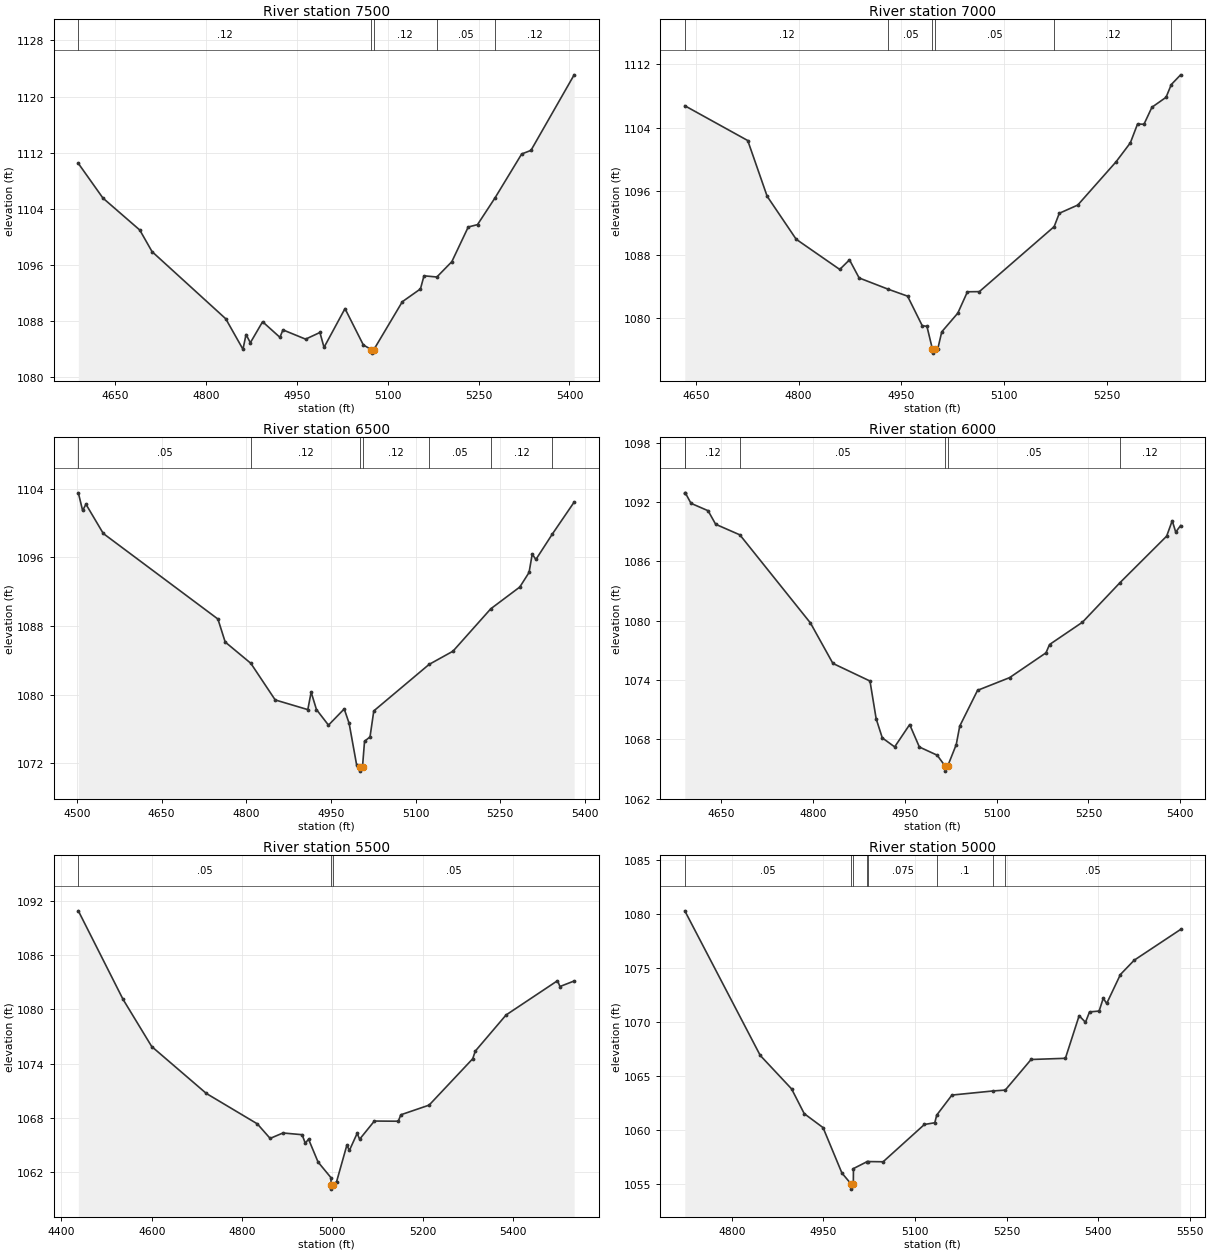
Type RM Length L Ch R = 1,7500,500,500,500
BEGIN DESCRIPTION:
SANFERNANDO076 15.0
END DESCRIPTION:
XS GIS Cut Line= 3
      2816255.71     10247703.11      2815850.66     10247770.36
      2815505.67     10247553.10
#Sta/Elev= 30
  4589.4 1110.48  4630.0 1105.54  4690.8 1100.99  4711.1 1097.91  4832.7 1088.35
  4861.1 1084.01  4866.2 1086.11  4873.3 1084.94  4893.5 1087.93  4922.1 1085.71
  4927.1 1086.77  4964.5 1085.45  4988.1 1086.40  4994.9 1084.28  5029.5 1089.80
  5059.8 1084.62  5073.1 1083.96  5073.3 1083.46  5077.1 1083.96  5124.1 1090.78
  5154.0 1092.60  5159.9 1094.47  5181.1 1094.30  5205.8 1096.48  5232.9 1101.42
  5248.2 1101.76  5277.1 1105.57  5321.1 1111.82  5336.4 1112.33  5407.7 1123.09
#Mann=5,-1,0
  4589.4    0.12       0  5073.1    0.07       0  5077.1    0.12       0
  5181.1    0.05       0  5277.1    0.12       0
Bank Sta=5073.1,5077.1
Exp/Cntr=0.3,0.1

Type RM Length L Ch R = 1,7000,500,500,500
BEGIN DESCRIPTION:
SANFERNANDO076 14.0
END DESCRIPTION:
XS GIS Cut Line= 3
      2816205.66     10247603.09      2815946.53     10247344.48
      2815605.72     10247453.10
#Sta/Elev= 30
  4633.9 1106.76  4725.8 1102.38  4754.1 1095.37  4796.5 1089.96  4860.1 1086.16
  4874.3 1087.37  4888.4 1085.09  4930.9 1083.67  4959.1 1082.80  4980.4 1079.10
  4987.4 1078.99  4995.4 1076.13  4995.7 1075.63  4999.4 1076.13  5003.1 1076.13
  5009.0 1078.31  5032.4 1080.66  5046.5 1083.35  5063.9 1083.37  5173.1 1091.55
  5180.6 1093.23  5207.5 1094.26  5263.3 1099.69  5284.3 1102.09  5294.8 1104.46
  5304.2 1104.43  5315.8 1106.57  5336.4 1107.82  5344.1 1109.43  5357.7 1110.65
#Mann=6,-1,0
  4633.9    0.12       0  4930.9    0.05       0  4995.4    0.05       0
  4999.4    0.05       0  5173.1    0.12       0  5344.1    0.05       0
Bank Sta=4995.4,4999.4
Exp/Cntr=0.3,0.1

Type RM Length L Ch R = 1,6500,500,500,500
BEGIN DESCRIPTION:
SANFERNANDO076 13.0
END DESCRIPTION:
XS GIS Cut Line= 3
      2816505.67     10247453.09      2816242.79     10247030.71
      2815905.71     10246853.13
#Sta/Elev= 30
  4502.5 1103.53  4510.1 1101.47  4516.0 1102.20  4546.7 1098.79  4749.8 1088.82
  4762.7 1086.14  4808.1 1083.66  4851.3 1079.39  4909.1 1078.26  4915.0 1080.30
  4924.4 1078.27  4945.7 1076.45  4973.6 1078.34  4982.3 1076.66  4995.6 1071.81
  5002.0 1071.59  5002.2 1071.09  5006.0 1071.59  5009.6 1074.57  5019.3 1075.08
  5026.0 1078.11  5124.0 1083.53  5166.3 1085.07  5233.2 1090.01  5284.7 1092.55
  5301.1 1094.25  5306.7 1096.38  5313.2 1095.76  5342.3 1098.72  5381.0 1102.45
#Mann=7,-1,0
  4502.5    0.05       0  4808.1    0.12       0  5002.0    0.07       0
  5006.0    0.12       0  5124.0    0.05       0  5233.2    0.12       0
  5342.3    0.05       0
Bank Sta=5002,5006
Exp/Cntr=0.3,0.1

Type RM Length L Ch R = 1,6000,500,500,500
BEGIN DESCRIPTION:
SANFERNANDO076 12.0
END DESCRIPTION:
XS GIS Cut Line= 3
      2816555.69     10247253.10      2816605.92     10246847.20
      2816255.70     10246653.12
#Sta/Elev= 30
  4591.0 1092.93  4591.8 1092.93  4601.1 1091.87  4629.0 1091.12  4641.4 1089.75
  4680.9 1088.68  4796.1 1079.77  4832.8 1075.68  4893.3 1073.90  4903.4 1070.08
  4913.4 1068.15  4933.6 1067.24  4958.1 1069.50  4973.9 1067.23  5003.0 1066.40
  5016.1 1065.29  5016.3 1064.79  5020.1 1065.29  5034.1 1067.47  5039.8 1069.34
  5068.9 1072.96  5121.1 1074.24  5180.6 1076.75  5186.4 1077.59  5240.2 1079.85
  5301.3 1083.84  5377.6 1088.55  5386.7 1090.11  5392.4 1088.96  5400.4 1089.62
#Mann=6,-1,0
  4591.0    0.05       0  4591.8    0.12       0  4680.9    0.05       0
  5016.1    0.03       0  5020.1    0.05       0  5301.3    0.12       0
Bank Sta=5016.1,5020.1
Exp/Cntr=0.3,0.1

Type RM Length L Ch R = 1,5500,500,500,500
BEGIN DESCRIPTION:
SANFERNANDO076 11.0
END DESCRIPTION:
XS GIS Cut Line= 3
      2817255.70     10246853.12      2816839.65     10246474.42
      2816355.66     10246703.12
#Sta/Elev= 30
  4437.4 1090.90  4536.4 1081.11  4599.9 1075.89  4720.9 1070.70  4833.7 1067.34
  4862.1 1065.73  4890.5 1066.33  4933.0 1066.14  4939.8 1065.20  4947.2 1065.64
  4968.2 1063.12  4996.6 1061.40  4997.3 1060.62  4997.5 1060.12  5001.3 1060.62
  5009.3 1060.95  5032.0 1064.98  5037.6 1064.40  5054.8 1066.29  5060.3 1065.64
  5092.9 1067.65  5145.9 1067.63  5151.4 1068.34  5214.1 1069.41  5310.7 1074.54
  5316.3 1075.38  5384.5 1079.38  5498.4 1083.17  5503.9 1082.53  5535.3 1083.14
#Mann=3,-1,0
  4437.4    0.05       0  4997.3    0.05       0  5001.3    0.05       0
Bank Sta=4997.3,5001.3
Exp/Cntr=0.3,0.1

Type RM Length L Ch R = 1,5000,500,500,500
BEGIN DESCRIPTION:
SANFERNANDO076 10.0
END DESCRIPTION:
XS GIS Cut Line= 3
      2816955.67     10246003.12      2816686.49     10246068.50
      2816205.68     10246303.11
#Sta/Elev= 30
  4723.0 1080.29  4846.5 1066.92  4897.9 1063.82  4918.6 1061.53  4949.4 1060.24
  4980.3 1056.04  4995.0 1055.05  4995.3 1054.55  4999.0 1055.05  4999.2 1056.45
  5021.8 1057.10  5023.3 1057.10  5047.8 1057.08  5115.4 1060.53  5132.4 1060.69
  5135.6 1061.40  5160.5 1063.25  5227.7 1063.63  5247.8 1063.71  5290.1 1066.54
  5346.3 1066.65  5368.8 1070.59  5379.2 1069.98  5385.8 1070.94  5401.5 1071.02
  5408.3 1072.21  5413.9 1071.72  5436.4 1074.40  5458.9 1075.72  5535.0 1078.57
#Mann=8,-1,0
  4723.0    0.05       0  4995.0    0.03       0  4999.0    0.05       0
  5021.8     0.1       0  5023.3   0.075       0  5135.6     0.1       0
  5227.7   0.075       0  5247.8    0.05       0
Bank Sta=4995,4999
Exp/Cntr=0.3,0.1

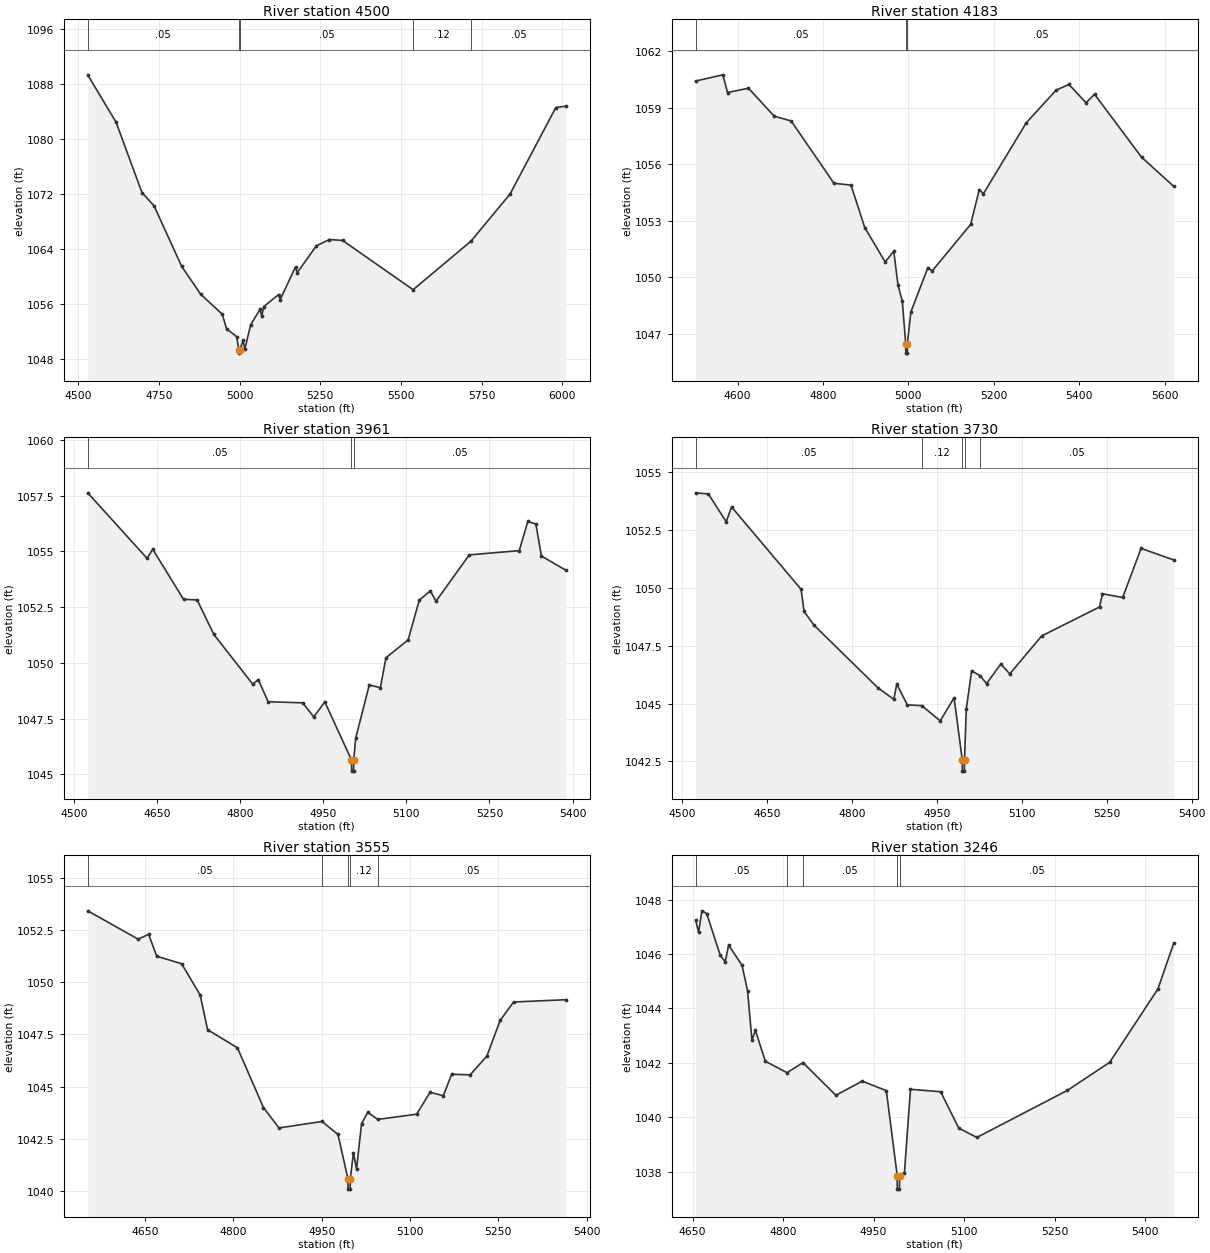
Type RM Length L Ch R = 1,4500,317,317,317
BEGIN DESCRIPTION:
SANFERNANDO076 9.0
END DESCRIPTION:
XS GIS Cut Line= 3
      2817005.68     10245903.11      2816599.25     10245665.69
      2815605.67     10245853.11
#Sta/Elev= 30
  4529.3 1089.34  4617.3 1082.43  4697.5 1072.20  4734.7 1070.29  4820.7 1061.45
  4879.4 1057.41  4946.2 1054.50  4959.6 1052.38  4991.0 1051.23  4997.2 1049.34
  4997.4 1048.84  5001.2 1049.34  5010.9 1050.74  5016.0 1049.39  5034.2 1052.96
  5063.3 1055.21  5068.4 1054.22  5074.9 1055.61  5120.8 1057.37  5125.9 1056.63
  5173.2 1061.40  5178.3 1060.53  5237.7 1064.45  5278.0 1065.37  5319.1 1065.24
  5537.6 1058.07  5717.0 1065.14  5838.1 1072.00  5979.8 1084.57  6011.1 1084.78
#Mann=5,-1,0
  4529.3    0.05       0  4997.2    0.03       0  5001.2    0.05       0
  5537.6    0.12       0  5717.0    0.05       0
Bank Sta=4997.2,5001.2
Exp/Cntr=0.3,0.1

Type RM Length L Ch R = 1,4183,222,222,222
BEGIN DESCRIPTION:
Mapping XS 6ceebdab
END DESCRIPTION:
XS GIS Cut Line= 2
      2817299.46     10245470.30      2816180.19     10245435.59
#Sta/Elev= 30
  4501.9 1060.41  4565.7 1060.74  4576.6 1059.80  4625.7 1060.03  4685.8 1058.55
  4725.8 1058.29  4825.8 1054.99  4865.8 1054.89  4898.0 1052.64  4945.9 1050.81
  4965.9 1051.39  4975.9 1049.58  4985.9 1048.74  4993.9 1046.48  4994.2 1045.98
  4997.7 1045.98  4997.9 1046.48  5005.9 1048.16  5045.9 1050.52  5055.9 1050.34
  5146.0 1052.81  5166.0 1054.64  5176.0 1054.44  5276.0 1058.19  5346.1 1059.93
  5376.1 1060.23  5416.1 1059.26  5436.1 1059.71  5546.2 1056.37  5621.7 1054.82
#Mann=3,-1,0
  4501.9    0.05       0  4993.9    0.03       0  4997.9    0.05       0
Bank Sta=4993.9,4997.9
Exp/Cntr=0.3,0.1

Type RM Length L Ch R = 1,3961,231,231,231
BEGIN DESCRIPTION:
Mapping XS 2e3e037a
END DESCRIPTION:
XS GIS Cut Line= 2
      2817232.73     10245206.95      2816371.62     10245262.50
#Sta/Elev= 30
  4525.2 1057.62  4632.5 1054.68  4642.5 1055.09  4698.1 1052.85  4722.7 1052.82
  4752.7 1051.28  4822.9 1049.05  4832.9 1049.25  4850.9 1048.26  4913.1 1048.21
  4933.1 1047.58  4953.1 1048.25  5001.2 1045.65  5001.5 1045.15  5005.0 1045.15
  5005.2 1045.65  5008.8 1046.63  5033.3 1049.01  5053.3 1048.89  5063.4 1050.23
  5103.4 1051.03  5123.5 1052.81  5143.5 1053.23  5153.6 1052.76  5213.7 1054.84
  5303.9 1055.03  5319.4 1056.34  5333.9 1056.22  5343.9 1054.79  5388.1 1054.15
#Mann=3,-1,0
  4525.2    0.05       0  5001.2    0.03       0  5005.2    0.05       0
Bank Sta=5001.2,5005.2
Exp/Cntr=0.3,0.1

Type RM Length L Ch R = 1,3730,175,175,175
BEGIN DESCRIPTION:
Mapping XS e4da2b24
END DESCRIPTION:
XS GIS Cut Line= 2
      2817198.02     10244901.39      2816379.66     10245109.45
#Sta/Elev= 30
  4524.1 1054.10  4546.7 1054.05  4578.1 1052.85  4587.6 1053.49  4710.4 1049.93
  4715.6 1048.98  4732.9 1048.39  4846.4 1045.67  4874.1 1045.18  4879.3 1045.84
  4898.0 1044.94  4923.5 1044.91  4956.0 1044.25  4980.5 1045.25  4994.9 1042.58
  4995.2 1042.08  4998.7 1042.08  4998.9 1042.58  5002.1 1044.77  5011.5 1046.41
  5026.5 1046.20  5037.8 1045.86  5063.1 1046.71  5078.8 1046.28  5135.3 1047.92
  5237.3 1049.17  5242.5 1049.74  5278.2 1049.58  5310.7 1051.70  5368.5 1051.20
#Mann=5,-1,0
  4524.1    0.05       0  4923.5    0.12       0  4994.9    0.07       0
  4998.9    0.12       0  5026.5    0.05       0
Bank Sta=4994.9,4998.9
Exp/Cntr=0.3,0.1

Type RM Length L Ch R = 1,3555,309,309,309
BEGIN DESCRIPTION:
Mapping XS 57624a77
END DESCRIPTION:
XS GIS Cut Line= 3
      2817086.89     10244734.73      2816607.74     10244894.45
      2816330.32     10245026.22
#Sta/Elev= 30
  4552.6 1053.44  4638.2 1052.08  4656.1 1052.31  4669.8 1051.26  4712.0 1050.90
  4743.6 1049.40  4756.2 1047.73  4806.9 1046.86  4851.1 1043.99  4877.5 1043.01
  4950.4 1043.32  4977.6 1042.70  4994.6 1040.57  4994.8 1040.07  4998.3 1040.07
  4998.6 1040.57  5003.9 1041.82  5009.2 1041.04  5017.7 1043.21  5028.2 1043.76
  5045.2 1043.42  5111.3 1043.67  5134.0 1044.72  5156.7 1044.56  5170.7 1045.59
  5202.2 1045.56  5230.5 1046.46  5253.2 1048.18  5275.9 1049.06  5364.8 1049.17
#Mann=5,-1,0
  4552.6    0.05       0  4950.4    0.12       0  4994.6    0.07       0
  4998.6    0.12       0  5045.2    0.05       0
Bank Sta=4994.6,4998.6
Exp/Cntr=0.3,0.1

Type RM Length L Ch R = 1,3246,179,179,179
BEGIN DESCRIPTION:
Mapping XS fd07ffee
END DESCRIPTION:
XS GIS Cut Line= 3
      2816822.00     10244801.90      2816587.62     10244680.37
      2816059.41     10244689.03
#Sta/Elev= 30
  4655.1 1047.25  4660.0 1046.81  4665.6 1047.59  4673.5 1047.49  4696.0 1045.95
  4704.2 1045.72  4709.8 1046.33  4732.0 1045.59  4741.1 1044.66  4748.5 1042.83
  4754.1 1043.20  4770.6 1042.06  4806.6 1041.64  4832.9 1042.01  4887.5 1040.81
  4931.1 1041.33  4971.1 1040.98  4989.1 1037.86  4989.3 1037.36  4992.8 1037.36
  4993.1 1037.86  5001.1 1037.97  5011.1 1041.03  5061.1 1040.94  5091.1 1039.60
  5121.1 1039.26  5271.1 1040.99  5341.1 1042.02  5421.1 1044.72  5447.4 1046.41
#Mann=5,-1,0
  4655.1    0.05       0  4806.6    0.12       0  4832.9    0.05       0
  4989.1    0.05       0  4993.1    0.05       0
Bank Sta=4989.1,4993.1
Exp/Cntr=0.3,0.1

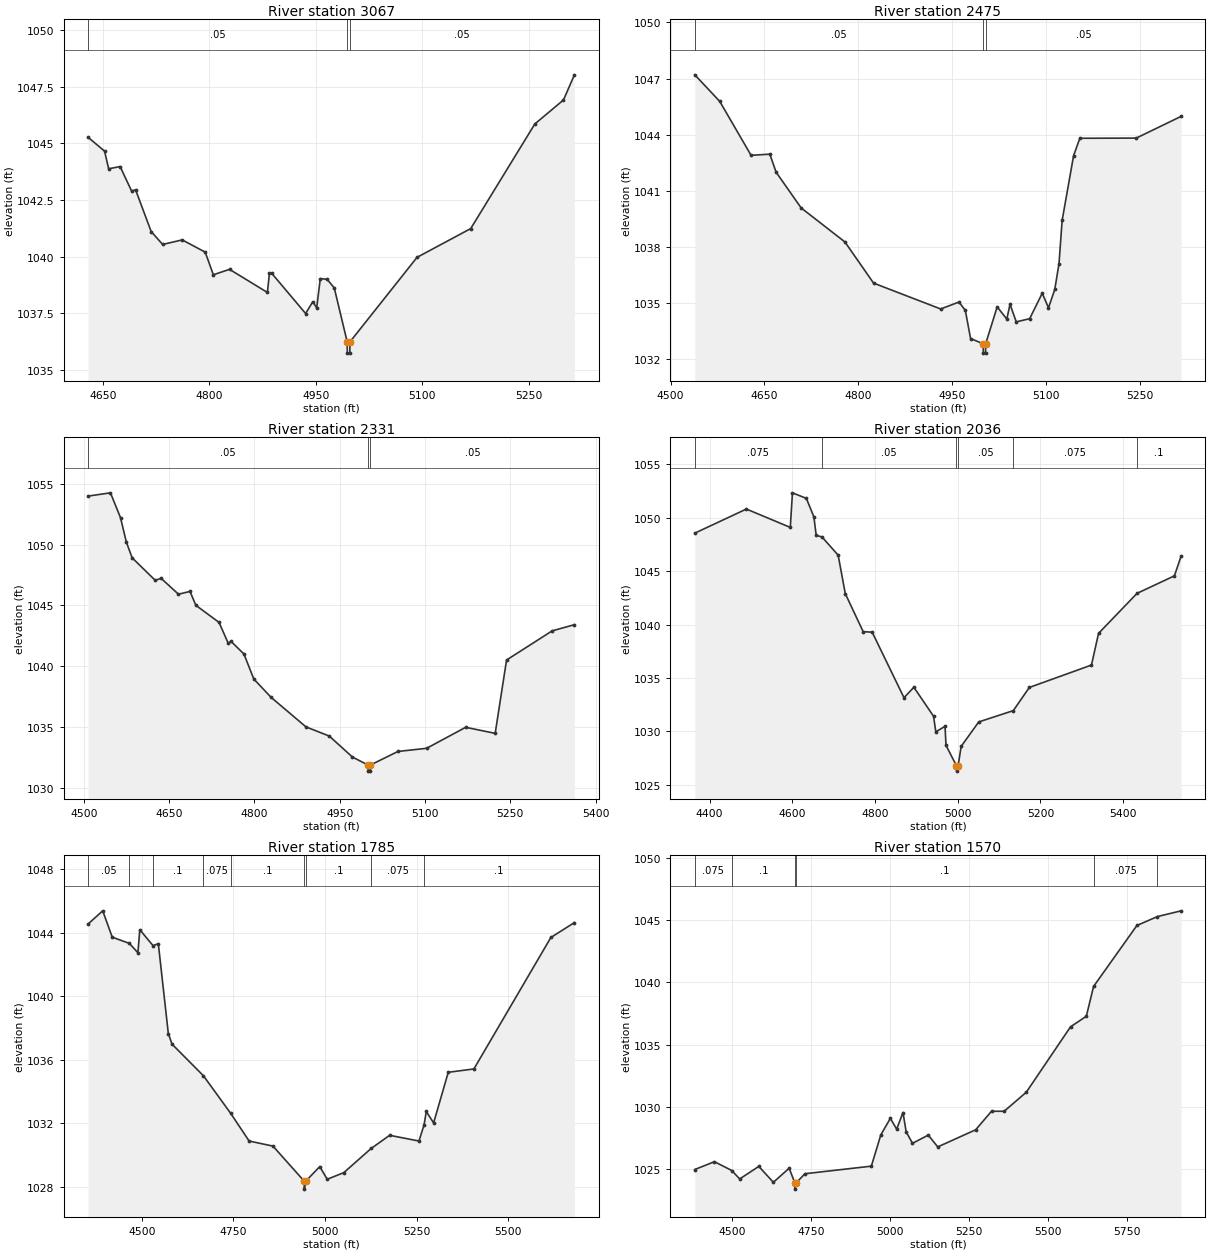
Type RM Length L Ch R = 1,3067,592,592,592
BEGIN DESCRIPTION:
Mapping XS 4c25f4ea
END DESCRIPTION:
XS GIS Cut Line= 3
      2816761.21     10244689.04      2816535.54     10244567.52
      2816110.46     10244506.80
#Sta/Elev= 30
  4629.0 1045.27  4652.2 1044.66  4658.0 1043.88  4674.1 1043.98  4690.3 1042.90
  4696.0 1042.95  4717.9 1041.11  4734.1 1040.54  4761.7 1040.74  4794.1 1040.20
  4805.6 1039.20  4828.4 1039.44  4881.8 1038.42  4884.7 1039.27  4887.8 1039.27
  4935.7 1037.49  4945.8 1038.01  4951.3 1037.74  4956.4 1039.03  4966.0 1039.00
  4976.1 1038.62  4994.3 1036.24  4994.5 1035.74  4998.0 1035.74  4998.3 1036.24
  5092.8 1039.97  5168.5 1041.24  5258.9 1045.86  5299.3 1046.92  5314.7 1048.03
#Mann=3,-1,0
  4629.0    0.05       0  4994.3    0.05       0  4998.3    0.05       0
Bank Sta=4994.3,4998.3
Exp/Cntr=0.3,0.1

Type RM Length L Ch R = 1,2475,144,144,144
BEGIN DESCRIPTION:
Mapping XS 7fd61313
END DESCRIPTION:
XS GIS Cut Line= 4
      2816839.36     10244663.00      2816839.36     10244376.55
      2816795.96     10244142.17      2816544.26     10244124.82
#Sta/Elev= 30
  4538.8 1047.20  4578.7 1045.78  4628.7 1042.90  4658.7 1042.96  4668.7 1042.00
  4708.7 1040.09  4778.7 1038.27  4824.5 1036.07  4931.7 1034.69  4961.0 1035.06
  4971.1 1034.61  4979.5 1033.11  4999.6 1032.83  4999.9 1032.33  5003.4 1032.33
  5003.6 1032.83  5022.0 1034.80  5037.4 1034.15  5042.5 1034.94  5052.5 1034.00
  5073.9 1034.17  5094.0 1035.53  5104.0 1034.75  5114.0 1035.73  5120.8 1037.11
  5125.8 1039.42  5144.1 1042.88  5154.1 1043.81  5244.3 1043.82  5315.9 1044.98
#Mann=3,-1,0
  4538.8    0.05       0  4999.6    0.03       0  5003.6    0.05       0
Bank Sta=4999.6,5003.6
Exp/Cntr=0.3,0.1

Type RM Length L Ch R = 1,2331,295,295,295
BEGIN DESCRIPTION:
Mapping XS ed2f823d
END DESCRIPTION:
XS GIS Cut Line= 4
      2817047.70     10244689.08      2816995.61     10244419.95
      2816917.48     10244038.01      2816726.55     10244046.69
#Sta/Elev= 30
  4507.5 1054.00  4546.8 1054.27  4564.5 1052.22  4574.7 1050.22  4584.9 1048.92
  4625.6 1047.06  4635.8 1047.23  4666.4 1045.92  4686.7 1046.15  4696.9 1045.01
  4737.7 1043.60  4753.9 1041.88  4759.0 1042.03  4781.6 1040.99  4798.8 1038.94
  4829.4 1037.42  4890.7 1034.99  4931.5 1034.24  4972.3 1032.51  4999.8 1031.85
  5000.1 1031.35  5003.6 1031.35  5003.8 1031.85  5052.3 1032.97  5102.8 1033.23
  5171.4 1034.96  5223.3 1034.46  5243.3 1040.50  5323.4 1042.90  5362.6 1043.41
#Mann=3,-1,0
  4507.5    0.05       0  4999.8    0.03       0  5003.8    0.05       0
Bank Sta=4999.8,5003.8
Exp/Cntr=0.3,0.1

Type RM Length L Ch R = 1,2036,251,251,251
BEGIN DESCRIPTION:
Mapping XS a8e8cb8b
END DESCRIPTION:
XS GIS Cut Line= 5
      2817394.91     10244679.00      2817321.13     10244422.97
      2817190.93     10244110.47      2817030.33     10244010.64
      2816649.50     10243984.67
#Sta/Elev= 30
  4364.3 1048.56  4489.0 1050.82  4595.2 1049.10  4600.4 1052.34  4634.0 1051.82
  4652.3 1050.08  4657.8 1048.35  4671.7 1048.21  4710.9 1046.50  4728.1 1042.90
  4771.4 1039.33  4793.2 1039.28  4870.1 1033.14  4894.0 1034.12  4941.6 1031.40
  4947.0 1029.94  4969.3 1030.46  4971.7 1028.67  4997.0 1026.76  4997.3 1026.26
  5001.0 1026.76  5008.3 1028.58  5050.8 1030.87  5134.4 1031.93  5173.1 1034.10
  5323.4 1036.20  5340.5 1039.17  5433.6 1042.92  5523.9 1044.56  5540.1 1046.40
#Mann=6,-1,0
  4364.3   0.075       0  4671.7    0.05       0  4997.0    0.03       0
  5001.0    0.05       0  5134.4   0.075       0  5433.6     0.1       0
Bank Sta=4997,5001
Exp/Cntr=0.3,0.1

Type RM Length L Ch R = 1,1785,215,215,215
BEGIN DESCRIPTION:
Mapping XS dc8d1a7a
END DESCRIPTION:
XS GIS Cut Line= 4
      2817568.53     10244457.69      2817464.36     10243945.53
      2817290.75     10243919.49      2816661.38     10243906.47
#Sta/Elev= 30
  4353.3 1044.54  4393.2 1045.37  4419.2 1043.71  4465.9 1043.32  4489.3 1042.73
  4494.4 1044.18  4530.5 1043.18  4545.0 1043.30  4572.3 1037.64  4582.5 1036.97
  4668.2 1034.98  4742.7 1032.61  4792.9 1030.87  4858.0 1030.55  4943.4 1028.34
  4943.6 1027.84  4947.4 1028.34  4985.8 1029.26  5006.1 1028.46  5051.5 1028.88
  5126.0 1030.40  5176.6 1031.23  5256.6 1030.87  5270.5 1031.88  5276.6 1032.73
  5296.6 1032.01  5336.6 1035.20  5406.6 1035.41  5616.7 1043.69  5681.0 1044.63
#Mann=9,-1,0
  4353.3    0.05       0  4465.9   0.075       0  4530.5     0.1       0
  4668.2   0.075       0  4742.7     0.1       0  4943.4    0.07       0
  4947.4     0.1       0  5126.0   0.075       0  5270.5     0.1       0
Bank Sta=4943.4,4947.4
Exp/Cntr=0.3,0.1

Type RM Length L Ch R = 1,1570,417,417,417
BEGIN DESCRIPTION:
Mapping XS 5f237a83
END DESCRIPTION:
XS GIS Cut Line= 3
      2818080.70     10243871.76      2817898.39     10243776.26
      2816565.91     10243758.90
#Sta/Elev= 30
  4382.5 1024.94  4444.6 1025.57  4499.4 1024.86  4524.5 1024.18  4585.0 1025.19
  4631.0 1023.91  4681.0 1025.04  4699.0 1023.86  4699.3 1023.36  4703.0 1023.86
  4731.0 1024.60  4941.0 1025.21  4971.0 1027.73  5001.1 1029.06  5021.1 1028.19
  5041.1 1029.53  5051.1 1027.98  5071.1 1027.05  5121.1 1027.71  5151.1 1026.76
  5271.1 1028.14  5321.1 1029.63  5361.1 1029.63  5431.1 1031.16  5571.1 1036.43
  5621.1 1037.28  5644.0 1039.68  5781.1 1044.59  5846.2 1045.31  5920.9 1045.77
#Mann=6,-1,0
  4382.5   0.075       0  4499.4     0.1       0  4699.0    0.07       0
  4703.0     0.1       0  5644.0   0.075       0  5846.2     0.1       0
Bank Sta=4699,4703
Exp/Cntr=0.3,0.1

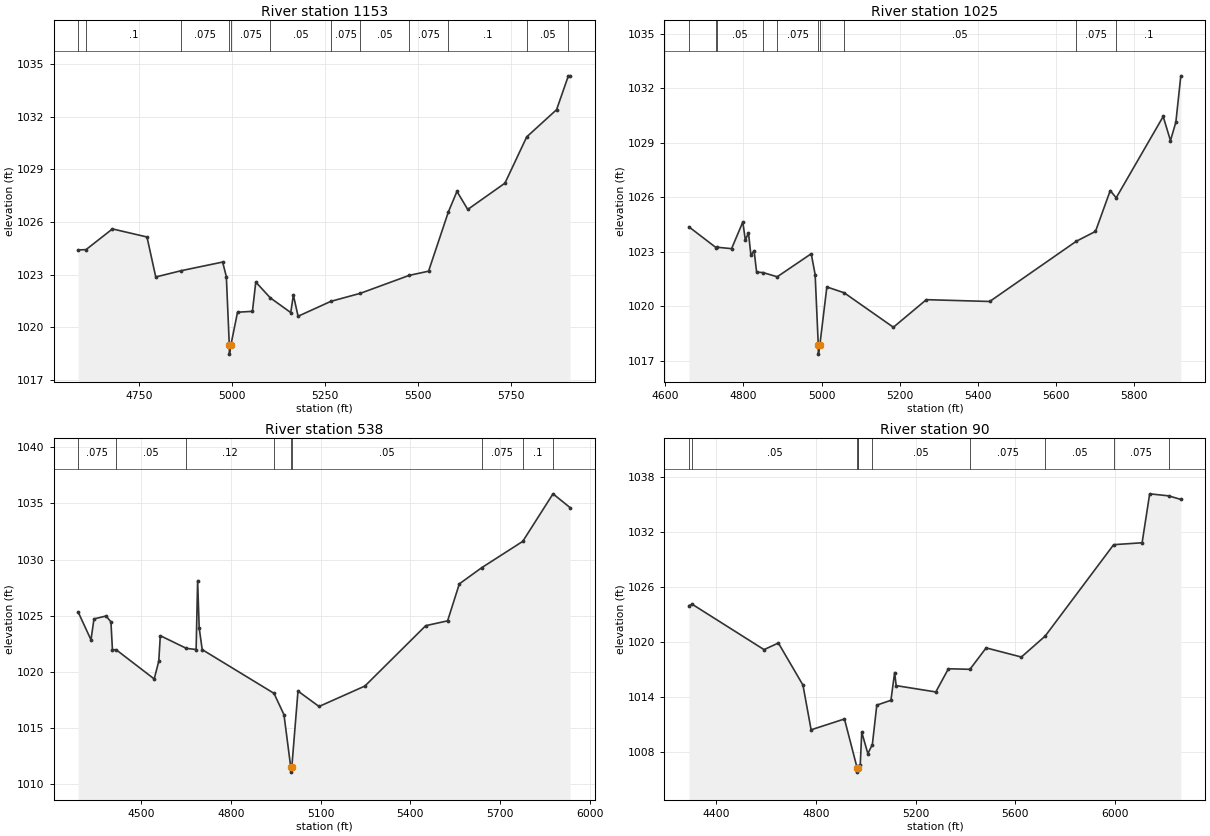
Type RM Length L Ch R = 1,1153,128,128,128
BEGIN DESCRIPTION:
Mapping XS c35b920a
END DESCRIPTION:
XS GIS Cut Line= 4
      2818028.58     10243768.90      2817759.50     10243586.62
      2817776.86     10243343.56      2817082.45     10243048.44
#Sta/Elev= 30
  4585.6 1024.41  4606.9 1024.43  4677.9 1025.61  4770.8 1025.15  4794.4 1022.87
  4863.2 1023.23  4974.3 1023.72  4984.3 1022.89  4992.3 1018.97  4992.6 1018.47
  4996.3 1018.97  5014.4 1020.86  5054.5 1020.91  5063.5 1022.58  5102.5 1021.68
  5157.6 1020.84  5164.6 1021.84  5177.3 1020.63  5265.5 1021.48  5345.1 1021.94
  5476.2 1022.96  5528.3 1023.20  5581.6 1026.58  5604.7 1027.75  5633.7 1026.72
  5733.8 1028.22  5792.4 1030.86  5872.7 1032.41  5903.9 1034.31  5908.8 1034.34
#Mann=12,-1,0
  4585.6   0.075       0  4606.9     0.1       0  4863.2   0.075       0
  4992.3    0.07       0  4996.3   0.075       0  5102.5    0.05       0
  5265.5   0.075       0  5345.1    0.05       0  5476.2   0.075       0
  5581.6     0.1       0  5792.4    0.05       0  5903.9   0.075       0
Bank Sta=4992.3,4996.3
Exp/Cntr=0.3,0.1

Type RM Length L Ch R = 1,1025,487,487,487
BEGIN DESCRIPTION:
Mapping XS a0dcc51a
END DESCRIPTION:
XS GIS Cut Line= 5
      2818106.72     10243725.51      2817898.39     10243560.58
      2817881.03     10243274.12      2817733.46     10243169.95
      2817230.36     10243013.82
#Sta/Elev= 30
  4660.4 1024.37  4729.7 1023.23  4731.7 1023.25  4769.6 1023.17  4798.4 1024.64
  4804.8 1023.64  4812.9 1024.04  4819.2 1022.80  4827.3 1023.06  4833.7 1021.88
  4850.7 1021.85  4886.5 1021.62  4973.7 1022.89  4983.7 1021.74  4991.7 1017.86
  4992.0 1017.36  4995.7 1017.86  5013.7 1021.06  5058.0 1020.74  5184.1 1018.84
  5268.6 1020.36  5430.9 1020.26  5652.9 1023.58  5701.9 1024.12  5739.7 1026.37
  5754.9 1025.97  5875.3 1030.45  5894.0 1029.12  5907.8 1030.14  5920.5 1032.69
#Mann=10,-1,0
  4660.4   0.075       0  4729.7     0.1       0  4731.7    0.05       0
  4850.7     0.1       0  4886.5   0.075       0  4991.7    0.07       0
  4995.7   0.075       0  5058.0    0.05       0  5652.9   0.075       0
  5754.9     0.1       0
Bank Sta=4991.7,4995.7
Exp/Cntr=0.3,0.1

Type RM Length L Ch R = 1,538,448,448,448
BEGIN DESCRIPTION:
Mapping XS 104d2802
END DESCRIPTION:
XS GIS Cut Line= 5
      2818106.72     10243845.72      2818145.79     10243537.55
      2818124.08     10243159.94      2817937.45     10243012.38
      2817244.92     10242817.60
#Sta/Elev= 30
  4288.4 1025.34  4331.4 1022.86  4341.4 1024.72  4381.8 1024.98  4398.2 1024.46
  4403.2 1021.98  4415.6 1021.98  4543.0 1019.38  4558.3 1020.96  4563.4 1023.23
  4650.8 1022.10  4683.3 1022.00  4688.3 1028.13  4693.6 1023.90  4703.7 1021.99
  4943.9 1018.10  4977.3 1016.20  4999.7 1011.59  5000.0 1011.09  5003.7 1011.59
  5024.2 1018.30  5094.7 1016.93  5248.2 1018.75  5451.7 1024.12  5524.9 1024.55
  5564.2 1027.84  5639.2 1029.28  5776.4 1031.62  5877.7 1035.85  5934.6 1034.63
#Mann=9,-1,0
  4288.4   0.075       0  4415.6    0.05       0  4650.8    0.12       0
  4943.9    0.05       0  4999.7    0.03       0  5003.7    0.05       0
  5639.2   0.075       0  5776.4     0.1       0  5877.7   0.075       0
Bank Sta=4999.7,5003.7
Exp/Cntr=0.3,0.1

Type RM Length L Ch R = 1,90,0,0,0
BEGIN DESCRIPTION:
SANFERNANDO076 3.0
END DESCRIPTION:
XS GIS Cut Line= 4
      2818206.13     10243780.79      2818497.00     10243133.00
      2818353.45     10242924.19      2817351.85     10242778.05
#Sta/Elev= 30
  4289.9 1024.00  4303.5 1024.13  4591.4 1019.19  4649.1 1019.91  4747.8 1015.32
  4780.6 1010.44  4914.5 1011.62  4965.0 1006.32  4965.2 1005.82  4969.0 1006.32
  4969.1 1006.32  4978.0 1006.63  4984.0 1010.18  5008.5 1007.84  5026.6 1008.83
  5044.4 1013.13  5101.2 1013.66  5116.1 1016.69  5122.2 1015.26  5281.5 1014.57
  5332.0 1017.10  5418.6 1017.04  5483.6 1019.38  5625.1 1018.38  5720.5 1020.66
  5995.8 1030.64  6110.1 1030.85  6140.5 1036.19  6216.4 1035.97  6265.6 1035.58
#Mann=10,-1,0
  4289.9   0.075       0  4303.5    0.05       0  4965.0    0.07       0
  4969.0    0.05       0  4969.1    0.12       0  5026.6    0.05       0
  5418.6   0.075       0  5720.5    0.05       0  5995.8   0.075       0
  6216.4     0.1       0
Bank Sta=4965,4969
Exp/Cntr=0.3,0.1

Chan Stop Cuts=-1