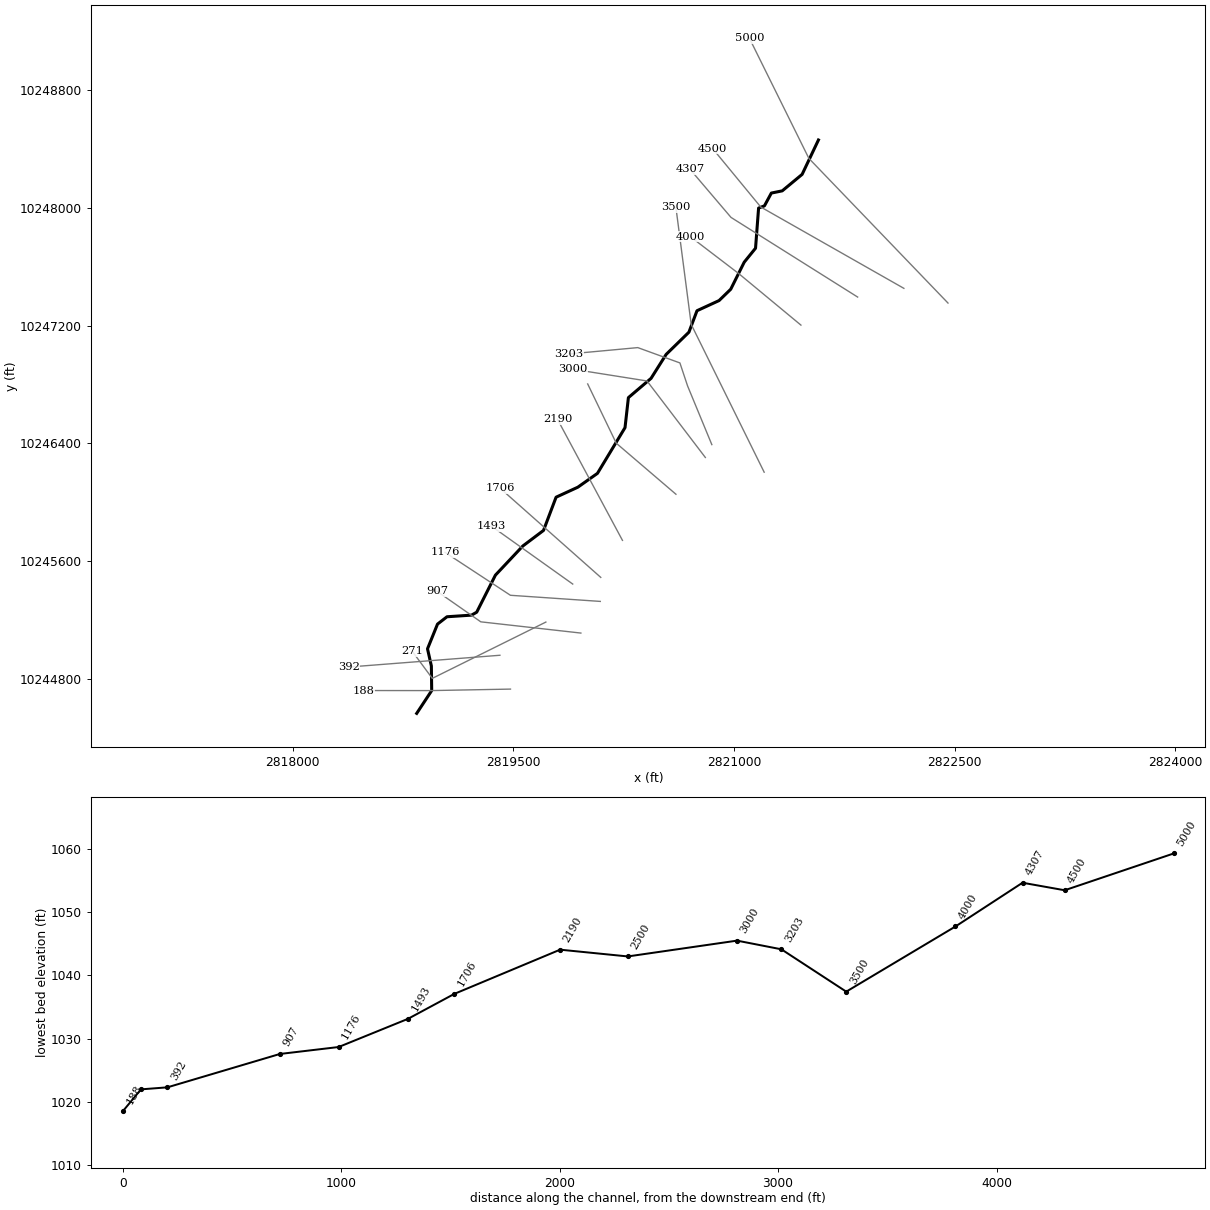
--- SANFERNANDO078.prj (project) ---

Proj Title=SANFERNANDO078 Base Level Engineering
Current Plan=p01
Default Exp/Contr=0.3,0.1
English Units
Geom File=g01
Flow File=f01
Plan File=p01
BEGIN DESCRIPTION:
SANFERNANDO078
END DESCRIPTION:

--- SANFERNANDO078.p01 (plan) ---

Plan Title=Multiple Run
Short Identifier=Multiple
Geom File=g01
Flow File=f01
Subcritical Flow
K Sum by GR= 0
Std Step Tol= 0.01
Critical Tol= 0.01
Num of Std Step Trials= 20
Max Error Tol= 0.3
Flow Tol Ratio= 0.001
Split Flow NTrial= 30
Split Flow Tol= 0.02
Split Flow Ratio= 0.02
Log Output Level= 0
Friction Slope Method= 1
Unsteady Friction Slope Method= 2
Unsteady Bridges Friction Slope Method= 1
Parabolic Critical Depth
Global Vel Dist=  1 , 1 , 1
Global Log Level= 0
CheckData=True
Encroach Param= -1, 0, 0, 0
BEGIN DESCRIPTION:
Multiple Run
END DESCRIPTION:

--- SANFERNANDO078.f01 (steady flow) ---

Flow Title=Multiple
Number of Profiles=7
Profile Names=10-year,25-year,50-year,1pct_min,100-year,1pct_plu,500-year
River Rch & RM= SANFERNANDO078,Reach-1,5000
     275     433     467     303     599    1184     809
Boundary for River Rch & Prof#=SANFERNANDO078,Reach-1,1
Up Type=0
Dn Type=3
Dn Slope=0.005
Boundary for River Rch & Prof#=SANFERNANDO078,Reach-1,2
Up Type=0
Dn Type=3
Dn Slope=0.005
Boundary for River Rch & Prof#=SANFERNANDO078,Reach-1,3
Up Type=0
Dn Type=3
Dn Slope=0.005
Boundary for River Rch & Prof#=SANFERNANDO078,Reach-1,4
Up Type=0
Dn Type=3
Dn Slope=0.005
Boundary for River Rch & Prof#=SANFERNANDO078,Reach-1,5
Up Type=0
Dn Type=3
Dn Slope=0.005
Boundary for River Rch & Prof#=SANFERNANDO078,Reach-1,6
Up Type=0
Dn Type=3
Dn Slope=0.005
Boundary for River Rch & Prof#=SANFERNANDO078,Reach-1,7
Up Type=0
Dn Type=3
Dn Slope=0.005

--- SANFERNANDO078.g01 (geometry) ---

Geom Title=Existing Conditions

River Reach=SANFERNANDO078,Reach-1
Reach XY= 30
      2821574.75     10248462.00      2821463.75     10248228.00
      2821328.50     10248116.00      2821254.50     10248101.00
      2821207.50     10248014.00      2821167.75     10247999.00
      2821147.00     10247726.00      2821070.00     10247631.00
      2820978.25     10247447.00      2820899.00     10247370.00
      2820749.00     10247301.00      2820694.00     10247155.00
      2820539.25     10247004.00      2820436.50     10246841.00
      2820282.50     10246710.00      2820259.50     10246506.00
      2820072.00     10246195.00      2819938.75     10246101.00
      2819790.75     10246033.00      2819705.25     10245807.00
      2819564.50     10245701.00      2819378.25     10245503.00
      2819251.00     10245251.00      2819215.75     10245231.00
      2819049.00     10245220.00      2818984.50     10245170.00
      2818916.50     10245002.00      2818942.75     10244885.00
      2818945.00     10244718.00      2818843.00     10244563.00

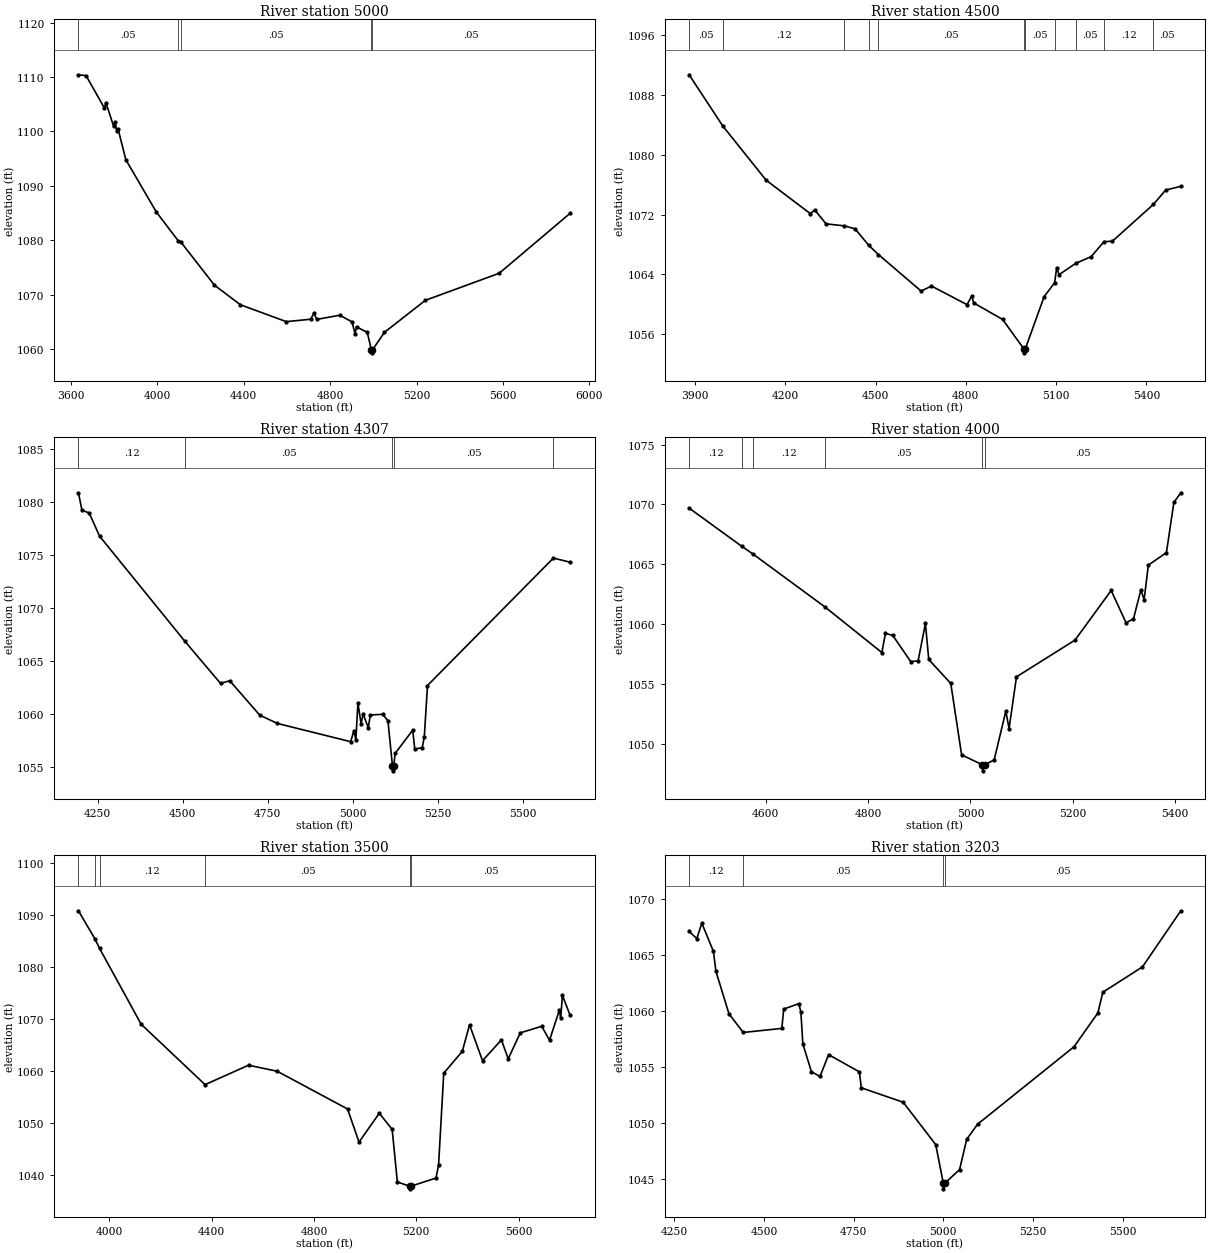
Type RM Length L Ch R = 1,5000,500,500,500
BEGIN DESCRIPTION:
SANFERNANDO078 10.0
END DESCRIPTION:
XS GIS Cut Line= 3
      2822455.70     10247353.09      2821509.75     10248336.74
      2821105.68     10249153.12
#Sta/Elev= 30
  3635.3 1110.43  3670.7 1110.27  3755.6 1104.30  3762.5 1105.29  3798.1 1100.97
  3805.0 1101.73  3812.2 1100.07  3819.1 1100.40  3854.7 1094.80  3996.0 1085.18
  4097.4 1079.88  4108.5 1079.71  4264.7 1071.74  4384.9 1068.13  4597.1 1065.03
  4710.3 1065.47  4724.5 1066.57  4738.6 1065.44  4844.6 1066.21  4901.2 1064.99
  4915.4 1062.84  4922.6 1064.06  4972.0 1063.05  4991.3 1059.79  4991.6 1059.29
  4995.3 1059.79  5051.7 1063.07  5240.9 1068.95  5582.9 1073.93  5910.9 1084.96
#Mann=5,-1,0
  3635.3    0.05       0  4097.4    0.12       0  4108.5    0.05       0
  4991.3    0.03       0  4995.3    0.05       0
Bank Sta=4991.3,4995.3
Exp/Cntr=0.3,0.1

Type RM Length L Ch R = 1,4500,193,193,193
BEGIN DESCRIPTION:
SANFERNANDO078 9.0
END DESCRIPTION:
XS GIS Cut Line= 3
      2822155.71     10247453.10      2821182.57     10248006.12
      2820855.66     10248403.14
#Sta/Elev= 30
  3880.7 1090.73  3993.0 1083.84  4136.6 1076.60  4283.3 1072.12  4298.1 1072.61
  4335.6 1070.75  4396.6 1070.48  4432.2 1070.08  4477.2 1067.88  4509.8 1066.63
  4651.4 1061.74  4685.9 1062.41  4804.1 1059.92  4820.0 1061.10  4825.8 1060.16
  4922.4 1057.93  4993.3 1053.96  4993.6 1053.46  4997.3 1053.96  5060.2 1061.00
  5095.0 1062.85  5101.8 1064.86  5109.7 1063.94  5165.8 1065.47  5216.3 1066.35
  5259.0 1068.36  5286.9 1068.42  5423.0 1073.35  5464.1 1075.28  5514.3 1075.78
#Mann=11,-1,0
  3880.7    0.05       0  3993.0    0.12       0  4396.6    0.05       0
  4477.2    0.12       0  4509.8    0.05       0  4993.3    0.03       0
  4997.3    0.05       0  5095.0    0.12       0  5165.8    0.05       0
  5259.0    0.12       0  5423.0    0.05       0
Bank Sta=4993.3,4997.3
Exp/Cntr=0.3,0.1

Type RM Length L Ch R = 1,4307,307,307,307
BEGIN DESCRIPTION:
Mapping XS d4c32af7
END DESCRIPTION:
XS GIS Cut Line= 3
      2821841.35     10247393.81      2820980.26     10247935.46
      2820702.46     10248261.87
#Sta/Elev= 30
  4193.6 1080.88  4203.9 1079.23  4225.1 1078.98  4255.7 1076.79  4506.8 1066.86
  4611.4 1062.90  4638.5 1063.15  4726.8 1059.90  4778.6 1059.12  4994.1 1057.40
  5003.5 1058.44  5009.4 1057.57  5015.4 1061.06  5024.7 1059.08  5030.6 1060.03
  5045.9 1058.71  5051.8 1059.92  5088.3 1059.98  5103.6 1059.39  5116.9 1055.15
  5117.2 1054.65  5120.9 1055.15  5124.8 1056.29  5176.6 1058.49  5182.5 1056.70
  5204.5 1056.84  5210.6 1057.84  5220.0 1062.70  5590.3 1074.72  5639.5 1074.33
#Mann=5,-1,0
  4193.6    0.12       0  4506.8    0.05       0  5116.9    0.03       0
  5120.9    0.05       0  5590.3    0.12       0
Bank Sta=5116.9,5120.9
Exp/Cntr=0.3,0.1

Type RM Length L Ch R = 1,4000,500,500,500
BEGIN DESCRIPTION:
SANFERNANDO078 8.0
END DESCRIPTION:
XS GIS Cut Line= 3
      2821455.71     10247203.09      2821032.37     10247553.75
      2820705.67     10247803.12
#Sta/Elev= 30
  4450.3 1069.70  4553.3 1066.50  4574.7 1065.87  4715.5 1061.44  4826.9 1057.62
  4833.9 1059.23  4848.2 1059.05  4883.4 1056.86  4897.7 1056.93  4912.0 1060.05
  4918.5 1057.04  4961.5 1055.04  4982.7 1049.07  5023.5 1048.23  5023.7 1047.73
  5027.5 1048.23  5046.3 1048.64  5069.1 1052.73  5075.4 1051.26  5089.9 1055.59
  5204.2 1058.66  5274.9 1062.81  5304.0 1060.11  5318.5 1060.44  5333.0 1062.87
  5339.3 1062.03  5347.5 1064.93  5382.9 1065.98  5397.4 1070.18  5411.0 1070.98
#Mann=6,-1,0
  4450.3    0.12       0  4553.3    0.05       0  4574.7    0.12       0
  4715.5    0.05       0  5023.5    0.03       0  5027.5    0.05       0
Bank Sta=5023.5,5027.5
Exp/Cntr=0.3,0.1

Type RM Length L Ch R = 1,3500,297,297,297
BEGIN DESCRIPTION:
SANFERNANDO078 7.0
END DESCRIPTION:
XS GIS Cut Line= 3
      2821205.69     10246203.11      2820709.49     10247208.20
      2820605.68     10248003.15
#Sta/Elev= 30
  3879.1 1090.84  3943.2 1085.47  3961.7 1083.61  4124.5 1069.03  4374.2 1057.44
  4544.1 1061.17  4656.3 1060.01  4931.3 1052.76  4976.2 1046.40  5055.4 1051.94
  5105.8 1048.84  5126.0 1038.75  5174.4 1037.92  5174.6 1037.42  5178.4 1037.92
  5277.2 1039.49  5287.3 1042.06  5307.5 1059.65  5380.0 1063.83  5408.4 1068.93
  5459.0 1062.04  5532.9 1066.02  5559.6 1062.41  5606.8 1067.39  5690.8 1068.65
  5721.0 1065.96  5759.7 1071.78  5764.7 1070.15  5771.4 1074.60  5801.7 1070.74
#Mann=6,-1,0
  3879.1    0.12       0  3943.2    0.05       0  3961.7    0.12       0
  4374.2    0.05       0  5174.4    0.03       0  5178.4    0.05       0
Bank Sta=5174.4,5178.4
Exp/Cntr=0.3,0.1

Type RM Length L Ch R = 1,3203,203,203,203
BEGIN DESCRIPTION:
Mapping XS 038dffb5
END DESCRIPTION:
XS GIS Cut Line= 5
      2820849.78     10246390.42      2820684.85     10246789.74
      2820632.76     10246945.99      2820346.30     10247050.16
      2819879.16     10247006.91
#Sta/Elev= 30
  4291.4 1067.10  4312.9 1066.46  4326.8 1067.83  4359.2 1065.31  4366.1 1063.54
  4402.5 1059.74  4442.2 1058.08  4549.8 1058.44  4555.2 1060.17  4597.3 1060.65
  4603.0 1059.87  4608.4 1057.06  4632.3 1054.58  4656.3 1054.15  4680.2 1056.10
  4766.1 1054.56  4771.3 1053.14  4888.1 1051.85  4978.8 1048.07  5000.1 1044.62
  5000.3 1044.12  5004.1 1044.62  5045.3 1045.84  5065.3 1048.55  5095.9 1049.90
  5364.3 1056.80  5430.8 1059.82  5444.7 1061.67  5555.1 1063.93  5662.1 1068.94
#Mann=4,-1,0
  4291.4    0.12       0  4442.2    0.05       0  5000.1    0.03       0
  5004.1    0.05       0
Bank Sta=5000.1,5004.1
Exp/Cntr=0.3,0.1

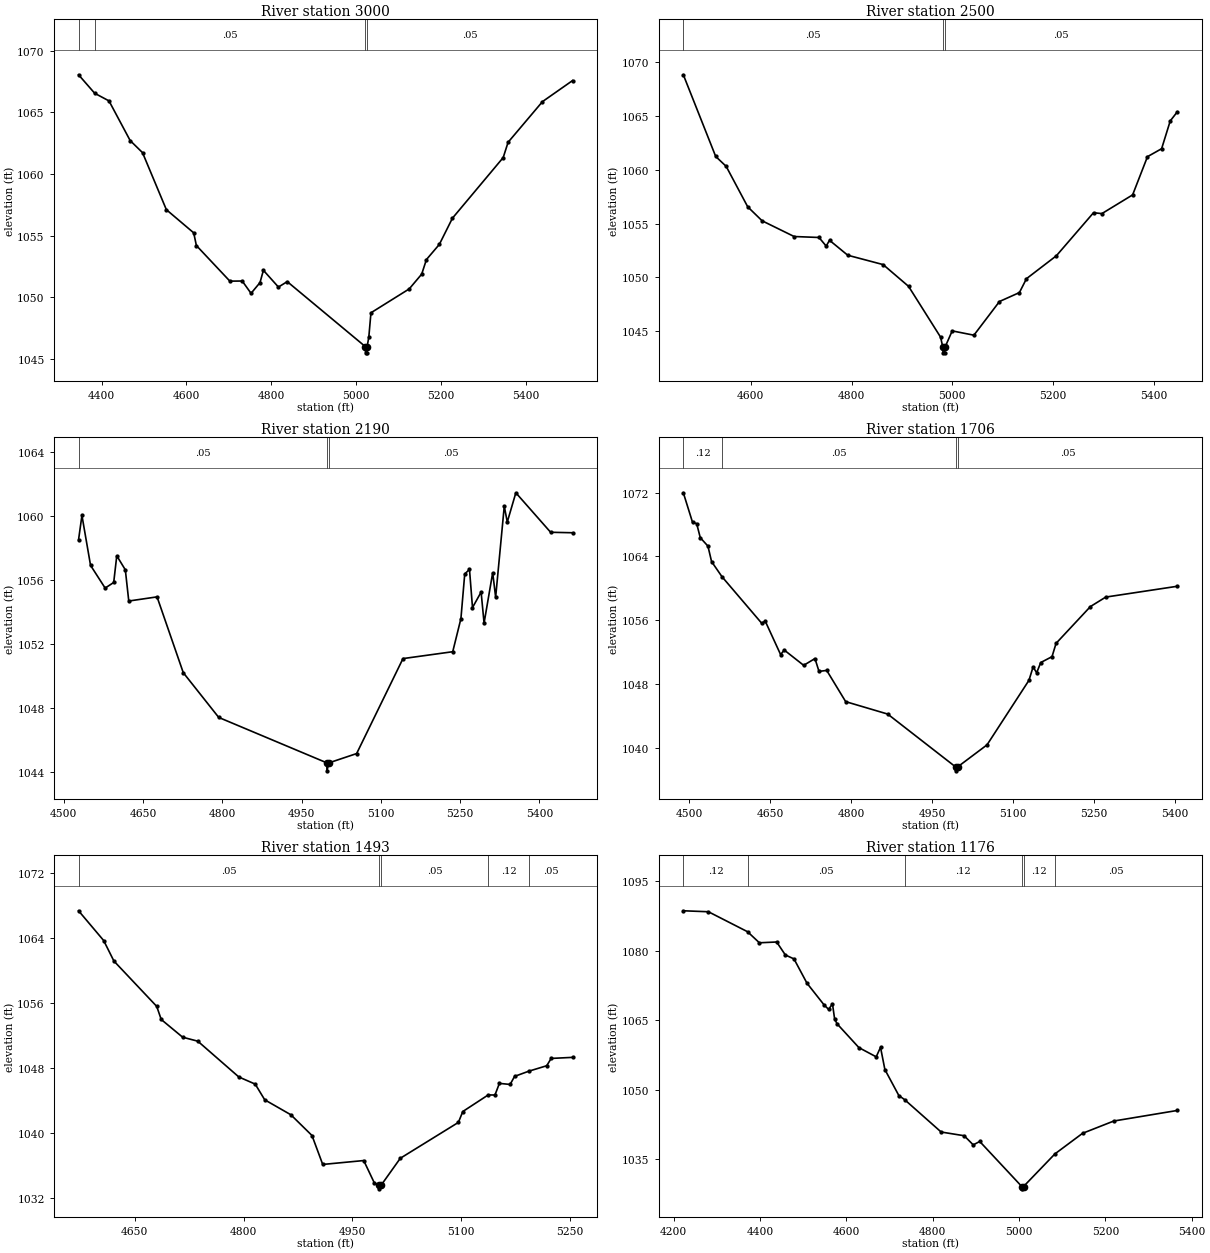
Type RM Length L Ch R = 1,3000,500,500,500
BEGIN DESCRIPTION:
SANFERNANDO078 6.0
END DESCRIPTION:
XS GIS Cut Line= 3
      2820805.70     10246303.09      2820409.19     10246823.31
      2819905.68     10246903.11
#Sta/Elev= 30
  4345.9 1068.06  4383.9 1066.56  4417.6 1065.94  4467.5 1062.72  4496.6 1061.74
  4552.8 1057.11  4617.2 1055.23  4623.5 1054.20  4702.4 1051.31  4731.5 1051.32
  4752.3 1050.32  4773.4 1051.19  4781.4 1052.19  4816.8 1050.83  4837.6 1051.27
  5021.8 1045.99  5022.0 1045.49  5025.5 1045.49  5025.8 1045.99  5029.8 1046.78
  5034.8 1048.74  5125.0 1050.68  5154.4 1051.88  5165.5 1053.06  5195.9 1054.29
  5226.8 1056.42  5346.4 1061.34  5357.9 1062.58  5438.9 1065.88  5509.8 1067.59
#Mann=4,-1,0
  4345.9    0.12       0  4383.9    0.05       0  5021.8    0.05       0
  5025.8    0.05       0
Bank Sta=5021.8,5025.8
Exp/Cntr=0.3,0.1

Type RM Length L Ch R = 1,2500,310,310,310
BEGIN DESCRIPTION:
SANFERNANDO078 5.0
END DESCRIPTION:
XS GIS Cut Line= 3
      2820605.72     10246053.08      2820199.86     10246400.27
      2820005.68     10246803.11
#Sta/Elev= 30
  4465.9 1068.83  4530.2 1061.24  4551.0 1060.32  4593.8 1056.56  4622.4 1055.26
  4686.0 1053.80  4735.4 1053.71  4749.7 1052.91  4756.3 1053.45  4792.5 1052.06
  4862.8 1051.19  4913.3 1049.17  4976.9 1044.45  4981.5 1043.49  4981.8 1042.99
  4985.3 1042.99  4985.5 1043.49  5000.0 1045.03  5043.1 1044.63  5093.9 1047.76
  5133.5 1048.59  5147.5 1049.88  5206.9 1052.01  5280.7 1056.01  5297.4 1055.93
  5358.4 1057.67  5387.9 1061.22  5416.0 1061.96  5433.1 1064.54  5447.2 1065.39
#Mann=3,-1,0
  4465.9    0.05       0  4981.5    0.03       0  4985.5    0.05       0
Bank Sta=4981.5,4985.5
Exp/Cntr=0.3,0.1

Type RM Length L Ch R = 1,2190,484,484,484
BEGIN DESCRIPTION:
Mapping XS 04b090f6
END DESCRIPTION:
XS GIS Cut Line= 2
      2820242.12     10245739.43      2819800.06     10246562.87
#Sta/Elev= 30
  4528.2 1058.51  4534.6 1060.03  4550.9 1056.91  4578.5 1055.49  4594.7 1055.84
  4600.5 1057.51  4616.7 1056.63  4623.2 1054.68  4676.7 1054.94  4726.3 1050.20
  4793.4 1047.40  4997.9 1044.56  4998.1 1044.06  5001.9 1044.56  5054.3 1045.14
  5142.0 1051.08  5236.1 1051.51  5251.6 1053.58  5258.8 1056.37  5267.8 1056.66
  5273.5 1054.27  5289.8 1055.24  5295.4 1053.30  5311.7 1056.45  5317.3 1054.92
  5333.6 1060.61  5339.3 1059.62  5355.5 1061.45  5421.3 1058.98  5462.8 1058.95
#Mann=3,-1,0
  4528.2    0.05       0  4997.9    0.03       0  5001.9    0.05       0
Bank Sta=4997.9,5001.9
Exp/Cntr=0.3,0.1

Type RM Length L Ch R = 1,1706,213,213,213
BEGIN DESCRIPTION:
Mapping XS f1546380
END DESCRIPTION:
XS GIS Cut Line= 2
      2820094.56     10245487.66      2819409.73     10246094.48
#Sta/Elev= 30
  4488.8 1071.99  4505.9 1068.27  4513.5 1068.12  4520.2 1066.35  4534.4 1065.29
  4541.1 1063.35  4560.4 1061.45  4633.9 1055.61  4640.6 1055.86  4669.0 1051.67
  4675.7 1052.24  4711.7 1050.32  4732.6 1051.17  4740.1 1049.56  4754.4 1049.68
  4789.5 1045.76  4867.3 1044.20  4993.0 1037.57  4993.3 1037.07  4997.0 1037.57
  5051.3 1040.33  5129.0 1048.44  5136.6 1050.11  5143.3 1049.39  5150.8 1050.67
  5171.7 1051.41  5179.2 1053.08  5242.8 1057.70  5271.2 1058.89  5403.8 1060.25
#Mann=4,-1,0
  4488.8    0.12       0  4560.4    0.05       0  4993.0    0.03       0
  4997.0    0.05       0
Bank Sta=4993,4997
Exp/Cntr=0.3,0.1

Type RM Length L Ch R = 1,1493,317,317,317
BEGIN DESCRIPTION:
Mapping XS 52aa240a
END DESCRIPTION:
XS GIS Cut Line= 2
      2819903.89     10245442.39      2819349.60     10245837.32
#Sta/Elev= 30
  4572.6 1067.31  4607.2 1063.65  4621.3 1061.13  4680.3 1055.55  4686.5 1053.94
  4716.0 1051.76  4736.9 1051.27  4793.4 1046.87  4816.0 1045.99  4829.1 1044.06
  4865.1 1042.22  4894.2 1039.67  4909.0 1036.11  4965.5 1036.59  4980.3 1033.80
  4985.9 1033.61  4986.1 1033.11  4989.9 1033.61  5015.9 1036.87  5095.9 1041.28
  5102.0 1042.62  5137.0 1044.66  5146.3 1044.65  5152.4 1046.08  5167.2 1045.95
  5173.3 1046.94  5192.9 1047.58  5217.6 1048.25  5223.7 1049.15  5253.2 1049.28
#Mann=5,-1,0
  4572.6    0.05       0  4985.9    0.05       0  4989.9    0.05       0
  5137.0    0.12       0  5192.9    0.05       0
Bank Sta=4985.9,4989.9
Exp/Cntr=0.3,0.1

Type RM Length L Ch R = 1,1176,269,269,269
BEGIN DESCRIPTION:
Mapping XS 725848f1
END DESCRIPTION:
XS GIS Cut Line= 3
      2820091.37     10245324.34      2819480.26     10245366.01
      2819035.85     10245657.66
#Sta/Elev= 30
  4222.6 1088.61  4280.7 1088.40  4371.4 1084.09  4398.7 1081.71  4438.8 1081.88
  4458.8 1079.09  4478.9 1078.23  4509.0 1072.99  4549.0 1068.27  4559.1 1067.35
  4568.0 1068.55  4573.1 1065.21  4579.1 1064.20  4629.2 1059.11  4669.3 1057.12
  4679.3 1059.17  4689.4 1054.38  4721.7 1048.78  4735.1 1047.89  4819.7 1040.91
  4873.0 1040.11  4894.0 1038.14  4909.1 1038.87  5006.5 1029.16  5006.8 1028.66
  5010.5 1029.16  5083.3 1036.20  5147.2 1040.63  5219.5 1043.28  5366.7 1045.56
#Mann=6,-1,0
  4222.6    0.12       0  4371.4    0.05       0  4735.1    0.12       0
  5006.5    0.07       0  5010.5    0.12       0  5083.3    0.05       0
Bank Sta=5006.5,5010.5
Exp/Cntr=0.3,0.1

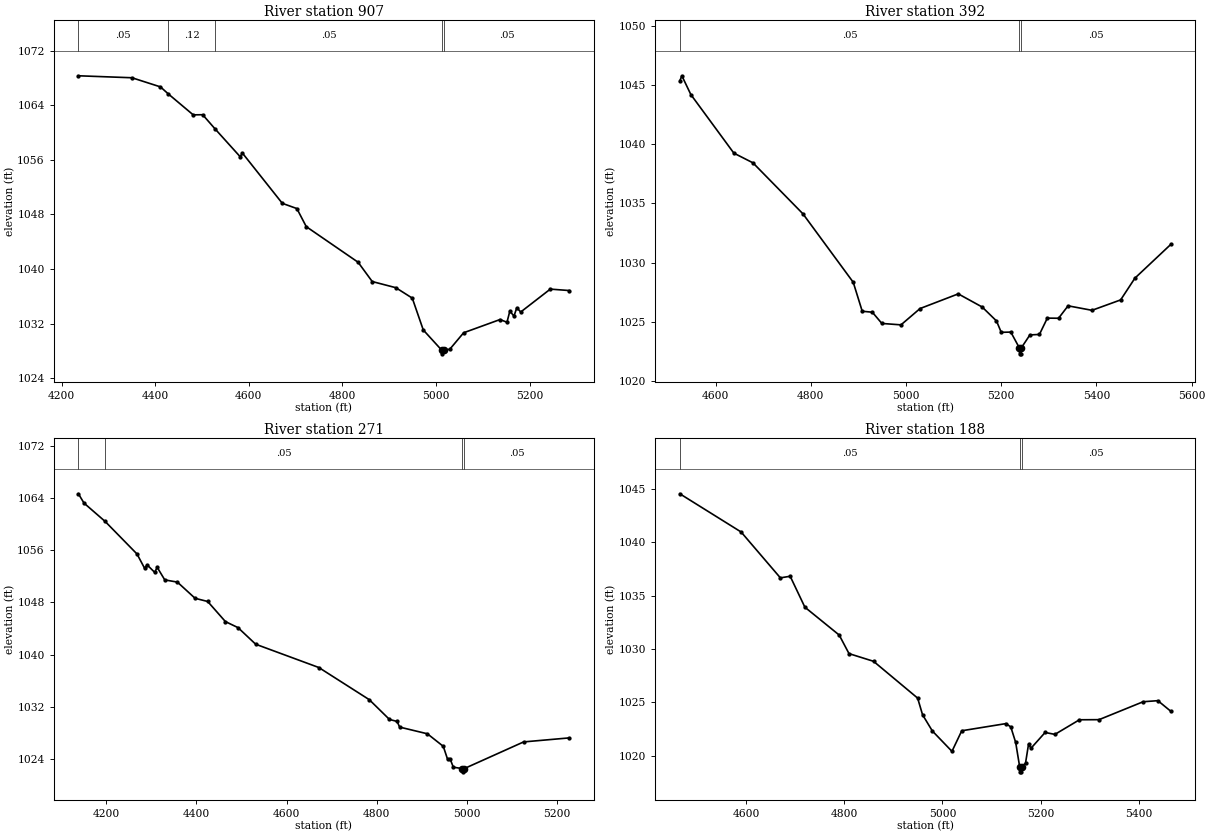
Type RM Length L Ch R = 1,907,515,515,515
BEGIN DESCRIPTION:
Mapping XS fb92ba49
END DESCRIPTION:
XS GIS Cut Line= 3
      2819959.39     10245109.07      2819278.87     10245185.46
      2818980.50     10245393.62
#Sta/Elev= 30
  4236.0 1068.33  4350.4 1068.04  4411.3 1066.70  4428.0 1065.67  4481.2 1062.60
  4501.4 1062.62  4528.3 1060.51  4581.4 1056.47  4586.4 1056.99  4671.5 1049.63
  4702.6 1048.86  4722.7 1046.21  4833.4 1040.99  4863.6 1038.16  4913.9 1037.26
  4949.1 1035.73  4972.6 1031.06  5012.5 1028.06  5012.7 1027.56  5016.5 1028.06
  5029.3 1028.24  5058.8 1030.65  5136.6 1032.59  5151.4 1032.19  5157.5 1033.83
  5166.3 1033.09  5172.4 1034.32  5180.7 1033.69  5243.9 1037.05  5284.6 1036.84
#Mann=5,-1,0
  4236.0    0.05       0  4428.0    0.12       0  4528.3    0.05       0
  5012.5    0.03       0  5016.5    0.05       0
Bank Sta=5012.5,5016.5
Exp/Cntr=0.3,0.1

Type RM Length L Ch R = 1,392,121,121,121
BEGIN DESCRIPTION:
Mapping XS cd648580
END DESCRIPTION:
XS GIS Cut Line= 2
      2819408.84     10244958.15      2818380.66     10244878.11
#Sta/Elev= 30
  4524.8 1045.36  4529.1 1045.79  4548.0 1044.20  4638.3 1039.25  4678.4 1038.43
  4783.4 1034.12  4889.1 1028.33  4908.0 1025.88  4929.2 1025.80  4949.2 1024.85
  4989.4 1024.73  5029.5 1026.11  5109.7 1027.35  5159.9 1026.24  5190.0 1025.06
  5200.0 1024.10  5220.1 1024.12  5238.1 1022.78  5238.4 1022.28  5241.9 1022.28
  5242.1 1022.78  5260.2 1023.88  5280.2 1023.92  5296.8 1025.30  5320.4 1025.29
  5340.4 1026.34  5390.6 1025.96  5450.8 1026.84  5480.8 1028.68  5556.1 1031.53
#Mann=3,-1,0
  4524.8    0.05       0  5238.1    0.03       0  5242.1    0.05       0
Bank Sta=5238.1,5242.1
Exp/Cntr=0.3,0.1

Type RM Length L Ch R = 1,271,83,83,83
BEGIN DESCRIPTION:
Mapping XS 06b0fd38
END DESCRIPTION:
XS GIS Cut Line= 3
      2819721.32     10245183.85      2818949.00     10244801.00
      2818813.60     10244984.07
#Sta/Elev= 30
  4138.0 1064.71  4150.4 1063.28  4197.3 1060.46  4268.1 1055.45  4284.9 1053.26
  4290.5 1053.78  4307.3 1052.63  4312.9 1053.40  4329.7 1051.47  4357.7 1051.13
  4397.0 1048.64  4425.0 1048.15  4464.3 1045.06  4492.3 1044.13  4531.5 1041.58
  4671.6 1038.00  4783.7 1033.05  4828.5 1030.01  4845.4 1029.71  4851.0 1028.84
  4912.6 1027.81  4947.9 1025.88  4957.5 1023.87  4963.1 1023.93  4970.2 1022.67
  4990.5 1022.46  4990.8 1021.96  4994.5 1022.46  5126.2 1026.56  5227.7 1027.18
#Mann=4,-1,0
  4138.0    0.12       0  4197.3    0.05       0  4990.5    0.03       0
  4994.5    0.05       0
Bank Sta=4990.5,4994.5
Exp/Cntr=0.3,0.1

Type RM Length L Ch R = 1,188,0,0,0
BEGIN DESCRIPTION:
SANFERNANDO078 4.0
END DESCRIPTION:
XS GIS Cut Line= 3
      2819480.70     10244728.11      2818945.00     10244718.00
      2818479.40     10244718.29
#Sta/Elev= 30
  4464.2 1044.56  4589.2 1040.98  4669.3 1036.68  4689.3 1036.83  4719.3 1033.93
  4789.3 1031.32  4809.3 1029.58  4859.3 1028.86  4949.3 1025.41  4959.3 1023.85
  4979.3 1022.33  5019.3 1020.42  5039.3 1022.35  5129.3 1023.02  5139.3 1022.71
  5149.3 1021.25  5157.3 1019.00  5157.6 1018.50  5161.1 1018.50  5161.3 1019.00
  5169.3 1019.30  5175.5 1021.09  5180.5 1020.71  5209.3 1022.19  5229.3 1022.01
  5279.3 1023.38  5319.3 1023.39  5409.3 1025.07  5439.3 1025.17  5465.6 1024.18
#Mann=3,-1,0
  4464.2    0.05       0  5157.3    0.05       0  5161.3    0.05       0
Bank Sta=5157.3,5161.3
Exp/Cntr=0.3,0.1

Chan Stop Cuts=-1