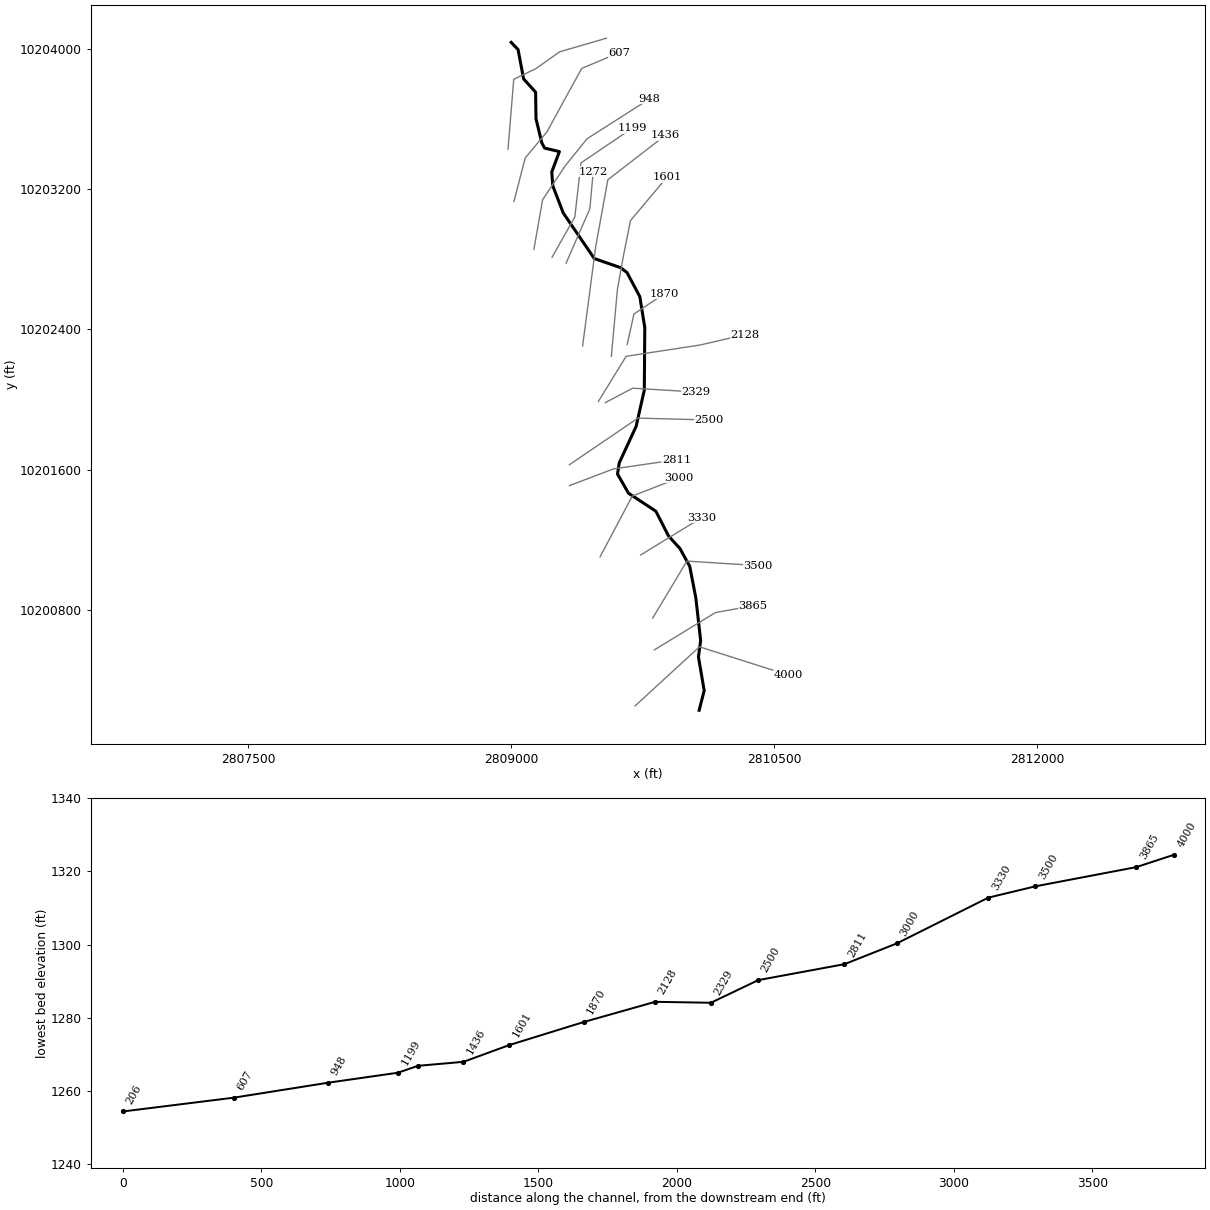
--- SANFERNANDO080.prj (project) ---

Proj Title=SANFERNANDO080 Base Level Engineering
Current Plan=p01
Default Exp/Contr=0.3,0.1
English Units
Geom File=g01
Flow File=f01
Plan File=p01
BEGIN DESCRIPTION:
SANFERNANDO080
END DESCRIPTION:

--- SANFERNANDO080.p01 (plan) ---

Plan Title=Multiple Run
Short Identifier=Multiple
Geom File=g01
Flow File=f01
Subcritical Flow
K Sum by GR= 0
Std Step Tol= 0.01
Critical Tol= 0.01
Num of Std Step Trials= 20
Max Error Tol= 0.3
Flow Tol Ratio= 0.001
Split Flow NTrial= 30
Split Flow Tol= 0.02
Split Flow Ratio= 0.02
Log Output Level= 0
Friction Slope Method= 1
Unsteady Friction Slope Method= 2
Unsteady Bridges Friction Slope Method= 1
Parabolic Critical Depth
Global Vel Dist=  1 , 1 , 1
Global Log Level= 0
CheckData=True
Encroach Param= -1, 0, 0, 0
BEGIN DESCRIPTION:
Multiple Run
END DESCRIPTION:

--- SANFERNANDO080.f01 (steady flow) ---

Flow Title=Multiple
Number of Profiles=7
Profile Names=10-year,25-year,50-year,1pct_min,100-year,1pct_plu,500-year
River Rch & RM= SANFERNANDO080,Reach-1,4000
     137     208     287     173     374     809     531
Boundary for River Rch & Prof#=SANFERNANDO080,Reach-1,1
Up Type=0
Dn Type=3
Dn Slope=0.005
Boundary for River Rch & Prof#=SANFERNANDO080,Reach-1,2
Up Type=0
Dn Type=3
Dn Slope=0.005
Boundary for River Rch & Prof#=SANFERNANDO080,Reach-1,3
Up Type=0
Dn Type=3
Dn Slope=0.005
Boundary for River Rch & Prof#=SANFERNANDO080,Reach-1,4
Up Type=0
Dn Type=3
Dn Slope=0.005
Boundary for River Rch & Prof#=SANFERNANDO080,Reach-1,5
Up Type=0
Dn Type=3
Dn Slope=0.005
Boundary for River Rch & Prof#=SANFERNANDO080,Reach-1,6
Up Type=0
Dn Type=3
Dn Slope=0.005
Boundary for River Rch & Prof#=SANFERNANDO080,Reach-1,7
Up Type=0
Dn Type=3
Dn Slope=0.005

--- SANFERNANDO080.g01 (geometry) ---

Geom Title=Existing Conditions

River Reach=SANFERNANDO080,Reach-1
Reach XY= 30
      2810070.75     10200228.00      2810099.50     10200340.00
      2810066.75     10200532.00      2810079.25     10200626.00
      2810051.75     10200869.00      2810017.00     10201049.00
      2809961.50     10201150.00      2809896.00     10201222.00
      2809824.00     10201363.00      2809667.75     10201466.00
      2809605.25     10201575.00      2809614.75     10201638.00
      2809711.25     10201847.00      2809758.00     10202054.00
      2809760.75     10202410.00      2809732.25     10202587.00
      2809659.50     10202724.00      2809623.25     10202752.00
      2809472.75     10202804.00      2809295.75     10203064.00
      2809236.00     10203219.00      2809230.25     10203298.00
      2809273.75     10203414.00      2809189.75     10203434.00
      2809173.75     10203463.00      2809140.25     10203601.00
      2809138.00     10203753.00      2809069.50     10203829.00
      2809038.00     10203996.00      2808998.50     10204037.00

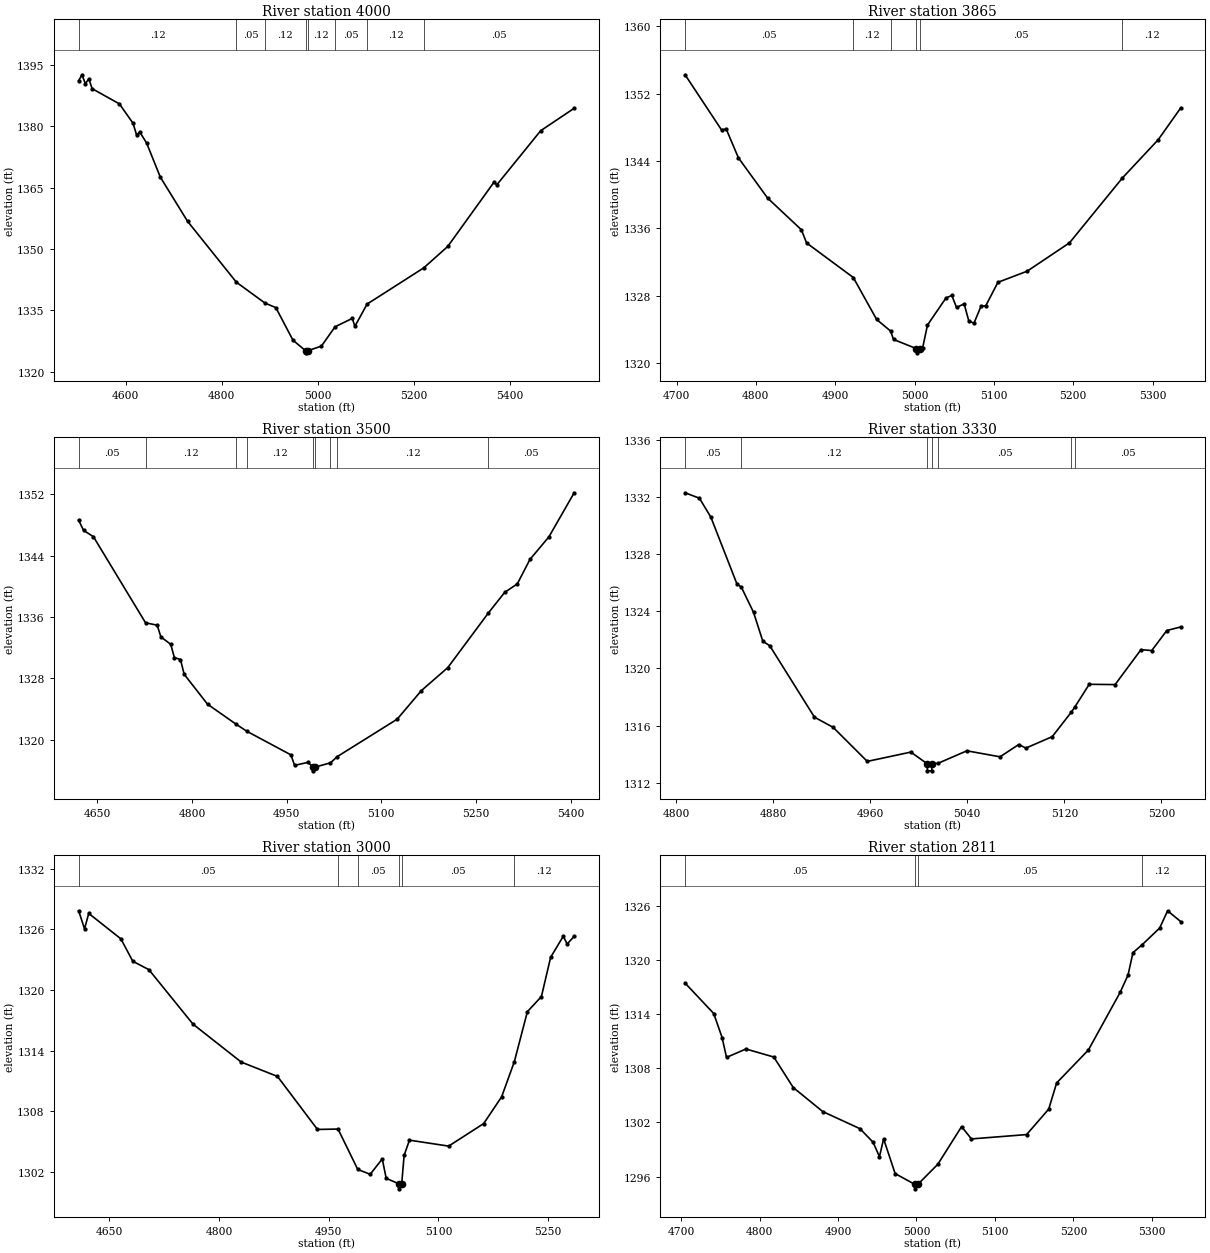
Type RM Length L Ch R = 1,4000,135,135,135
BEGIN DESCRIPTION:
SANFERNANDO080 7.0
END DESCRIPTION:
XS GIS Cut Line= 3
      2809705.67     10200253.10      2810072.54     10200589.86
      2810580.71     10200428.10
#Sta/Elev= 30
  4502.0 1391.20  4509.1 1392.63  4515.9 1390.45  4523.3 1391.62  4530.1 1389.23
  4586.8 1385.51  4615.2 1380.77  4622.6 1377.90  4629.3 1378.61  4643.5 1375.92
  4671.9 1367.60  4728.6 1356.78  4830.3 1341.86  4890.1 1336.73  4912.4 1335.64
  4948.1 1327.66  4974.5 1325.07  4974.7 1324.57  4978.5 1325.07  5007.2 1326.21
  5035.7 1330.95  5071.6 1333.00  5076.9 1331.06  5102.4 1336.51  5220.3 1345.37
  5270.2 1350.61  5366.9 1366.41  5372.1 1365.67  5463.6 1378.94  5533.3 1384.43
#Mann=8,-1,0
  4502.0    0.12       0  4830.3    0.05       0  4890.1    0.12       0
  4974.5    0.07       0  4978.5    0.12       0  5035.7    0.05       0
  5102.4    0.12       0  5220.3    0.05       0
Bank Sta=4974.5,4978.5
Exp/Cntr=0.3,0.1

Type RM Length L Ch R = 1,3865,365,365,365
BEGIN DESCRIPTION:
Mapping XS b4fe72d0
END DESCRIPTION:
XS GIS Cut Line= 3
      2809815.01     10200572.02      2810163.35     10200784.89
      2810376.22     10200823.60
#Sta/Elev= 30
  4710.8 1354.25  4756.7 1347.70  4762.6 1347.81  4778.0 1344.38  4814.8 1339.60
  4857.4 1335.83  4863.9 1334.27  4922.8 1330.16  4952.2 1325.18  4969.9 1323.79
  4973.5 1322.80  5002.4 1321.71  5002.7 1321.21  5006.4 1321.71  5010.3 1321.84
  5016.3 1324.51  5039.7 1327.74  5047.0 1328.03  5052.9 1326.60  5062.5 1327.03
  5068.4 1325.00  5074.9 1324.73  5083.8 1326.75  5089.7 1326.79  5105.1 1329.59
  5141.9 1330.91  5195.3 1334.28  5262.0 1341.99  5307.1 1346.53  5335.4 1350.30
#Mann=6,-1,0
  4710.8    0.05       0  4922.8    0.12       0  4969.9    0.05       0
  5002.4    0.05       0  5006.4    0.05       0  5262.0    0.12       0
Bank Sta=5002.4,5006.4
Exp/Cntr=0.3,0.1

Type RM Length L Ch R = 1,3500,170,170,170
BEGIN DESCRIPTION:
SANFERNANDO080 6.0
END DESCRIPTION:
XS GIS Cut Line= 3
      2809805.66     10200753.07      2810000.74     10201078.59
      2810405.64     10201053.11
#Sta/Elev= 30
  4620.5 1348.61  4628.3 1347.28  4643.9 1346.46  4726.5 1335.24  4745.0 1334.92
  4750.8 1333.40  4766.4 1332.43  4772.2 1330.71  4781.9 1330.44  4787.7 1328.53
  4824.7 1324.63  4869.6 1322.04  4887.4 1321.08  4956.9 1318.02  4962.7 1316.65
  4984.1 1317.05  4991.6 1316.44  4991.9 1315.94  4995.6 1316.44  5019.5 1316.98
  5030.4 1317.80  5125.2 1322.67  5163.6 1326.40  5205.4 1329.39  5269.8 1336.52
  5295.5 1339.19  5315.6 1340.31  5335.6 1343.49  5365.7 1346.44  5405.7 1352.18
#Mann=9,-1,0
  4620.5    0.05       0  4726.5    0.12       0  4869.6    0.05       0
  4887.4    0.12       0  4991.6    0.07       0  4995.6    0.12       0
  5019.5    0.05       0  5030.4    0.12       0  5269.8    0.05       0
Bank Sta=4991.6,4995.6
Exp/Cntr=0.3,0.1

Type RM Length L Ch R = 1,3330,330,330,330
BEGIN DESCRIPTION:
Mapping XS 9c1ed08e
END DESCRIPTION:
XS GIS Cut Line= 2
      2809737.58     10201113.84      2810085.97     10201326.75
#Sta/Elev= 30
  4807.5 1332.28  4819.3 1331.90  4828.7 1330.58  4850.2 1325.91  4853.8 1325.69
  4863.9 1323.92  4871.5 1321.91  4877.3 1321.58  4914.1 1316.59  4929.5 1315.88
  4957.6 1313.50  4993.5 1314.15  5006.9 1313.34  5007.2 1312.84  5010.7 1312.84
  5010.9 1313.34  5015.7 1313.36  5039.7 1314.24  5067.0 1313.82  5082.4 1314.68
  5088.3 1314.43  5110.0 1315.23  5125.6 1316.93  5128.6 1317.30  5140.5 1318.89
  5161.8 1318.87  5183.1 1321.31  5192.0 1321.25  5204.4 1322.65  5215.8 1322.90
#Mann=7,-1,0
  4807.5    0.05       0  4853.8    0.12       0  5006.9    0.07       0
  5010.9    0.12       0  5015.7    0.05       0  5125.6    0.12       0
  5128.6    0.05       0
Bank Sta=5006.9,5010.9
Exp/Cntr=0.3,0.1

Type RM Length L Ch R = 1,3000,189,189,189
BEGIN DESCRIPTION:
SANFERNANDO080 5.0
END DESCRIPTION:
XS GIS Cut Line= 3
      2809505.70     10201103.14      2809689.40     10201449.55
      2809955.67     10201553.11
#Sta/Elev= 30
  4607.9 1327.85  4616.0 1326.06  4621.7 1327.59  4665.7 1325.07  4682.0 1322.85
  4704.0 1322.02  4764.3 1316.63  4830.3 1312.87  4879.9 1311.45  4934.6 1306.20
  4962.7 1306.24  4989.7 1302.24  5006.7 1301.76  5023.2 1303.28  5028.6 1301.36
  5045.8 1300.82  5046.0 1300.32  5049.8 1300.82  5053.1 1303.63  5060.4 1305.14
  5114.0 1304.55  5161.9 1306.78  5186.5 1309.43  5203.9 1312.92  5221.7 1317.86
  5240.9 1319.36  5253.5 1323.24  5270.8 1325.33  5276.1 1324.56  5285.7 1325.32
#Mann=6,-1,0
  4607.9    0.05       0  4962.7    0.12       0  4989.7    0.05       0
  5045.8    0.05       0  5049.8    0.05       0  5203.9    0.12       0
Bank Sta=5045.8,5049.8
Exp/Cntr=0.3,0.1

Type RM Length L Ch R = 1,2811,311,311,311
BEGIN DESCRIPTION:
Mapping XS c74b01c7
END DESCRIPTION:
XS GIS Cut Line= 3
      2809331.55     10201509.27      2809583.24     10201604.74
      2809942.12     10201656.63
#Sta/Elev= 30
  4705.0 1317.43  4741.5 1314.06  4752.2 1311.39  4757.8 1309.20  4782.6 1310.13
  4818.1 1309.24  4842.9 1305.86  4880.5 1303.20  4928.0 1301.30  4944.7 1299.80
  4952.8 1298.20  4958.1 1300.17  4972.8 1296.33  4997.8 1295.14  4998.1 1294.64
  5001.8 1295.14  5027.2 1297.36  5057.5 1301.53  5070.1 1300.17  5140.4 1300.65
  5168.6 1303.47  5178.7 1306.37  5219.2 1310.02  5259.6 1316.39  5269.7 1318.31
  5276.0 1320.80  5288.0 1321.70  5310.1 1323.53  5320.2 1325.44  5336.8 1324.25
#Mann=4,-1,0
  4705.0    0.05       0  4997.8    0.05       0  5001.8    0.05       0
  5288.0    0.12       0
Bank Sta=4997.8,5001.8
Exp/Cntr=0.3,0.1

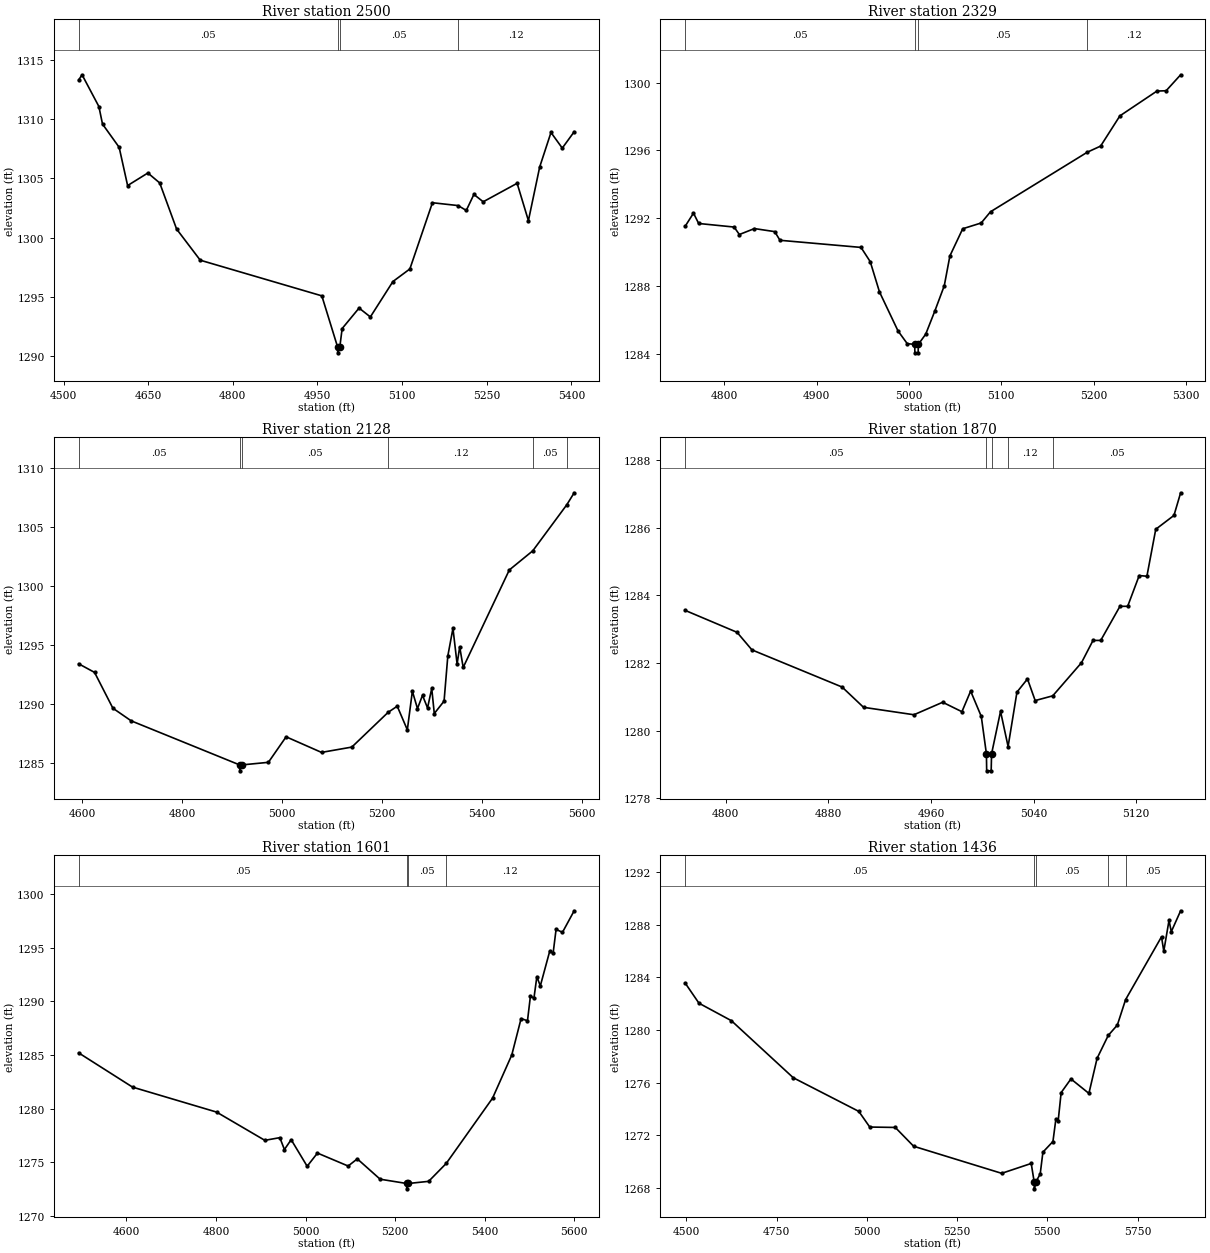
Type RM Length L Ch R = 1,2500,171,171,171
BEGIN DESCRIPTION:
SANFERNANDO080 4.0
END DESCRIPTION:
XS GIS Cut Line= 3
      2809330.68     10201628.11      2809721.93     10201894.28
      2810126.78     10201883.22
#Sta/Elev= 30
  4526.8 1313.31  4532.9 1313.75  4562.7 1311.07  4569.1 1309.59  4598.6 1307.63
  4613.6 1304.40  4649.5 1305.46  4670.5 1304.62  4700.4 1300.73  4742.3 1298.10
  4957.8 1295.09  4985.7 1290.78  4986.0 1290.28  4989.7 1290.78  4993.8 1292.33
  5023.8 1294.06  5043.8 1293.31  5083.8 1296.30  5113.8 1297.36  5153.8 1302.95
  5199.3 1302.71  5213.8 1302.30  5227.3 1303.65  5243.8 1303.03  5303.9 1304.59
  5323.9 1301.44  5343.9 1305.97  5363.9 1308.88  5383.9 1307.56  5405.0 1308.94
#Mann=4,-1,0
  4526.8    0.05       0  4985.7    0.03       0  4989.7    0.05       0
  5199.3    0.12       0
Bank Sta=4985.7,4989.7
Exp/Cntr=0.3,0.1

Type RM Length L Ch R = 1,2329,201,201,201
BEGIN DESCRIPTION:
Mapping XS ac5b2282
END DESCRIPTION:
XS GIS Cut Line= 3
      2809535.53     10201982.36      2809691.75     10202064.81
      2810051.36     10202043.15
#Sta/Elev= 30
  4757.4 1291.53  4766.5 1292.31  4772.1 1291.70  4810.5 1291.49  4816.2 1291.05
  4832.5 1291.40  4854.5 1291.22  4860.2 1290.71  4948.0 1290.29  4958.0 1289.45
  4968.0 1287.67  4988.1 1285.37  4998.1 1284.62  5006.1 1284.58  5006.4 1284.08
  5009.9 1284.08  5010.1 1284.58  5018.1 1285.18  5028.1 1286.56  5038.2 1288.03
  5044.3 1289.79  5058.2 1291.39  5078.2 1291.73  5088.3 1292.39  5193.2 1295.90
  5207.6 1296.26  5228.5 1298.04  5268.6 1299.50  5278.6 1299.52  5294.3 1300.46
#Mann=4,-1,0
  4757.4    0.05       0  5006.1    0.03       0  5010.1    0.05       0
  5193.2    0.12       0
Bank Sta=5006.1,5010.1
Exp/Cntr=0.3,0.1

Type RM Length L Ch R = 1,2128,258,258,258
BEGIN DESCRIPTION:
Mapping XS 71111c42
END DESCRIPTION:
XS GIS Cut Line= 4
      2809495.51     10201988.47      2809654.28     10202246.47
      2810076.00     10202310.96      2810332.30     10202370.11
#Sta/Elev= 30
  4592.5 1293.40  4624.4 1292.67  4661.1 1289.64  4697.8 1288.57  4915.1 1284.84
  4915.3 1284.34  4919.1 1284.84  4972.6 1285.06  5008.1 1287.22  5079.0 1285.90
  5139.7 1286.35  5212.4 1289.29  5230.7 1289.81  5250.9 1287.81  5261.0 1291.08
  5271.2 1289.61  5281.3 1290.73  5291.4 1289.66  5299.8 1291.31  5304.9 1289.19
  5324.5 1290.24  5332.0 1294.06  5342.3 1296.40  5350.6 1293.38  5355.8 1294.83
  5362.8 1293.09  5455.2 1301.34  5502.2 1302.96  5570.4 1306.86  5585.1 1307.87
#Mann=6,-1,0
  4592.5    0.05       0  4915.1    0.03       0  4919.1    0.05       0
  5212.4    0.12       0  5502.2    0.05       0  5570.4    0.12       0
Bank Sta=4915.1,4919.1
Exp/Cntr=0.3,0.1

Type RM Length L Ch R = 1,1870,269,269,269
BEGIN DESCRIPTION:
Mapping XS 559af306
END DESCRIPTION:
XS GIS Cut Line= 3
      2809660.20     10202313.62      2809698.92     10202487.82
      2809871.86     10202603.12
#Sta/Elev= 30
  4768.3 1283.56  4808.8 1282.91  4820.4 1282.39  4890.7 1281.29  4907.4 1280.69
  4946.7 1280.47  4969.1 1280.84  4984.1 1280.56  4990.9 1281.17  4999.2 1280.42
  5003.2 1279.31  5003.4 1278.81  5006.9 1278.81  5007.2 1279.31  5014.2 1280.57
  5020.1 1279.53  5027.0 1281.14  5035.2 1281.53  5041.2 1280.89  5054.9 1281.03
  5077.3 1282.01  5086.3 1282.67  5092.3 1282.67  5107.3 1283.68  5113.3 1283.68
  5122.3 1284.59  5128.3 1284.57  5135.2 1285.96  5149.4 1286.37  5154.6 1287.04
#Mann=5,-1,0
  4768.3    0.05       0  5003.2    0.03       0  5007.2    0.05       0
  5020.1    0.12       0  5054.9    0.05       0
Bank Sta=5003.2,5007.2
Exp/Cntr=0.3,0.1

Type RM Length L Ch R = 1,1601,165,165,165
BEGIN DESCRIPTION:
Mapping XS 06affd19
END DESCRIPTION:
XS GIS Cut Line= 5
      2809569.93     10202246.48      2809604.66     10202628.50
      2809639.39     10202821.99      2809679.08     10203020.45
      2809887.31     10203268.33
#Sta/Elev= 30
  4493.4 1285.20  4613.8 1282.00  4801.3 1279.67  4909.1 1277.03  4942.6 1277.28
  4952.8 1276.17  4967.9 1277.09  5003.6 1274.61  5026.6 1275.84  5095.1 1274.63
  5115.5 1275.30  5166.5 1273.40  5225.7 1273.00  5225.9 1272.50  5229.7 1273.00
  5274.8 1273.20  5314.0 1274.87  5417.5 1280.97  5460.4 1285.00  5481.2 1288.40
  5495.5 1288.20  5502.1 1290.53  5509.8 1290.28  5516.4 1292.32  5524.1 1291.45
  5545.0 1294.68  5552.7 1294.51  5559.3 1296.73  5573.6 1296.46  5599.7 1298.47
#Mann=4,-1,0
  4493.4    0.05       0  5225.7    0.03       0  5229.7    0.05       0
  5314.0    0.12       0
Bank Sta=5225.7,5229.7
Exp/Cntr=0.3,0.1

Type RM Length L Ch R = 1,1436,164,164,164
BEGIN DESCRIPTION:
Mapping XS abad6aea
END DESCRIPTION:
XS GIS Cut Line= 4
      2809406.21     10202306.02      2809480.63     10202871.61
      2809550.09     10203253.64      2809877.56     10203506.68
#Sta/Elev= 30
  4496.7 1283.58  4535.1 1282.04  4624.9 1280.71  4796.3 1276.37  4977.9 1273.81
  5008.2 1272.62  5078.9 1272.59  5129.7 1271.16  5373.6 1269.10  5455.4 1269.85
  5463.8 1268.42  5464.1 1267.92  5467.8 1268.42  5480.3 1269.05  5487.8 1270.71
  5515.6 1271.52  5523.8 1273.24  5530.1 1273.09  5538.3 1275.24  5565.4 1276.28
  5615.2 1275.18  5637.9 1277.85  5668.8 1279.59  5694.0 1280.38  5716.8 1282.31
  5816.3 1287.09  5822.6 1286.00  5837.1 1288.34  5843.4 1287.48  5869.3 1289.07
#Mann=5,-1,0
  4496.7    0.05       0  5463.8    0.03       0  5467.8    0.05       0
  5668.8    0.12       0  5716.8    0.05       0
Bank Sta=5463.8,5467.8
Exp/Cntr=0.3,0.1

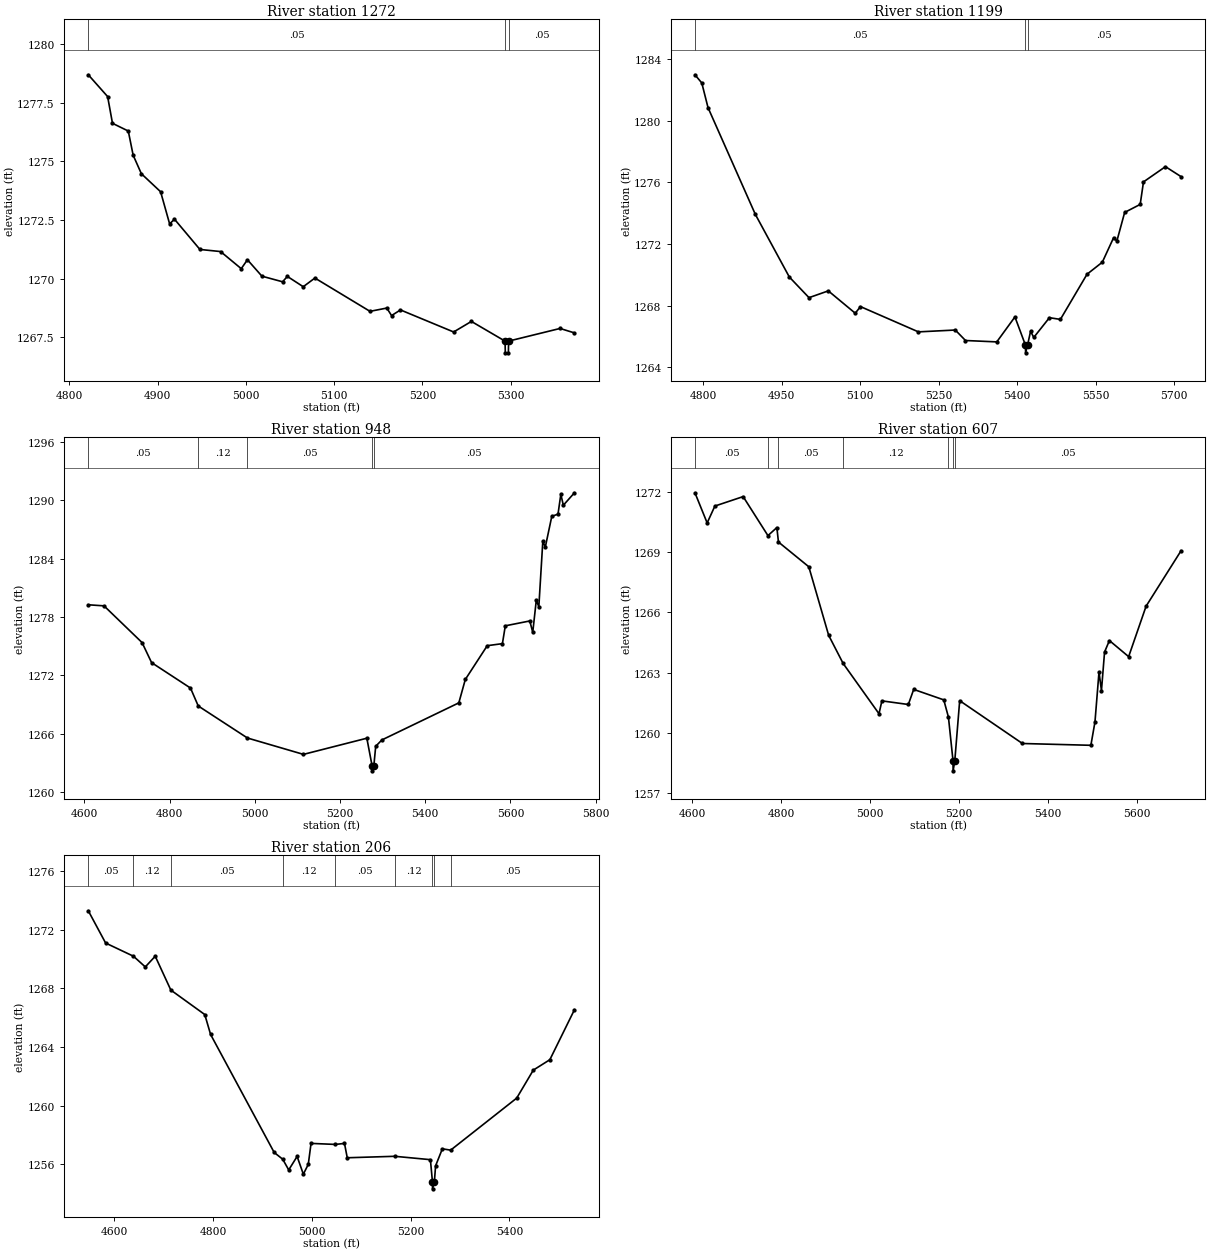
Type RM Length L Ch R = 1,1272,73,73,73
BEGIN DESCRIPTION:
Mapping XS 0125ba77
END DESCRIPTION:
XS GIS Cut Line= 3
      2809311.87     10202778.06      2809447.35     10203087.72
      2809466.59     10203299.35
#Sta/Elev= 30
  4821.6 1278.69  4843.5 1277.76  4849.0 1276.62  4866.9 1276.29  4872.4 1275.26
  4881.7 1274.47  4903.5 1273.70  4913.7 1272.33  4919.2 1272.53  4948.0 1271.24
  4971.4 1271.15  4994.8 1270.42  5001.8 1270.80  5018.2 1270.10  5041.6 1269.86
  5047.0 1270.09  5065.0 1269.65  5078.2 1270.02  5140.6 1268.60  5159.6 1268.74
  5165.0 1268.42  5175.1 1268.66  5235.3 1267.72  5255.4 1268.17  5293.5 1267.33
  5293.8 1266.83  5297.3 1266.83  5297.5 1267.33  5355.8 1267.87  5372.1 1267.68
#Mann=3,-1,0
  4821.6    0.05       0  5293.5    0.05       0  5297.5    0.05       0
Bank Sta=5293.5,5297.5
Exp/Cntr=0.3,0.1

Type RM Length L Ch R = 1,1199,251,251,251
BEGIN DESCRIPTION:
Mapping XS e134c7a8
END DESCRIPTION:
XS GIS Cut Line= 4
      2809231.67     10202811.32      2809361.89     10203041.37
      2809396.61     10203349.53      2809690.44     10203548.30
#Sta/Elev= 30
  4784.3 1282.97  4797.4 1282.44  4809.3 1280.84  4899.8 1273.91  4964.7 1269.85
  5002.3 1268.51  5039.2 1268.95  5090.7 1267.50  5100.7 1267.93  5211.4 1266.29
  5281.9 1266.41  5301.4 1265.73  5361.2 1265.64  5395.9 1267.26  5416.0 1265.43
  5416.3 1264.93  5420.0 1265.43  5425.8 1266.33  5431.9 1265.93  5461.8 1267.21
  5482.8 1267.10  5533.7 1270.03  5562.9 1270.81  5584.6 1272.41  5590.7 1272.18
  5605.6 1274.04  5635.3 1274.56  5641.6 1276.02  5683.6 1277.01  5713.5 1276.36
#Mann=3,-1,0
  4784.3    0.05       0  5416.0    0.05       0  5420.0    0.05       0
Bank Sta=5416,5420
Exp/Cntr=0.3,0.1

Type RM Length L Ch R = 1,948,341,341,341
BEGIN DESCRIPTION:
Mapping XS 7ecd1a86
END DESCRIPTION:
XS GIS Cut Line= 5
      2809128.37     10202856.75      2809177.98     10203139.52
      2809306.98     10203333.02      2809431.01     10203486.82
      2809788.20     10203715.03
#Sta/Elev= 30
  4609.2 1279.26  4646.1 1279.15  4735.4 1275.38  4757.8 1273.32  4849.1 1270.71
  4867.3 1268.87  4982.8 1265.58  5114.2 1263.90  5263.0 1265.56  5275.4 1262.71
  5275.7 1262.21  5279.4 1262.71  5283.8 1264.73  5298.2 1265.38  5478.9 1269.19
  5494.1 1271.59  5545.6 1275.06  5581.2 1275.27  5588.0 1277.10  5645.5 1277.60
  5652.4 1276.43  5660.7 1279.72  5666.7 1279.07  5676.0 1285.77  5681.9 1285.19
  5697.1 1288.34  5711.7 1288.57  5718.3 1290.60  5724.2 1289.48  5750.3 1290.76
#Mann=5,-1,0
  4609.2    0.05       0  4867.3    0.12       0  4982.8    0.05       0
  5275.4    0.03       0  5279.4    0.05       0
Bank Sta=5275.4,5279.4
Exp/Cntr=0.3,0.1

Type RM Length L Ch R = 1,607,401,401,401
BEGIN DESCRIPTION:
Mapping XS 68cef534
END DESCRIPTION:
XS GIS Cut Line= 6
      2809014.26     10203129.63      2809078.75     10203377.67
      2809202.79     10203526.51      2809292.09     10203690.24
      2809401.24     10203888.70      2809614.58     10203978.00
#Sta/Elev= 30
  4605.5 1271.94  4633.0 1270.44  4650.4 1271.28  4714.0 1271.75  4769.8 1269.81
  4789.9 1270.21  4793.5 1269.49  4861.8 1268.26  4906.5 1264.85  4939.1 1263.45
  5019.8 1260.95  5026.3 1261.59  5085.8 1261.41  5097.9 1262.16  5165.6 1261.64
  5176.1 1260.78  5186.4 1258.61  5186.6 1258.11  5190.4 1258.61  5201.4 1261.60
  5342.6 1259.47  5496.7 1259.38  5505.9 1260.54  5515.0 1263.03  5520.5 1262.10
  5527.5 1264.02  5538.4 1264.59  5581.7 1263.79  5621.0 1266.30  5699.8 1269.06
#Mann=7,-1,0
  4605.5    0.05       0  4769.8    0.12       0  4793.5    0.05       0
  4939.1    0.12       0  5176.1    0.05       0  5186.4    0.07       0
  5190.4    0.05       0
Bank Sta=5186.4,5190.4
Exp/Cntr=0.3,0.1

Type RM Length L Ch R = 1,206,0,0,0
BEGIN DESCRIPTION:
Mapping XS c7d83212
END DESCRIPTION:
XS GIS Cut Line= 5
      2808980.68     10203428.08      2809013.38     10203826.17
      2809140.53     10203887.73      2809275.08     10203983.21
      2809542.46     10204060.84
#Sta/Elev= 30
  4547.4 1273.30  4582.5 1271.10  4638.8 1270.20  4662.8 1269.47  4682.9 1270.20
  4714.5 1267.89  4783.2 1266.22  4795.0 1264.86  4923.7 1256.81  4941.0 1256.35
  4953.1 1255.62  4970.1 1256.54  4982.7 1255.33  4992.7 1256.00  4998.3 1257.43
  5047.7 1257.36  5066.0 1257.43  5071.6 1256.45  5167.7 1256.55  5239.9 1256.32
  5244.0 1254.83  5244.2 1254.33  5248.0 1254.83  5250.4 1255.90  5264.1 1257.06
  5280.9 1256.97  5414.6 1260.52  5448.2 1262.43  5481.7 1263.14  5531.5 1266.55
#Mann=9,-1,0
  4547.4    0.05       0  4638.8    0.12       0  4714.5    0.05       0
  4941.0    0.12       0  5047.7    0.05       0  5167.7    0.12       0
  5244.0    0.07       0  5248.0    0.12       0  5280.9    0.05       0
Bank Sta=5244,5248
Exp/Cntr=0.3,0.1

Chan Stop Cuts=-1