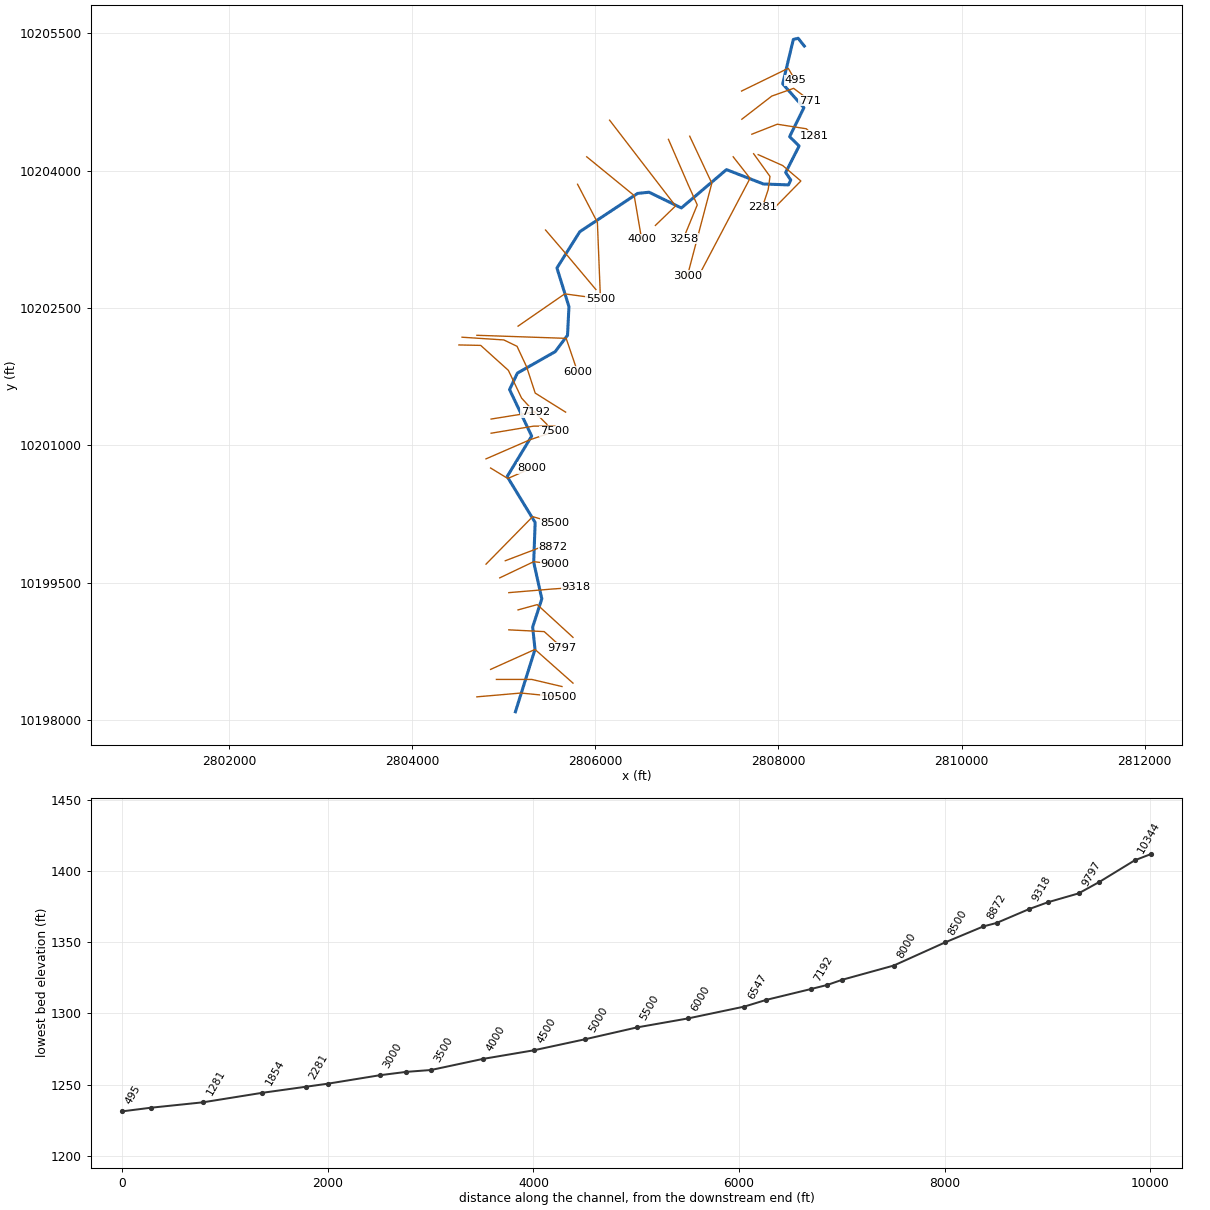
--- SANFERNANDO082.prj (project) ---

Proj Title=SANFERNANDO082 Base Level Engineering
Current Plan=p01
Default Exp/Contr=0.3,0.1
English Units
Geom File=g01
Flow File=f01
Plan File=p01
BEGIN DESCRIPTION:
SANFERNANDO082
END DESCRIPTION:

--- SANFERNANDO082.p01 (plan) ---

Plan Title=Multiple Run
Short Identifier=Multiple
Geom File=g01
Flow File=f01
Subcritical Flow
K Sum by GR= 0
Std Step Tol= 0.01
Critical Tol= 0.01
Num of Std Step Trials= 20
Max Error Tol= 0.3
Flow Tol Ratio= 0.001
Split Flow NTrial= 30
Split Flow Tol= 0.02
Split Flow Ratio= 0.02
Log Output Level= 0
Friction Slope Method= 1
Unsteady Friction Slope Method= 2
Unsteady Bridges Friction Slope Method= 1
Parabolic Critical Depth
Global Vel Dist=  1 , 1 , 1
Global Log Level= 0
CheckData=True
Encroach Param= -1, 0, 0, 0
BEGIN DESCRIPTION:
Multiple Run
END DESCRIPTION:

--- SANFERNANDO082.f01 (steady flow) ---

Flow Title=Multiple
Number of Profiles=7
Profile Names=10-year,25-year,50-year,1pct_min,100-year,1pct_plu,500-year
River Rch & RM= SANFERNANDO082,Reach-1,10500
     404     656    1115     817    1535    2884    2201
River Rch & RM= SANFERNANDO082,Reach-1,1854
     662    1108    1991    1490    2796    5249    4004
Boundary for River Rch & Prof#=SANFERNANDO082,Reach-1,1
Up Type=0
Dn Type=3
Dn Slope=0.005
Boundary for River Rch & Prof#=SANFERNANDO082,Reach-1,2
Up Type=0
Dn Type=3
Dn Slope=0.005
Boundary for River Rch & Prof#=SANFERNANDO082,Reach-1,3
Up Type=0
Dn Type=3
Dn Slope=0.005
Boundary for River Rch & Prof#=SANFERNANDO082,Reach-1,4
Up Type=0
Dn Type=3
Dn Slope=0.005
Boundary for River Rch & Prof#=SANFERNANDO082,Reach-1,5
Up Type=0
Dn Type=3
Dn Slope=0.005
Boundary for River Rch & Prof#=SANFERNANDO082,Reach-1,6
Up Type=0
Dn Type=3
Dn Slope=0.005
Boundary for River Rch & Prof#=SANFERNANDO082,Reach-1,7
Up Type=0
Dn Type=3
Dn Slope=0.005

--- SANFERNANDO082.g01 (geometry) ---

Geom Title=Existing Conditions

River Reach=SANFERNANDO082,Reach-1
Reach XY= 30
      2805126.75     10198090.00      2805340.75     10198772.00
      2805315.00     10199016.00      2805415.25     10199324.00
      2805326.50     10199724.00      2805342.25     10200158.00
      2805036.50     10200660.00      2805304.25     10201102.00
      2805062.75     10201610.00      2805148.50     10201790.00
      2805561.00     10202024.00      2805696.00     10202203.00
      2805711.50     10202516.00      2805580.25     10202938.00
      2805830.25     10203335.00      2806461.50     10203753.00
      2806586.50     10203766.00      2806939.75     10203594.00
      2807432.50     10204013.00      2807835.75     10203856.00
      2808109.25     10203846.00      2808134.50     10203899.00
      2808079.25     10203982.00      2808226.00     10204271.00
      2808122.25     10204373.00      2808278.25     10204689.00
      2808046.50     10204950.00      2808163.00     10205435.00
      2808215.50     10205448.00      2808282.50     10205363.00

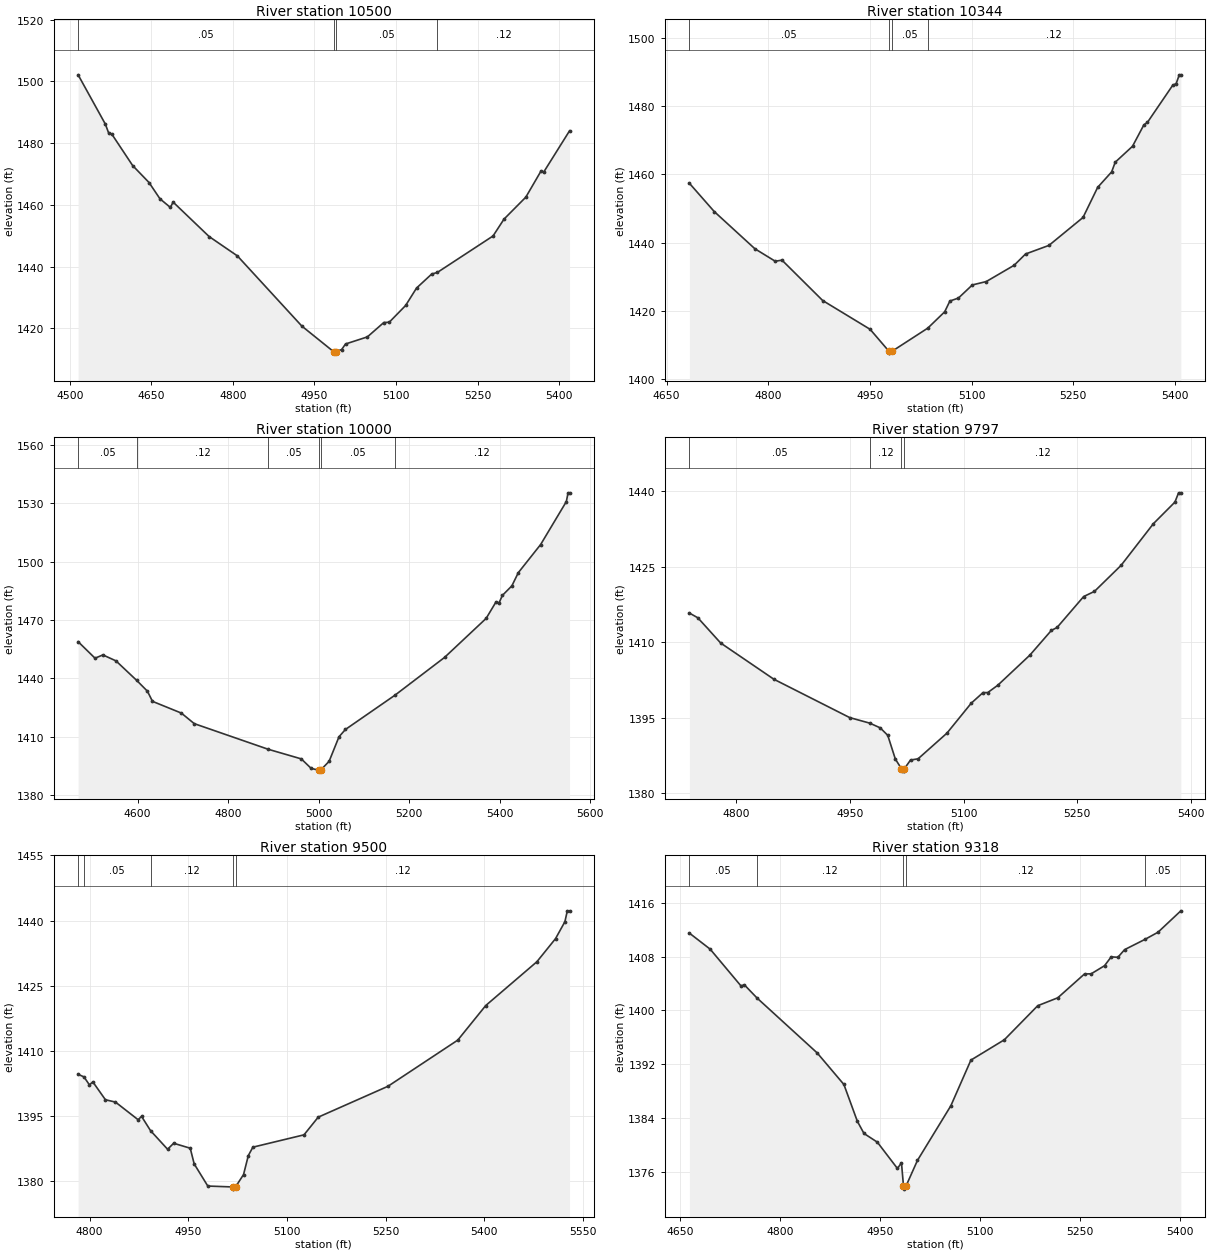
Type RM Length L Ch R = 1,10500,156,156,156
BEGIN DESCRIPTION:
SANFERNANDO082 20.0
END DESCRIPTION:
XS GIS Cut Line= 3
      2804705.73     10198253.12      2805188.53     10198294.91
      2805605.64     10198253.12
#Sta/Elev= 30
  4515.4 1502.13  4565.5 1486.16  4571.9 1483.13  4577.0 1483.02  4615.7 1472.74
  4645.8 1467.25  4665.9 1461.98  4685.1 1459.17  4690.1 1460.91  4756.3 1449.75
  4808.3 1443.48  4926.9 1420.73  4985.1 1412.48  4985.4 1411.98  4989.1 1412.48
  5000.0 1413.13  5007.2 1414.94  5047.4 1417.24  5077.5 1421.88  5087.6 1421.99
  5117.7 1427.41  5137.8 1433.06  5165.7 1437.60  5175.9 1438.10  5278.5 1449.93
  5298.6 1455.38  5338.8 1462.51  5366.5 1470.90  5371.6 1470.61  5419.2 1484.00
#Mann=4,-1,0
  4515.4    0.05       0  4985.1    0.05       0  4989.1    0.05       0
  5175.9    0.12       0
Bank Sta=4985.1,4989.1
Exp/Cntr=0.3,0.1

Type RM Length L Ch R = 1,10344,344,344,344
BEGIN DESCRIPTION:
Mapping XS bdfff3fe
END DESCRIPTION:
XS GIS Cut Line= 3
      2804919.07     10198443.37      2805306.13     10198443.37
      2805635.09     10198365.97
#Sta/Elev= 30
  4683.6 1457.42  4720.2 1449.14  4780.2 1438.23  4810.2 1434.57  4820.2 1434.89
  4880.2 1423.06  4950.2 1414.62  4978.2 1408.14  4978.5 1407.64  4982.2 1408.14
  5035.3 1414.97  5060.2 1419.75  5067.9 1422.91  5080.5 1423.78  5101.0 1427.62
  5121.6 1428.62  5162.7 1433.39  5179.5 1436.69  5214.0 1439.21  5264.3 1447.40
  5285.9 1456.22  5306.5 1460.75  5311.8 1463.59  5337.3 1468.26  5354.1 1474.55
  5359.3 1475.26  5396.5 1486.11  5401.7 1486.63  5406.3 1489.20  5408.6 1489.20
#Mann=4,-1,0
  4683.6    0.05       0  4978.2    0.05       0  4982.2    0.05       0
  5035.3    0.12       0
Bank Sta=4978.2,4982.2
Exp/Cntr=0.3,0.1

Type RM Length L Ch R = 1,10000,203,203,203
BEGIN DESCRIPTION:
SANFERNANDO082 19.0
END DESCRIPTION:
XS GIS Cut Line= 3
      2804855.71     10198553.12      2805340.52     10198771.21
      2805755.65     10198403.14
#Sta/Elev= 30
  4468.4 1458.90  4505.8 1450.41  4523.2 1452.10  4552.1 1449.04  4598.1 1438.97
  4621.6 1433.48  4632.8 1428.26  4696.6 1422.24  4725.2 1416.81  4888.5 1403.67
  4961.8 1398.72  4983.7 1393.82  5000.4 1392.94  5000.7 1392.44  5004.4 1392.94
  5023.3 1397.48  5045.1 1410.07  5059.3 1413.82  5168.9 1431.43  5278.4 1450.80
  5370.4 1470.85  5392.2 1479.30  5398.9 1478.79  5406.4 1482.67  5427.3 1487.56
  5441.5 1494.32  5490.9 1508.78  5547.7 1530.82  5551.5 1535.31  5554.8 1535.31
#Mann=6,-1,0
  4468.4    0.05       0  4598.1    0.12       0  4888.5    0.05       0
  5000.4    0.05       0  5004.4    0.05       0  5168.9    0.12       0
Bank Sta=5000.4,5004.4
Exp/Cntr=0.3,0.1

Type RM Length L Ch R = 1,9797,297,297,297
BEGIN DESCRIPTION:
Mapping XS 62acec84
END DESCRIPTION:
XS GIS Cut Line= 3
      2805054.54     10198985.21      2805441.59     10198965.86
      2805635.12     10198791.69
#Sta/Elev= 30
  4738.6 1415.76  4749.8 1414.81  4779.8 1409.81  4849.9 1402.62  4950.0 1394.99
  4976.4 1393.89  4990.1 1392.96  5000.1 1391.47  5010.1 1386.76  5018.1 1384.86
  5018.4 1384.36  5021.9 1384.36  5022.1 1384.86  5030.1 1386.56  5040.1 1386.81
  5078.1 1391.90  5110.2 1397.86  5125.7 1399.96  5131.9 1399.96  5145.1 1401.41
  5187.4 1407.39  5215.8 1412.31  5223.3 1412.89  5258.4 1419.04  5272.6 1420.06
  5307.7 1425.23  5350.3 1433.51  5378.7 1437.80  5383.5 1439.64  5386.5 1439.64
#Mann=4,-1,0
  4738.6    0.05       0  4976.4    0.12       0  5018.1    0.07       0
  5022.1    0.12       0
Bank Sta=5018.1,5022.1
Exp/Cntr=0.3,0.1

Type RM Length L Ch R = 1,9500,182,182,182
BEGIN DESCRIPTION:
SANFERNANDO082 18.0
END DESCRIPTION:
XS GIS Cut Line= 3
      2805155.65     10199203.10      2805365.26     10199260.77
      2805755.70     10198903.10
#Sta/Elev= 30
  4782.6 1404.61  4791.5 1404.01  4799.8 1402.17  4805.0 1402.86  4824.1 1398.75
  4839.4 1398.21  4873.8 1394.15  4879.0 1394.92  4892.7 1391.63  4918.6 1387.35
  4927.8 1388.73  4953.0 1387.59  4959.0 1383.98  4979.7 1378.88  5017.8 1378.67
  5018.1 1378.17  5021.8 1378.67  5034.0 1381.52  5041.3 1385.90  5048.2 1387.83
  5125.9 1390.67  5147.5 1394.74  5253.5 1401.85  5359.6 1412.48  5402.1 1420.44
  5479.8 1430.52  5508.2 1435.85  5522.4 1439.74  5526.1 1442.25  5529.5 1442.25
#Mann=5,-1,0
  4782.6    0.12       0  4791.5    0.05       0  4892.7    0.12       0
  5017.8    0.07       0  5021.8    0.12       0
Bank Sta=5017.8,5021.8
Exp/Cntr=0.3,0.1

Type RM Length L Ch R = 1,9318,318,318,318
BEGIN DESCRIPTION:
Mapping XS a25016ca
END DESCRIPTION:
XS GIS Cut Line= 3
      2805054.59     10199391.59      2805519.00     10199430.29
      2805789.89     10199449.64
#Sta/Elev= 30
  4664.1 1411.52  4695.3 1409.13  4741.5 1403.66  4746.6 1403.82  4765.7 1401.85
  4855.9 1393.68  4896.0 1388.98  4916.1 1383.52  4926.1 1381.69  4946.2 1380.39
  4976.3 1376.48  4982.4 1377.32  4985.4 1373.90  4985.6 1373.40  4989.4 1373.90
  5006.4 1377.68  5056.5 1385.81  5086.6 1392.61  5136.8 1395.64  5186.9 1400.71
  5217.0 1401.89  5257.1 1405.44  5267.1 1405.46  5287.2 1406.67  5297.2 1407.99
  5307.2 1407.92  5317.3 1409.06  5347.7 1410.58  5367.4 1411.65  5401.7 1414.84
#Mann=5,-1,0
  4664.1    0.05       0  4765.7    0.12       0  4985.4    0.07       0
  4989.4    0.12       0  5347.7    0.05       0
Bank Sta=4985.4,4989.4
Exp/Cntr=0.3,0.1

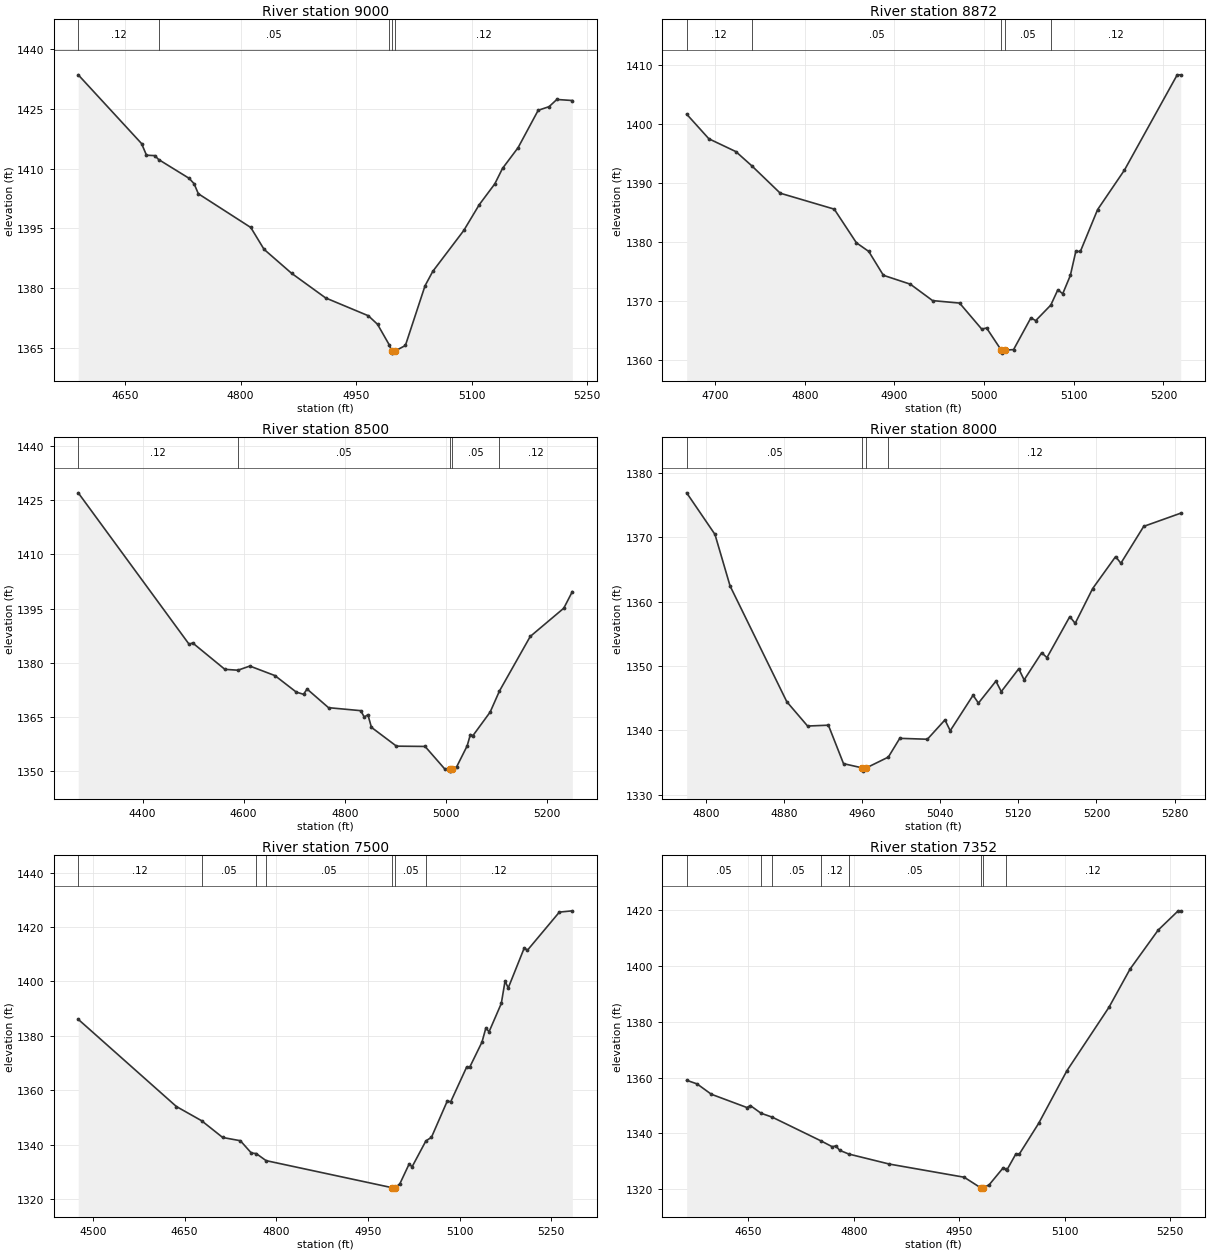
Type RM Length L Ch R = 1,9000,128,128,128
BEGIN DESCRIPTION:
SANFERNANDO082 17.0
END DESCRIPTION:
XS GIS Cut Line= 3
      2804955.67     10199553.11      2805326.47     10199729.69
      2805555.64     10199703.12
#Sta/Elev= 30
  4589.3 1433.59  4671.5 1416.30  4677.9 1413.37  4688.7 1413.27  4693.7 1412.28
  4733.3 1407.55  4739.7 1406.20  4745.2 1403.68  4813.3 1395.19  4830.5 1389.70
  4866.2 1383.68  4910.5 1377.47  4965.9 1372.99  4977.8 1370.85  4993.2 1365.62
  4996.2 1364.09  4996.4 1363.59  5000.2 1364.09  5014.0 1365.51  5039.5 1380.53
  5049.5 1384.14  5089.8 1394.44  5109.9 1400.93  5130.1 1406.17  5140.1 1410.06
  5160.3 1415.27  5186.4 1424.67  5200.5 1425.58  5210.6 1427.39  5230.7 1427.13
#Mann=5,-1,0
  4589.3    0.12       0  4693.7    0.05       0  4993.2    0.12       0
  4996.2    0.07       0  5000.2    0.12       0
Bank Sta=4996.2,5000.2
Exp/Cntr=0.3,0.1

Type RM Length L Ch R = 1,8872,372,372,372
BEGIN DESCRIPTION:
Mapping XS e8474659
END DESCRIPTION:
XS GIS Cut Line= 3
      2805015.86     10199739.91      2805422.24     10199894.73
      2805538.37     10199894.73
#Sta/Elev= 30
  4668.3 1401.68  4693.1 1397.50  4723.2 1395.33  4740.9 1392.93  4772.7 1388.28
  4832.9 1385.58  4857.6 1379.88  4871.4 1378.41  4887.7 1374.37  4917.8 1372.86
  4942.6 1370.08  4972.7 1369.66  4997.4 1365.25  5002.8 1365.44  5019.2 1361.68
  5019.5 1361.18  5023.2 1361.68  5032.9 1361.78  5052.2 1367.15  5057.6 1366.69
  5074.4 1369.32  5082.3 1371.92  5087.7 1371.24  5096.2 1374.34  5102.3 1378.41
  5107.4 1378.41  5126.6 1385.50  5156.6 1392.21  5215.4 1408.34  5219.3 1408.34
#Mann=5,-1,0
  4668.3    0.12       0  4740.9    0.05       0  5019.2    0.05       0
  5023.2    0.05       0  5074.4    0.12       0
Bank Sta=5019.2,5023.2
Exp/Cntr=0.3,0.1

Type RM Length L Ch R = 1,8500,500,500,500
BEGIN DESCRIPTION:
SANFERNANDO082 16.0
END DESCRIPTION:
XS GIS Cut Line= 3
      2804805.66     10199703.08      2805315.19     10200221.78
      2805555.68     10200153.11
#Sta/Elev= 30
  4272.9 1427.05  4492.2 1385.09  4499.2 1385.47  4562.9 1378.15  4588.7 1377.91
  4612.3 1379.06  4661.9 1376.42  4704.3 1371.83  4718.5 1371.24  4725.5 1372.69
  4767.9 1367.53  4831.6 1366.70  4838.6 1364.93  4845.8 1365.58  4852.8 1362.08
  4902.3 1356.87  4958.9 1356.79  4997.4 1350.61  5007.5 1350.45  5007.8 1349.95
  5011.5 1350.45  5021.3 1351.13  5042.1 1356.94  5048.5 1360.08  5053.7 1359.82
  5087.6 1366.31  5106.0 1372.15  5166.9 1387.26  5233.2 1395.08  5250.1 1399.68
#Mann=5,-1,0
  4272.9    0.12       0  4588.7    0.05       0  5007.5    0.05       0
  5011.5    0.05       0  5106.0    0.12       0
Bank Sta=5007.5,5011.5
Exp/Cntr=0.3,0.1

Type RM Length L Ch R = 1,8000,500,500,500
BEGIN DESCRIPTION:
SANFERNANDO082 15.0
END DESCRIPTION:
XS GIS Cut Line= 3
      2804855.69     10200753.11      2805043.32     10200638.61
      2805305.72     10200753.13
#Sta/Elev= 30
  4780.2 1376.87  4809.2 1370.42  4824.7 1362.41  4882.8 1344.44  4904.1 1340.67
  4925.4 1340.80  4940.9 1334.83  4960.2 1334.17  4960.4 1333.67  4964.2 1334.17
  4986.8 1335.85  4998.5 1338.76  5026.8 1338.62  5044.8 1341.62  5050.2 1339.94
  5073.6 1345.45  5079.1 1344.23  5097.0 1347.64  5102.5 1346.02  5120.4 1349.56
  5125.9 1347.83  5143.9 1352.05  5149.3 1351.29  5172.7 1357.66  5178.2 1356.61
  5196.1 1362.01  5219.6 1366.97  5225.0 1365.94  5248.4 1371.66  5286.3 1373.71
#Mann=4,-1,0
  4780.2    0.05       0  4960.2    0.07       0  4964.2    0.05       0
  4986.8    0.12       0
Bank Sta=4960.2,4964.2
Exp/Cntr=0.3,0.1

Type RM Length L Ch R = 1,7500,148,148,148
BEGIN DESCRIPTION:
SANFERNANDO082 14.0
END DESCRIPTION:
XS GIS Cut Line= 3
      2804805.66     10200853.10      2805286.24     10201061.95
      2805555.73     10201153.13
#Sta/Elev= 30
  4476.0 1386.08  4636.6 1354.05  4677.8 1348.84  4712.4 1342.67  4741.3 1341.48
  4759.3 1336.96  4767.2 1336.77  4783.4 1334.17  4990.2 1324.20  4990.4 1323.70
  4994.2 1324.20  5002.3 1325.67  5017.2 1332.81  5022.5 1331.99  5044.9 1341.42
  5054.0 1342.74  5080.1 1356.17  5085.4 1355.74  5111.6 1368.55  5116.8 1368.59
  5136.7 1377.73  5143.0 1382.86  5148.3 1381.53  5168.3 1391.91  5174.4 1400.09
  5179.7 1397.63  5205.9 1412.32  5211.1 1411.47  5263.3 1425.47  5284.5 1425.94
#Mann=7,-1,0
  4476.0    0.12       0  4677.8    0.05       0  4767.2    0.12       0
  4783.4    0.05       0  4990.2    0.03       0  4994.2    0.05       0
  5044.9    0.12       0
Bank Sta=4990.2,4994.2
Exp/Cntr=0.3,0.1

Type RM Length L Ch R = 1,7352,160,160,160
BEGIN DESCRIPTION:
Mapping XS 23f82b9e
END DESCRIPTION:
XS GIS Cut Line= 3
      2804861.06     10201133.22      2805325.48     10201210.63
      2805557.75     10201210.63
#Sta/Elev= 30
  4562.1 1359.04  4576.9 1357.75  4597.2 1354.04  4647.8 1349.28  4652.8 1349.97
  4668.0 1347.22  4683.9 1345.82  4753.9 1337.23  4769.4 1335.20  4774.5 1335.54
  4779.7 1333.95  4793.0 1332.58  4850.7 1328.99  4957.0 1324.28  4980.4 1320.51
  4980.7 1320.01  4984.4 1320.51  4992.6 1321.56  5012.7 1327.69  5015.9 1327.17
  5017.8 1326.86  5030.5 1332.58  5035.5 1332.58  5063.1 1343.62  5103.1 1362.41
  5163.1 1385.22  5193.1 1398.92  5233.1 1412.90  5261.6 1419.81  5265.2 1419.81
#Mann=8,-1,0
  4562.1    0.05       0  4668.0    0.12       0  4683.9    0.05       0
  4753.9    0.12       0  4793.0    0.05       0  4980.4    0.03       0
  4984.4    0.05       0  5015.9    0.12       0
Bank Sta=4980.4,4984.4
Exp/Cntr=0.3,0.1

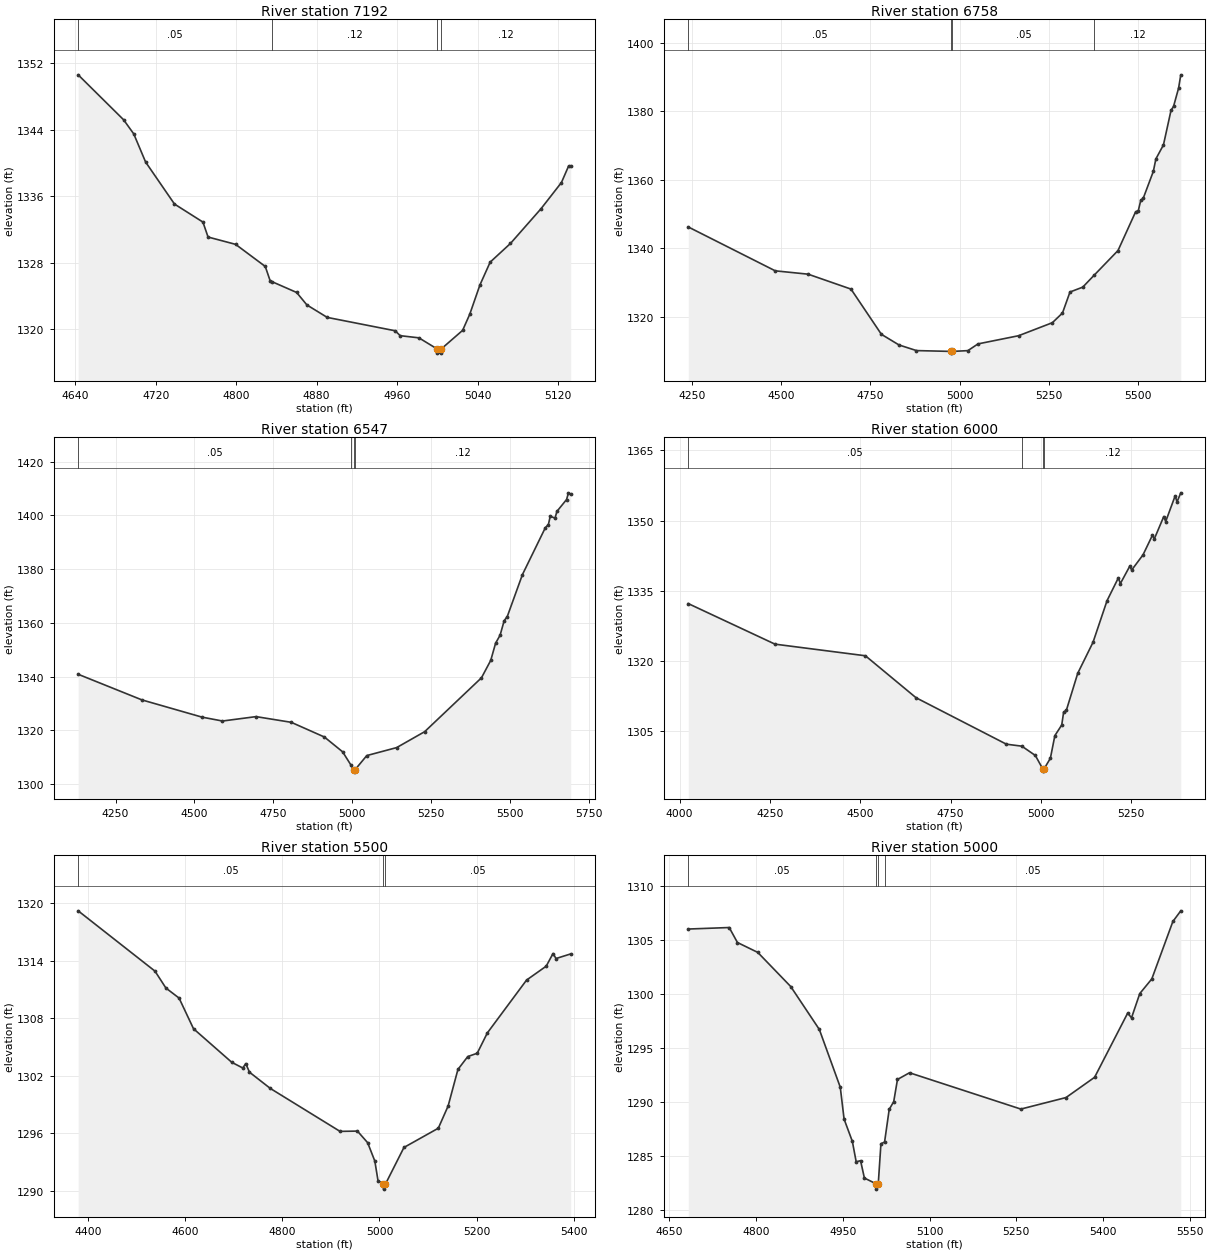
Type RM Length L Ch R = 1,7192,434,434,434
BEGIN DESCRIPTION:
Mapping XS 59acccdc
END DESCRIPTION:
XS GIS Cut Line= 2
      2804861.06     10201288.03      2805344.81     10201365.43
#Sta/Elev= 30
  4642.8 1350.61  4688.0 1345.20  4698.1 1343.50  4709.9 1340.11  4738.6 1335.06
  4766.9 1332.89  4772.0 1331.09  4799.4 1330.21  4828.9 1327.55  4834.0 1325.74
  4835.4 1325.73  4860.1 1324.42  4870.3 1322.92  4890.5 1321.42  4958.1 1319.81
  4963.1 1319.22  4981.7 1318.96  4999.9 1317.62  5000.2 1317.12  5003.7 1317.12
  5003.9 1317.62  5025.2 1319.86  5032.3 1321.80  5042.4 1325.32  5052.6 1328.07
  5072.8 1330.32  5103.2 1334.50  5123.5 1337.65  5130.6 1339.63  5132.7 1339.63
#Mann=4,-1,0
  4642.8    0.05       0  4835.4    0.12       0  4999.9    0.07       0
  5003.9    0.12       0
Bank Sta=4999.9,5003.9
Exp/Cntr=0.3,0.1

Type RM Length L Ch R = 1,6758,211,211,211
BEGIN DESCRIPTION:
Mapping XS 09ea794c
END DESCRIPTION:
XS GIS Cut Line= 6
      2804509.30     10202097.62      2804747.43     10202092.66
      2805050.07     10201819.78      2805193.96     10201517.14
      2805298.15     10201403.02      2805471.23     10201229.93
#Sta/Elev= 30
  4239.8 1346.27  4483.6 1333.48  4575.5 1332.51  4695.8 1328.16  4781.0 1314.98
  4830.3 1311.88  4879.3 1310.24  4976.0 1310.00  4976.2 1309.50  4980.0 1310.00
  5023.4 1310.23  5051.7 1312.19  5165.3 1314.57  5260.1 1318.37  5288.4 1321.19
  5309.4 1327.31  5345.2 1328.73  5377.9 1332.29  5444.0 1339.40  5493.5 1350.72
  5500.6 1350.90  5507.7 1354.00  5514.7 1354.63  5543.0 1362.47  5550.1 1366.10
  5571.3 1370.17  5592.5 1380.23  5599.6 1381.39  5613.7 1386.71  5619.9 1390.60
#Mann=4,-1,0
  4239.8    0.05       0  4976.0    0.03       0  4980.0    0.05       0
  5377.9    0.12       0
Bank Sta=4976,4980
Exp/Cntr=0.3,0.1

Type RM Length L Ch R = 1,6547,547,547,547
BEGIN DESCRIPTION:
Mapping XS 9541685a
END DESCRIPTION:
XS GIS Cut Line= 6
      2804544.00     10202181.97      2805000.46     10202152.20
      2805144.34     10202082.74      2805248.53     10201859.47
      2805342.80     10201571.71      2805675.20     10201363.34
#Sta/Elev= 30
  4131.5 1340.88  4333.6 1331.34  4524.0 1324.93  4588.9 1323.48  4695.3 1325.12
  4806.9 1323.00  4911.9 1317.53  4969.7 1312.02  4995.5 1307.20  5004.9 1305.33
  5005.2 1304.83  5008.9 1305.33  5046.3 1310.62  5141.0 1313.59  5229.8 1319.52
  5409.8 1339.57  5439.2 1346.06  5454.6 1352.47  5468.8 1355.41  5481.7 1360.81
  5491.6 1362.38  5539.6 1377.98  5612.4 1395.48  5621.8 1396.56  5627.7 1399.68
  5643.0 1399.02  5648.9 1401.50  5679.5 1405.93  5685.5 1408.42  5692.6 1407.95
#Mann=4,-1,0
  4131.5    0.05       0  4995.5    0.12       0  5004.9    0.07       0
  5008.9    0.12       0
Bank Sta=5004.9,5008.9
Exp/Cntr=0.3,0.1

Type RM Length L Ch R = 1,6000,500,500,500
BEGIN DESCRIPTION:
SANFERNANDO082 11.0
END DESCRIPTION:
XS GIS Cut Line= 3
      2804705.68     10202203.11      2805681.11     10202169.64
      2805805.68     10201803.13
#Sta/Elev= 30
  4024.0 1332.29  4264.1 1323.63  4514.3 1321.15  4654.4 1312.19  4904.5 1302.27
  4947.2 1301.85  4984.6 1299.86  5004.9 1297.02  5005.1 1296.52  5008.9 1297.02
  5026.2 1299.27  5038.6 1304.10  5057.6 1306.37  5062.9 1309.13  5070.3 1309.48
  5101.9 1317.41  5144.2 1324.03  5183.1 1332.93  5214.5 1337.81  5219.8 1336.55
  5245.9 1340.28  5251.2 1339.46  5282.6 1342.70  5308.7 1346.90  5313.9 1346.12
  5340.0 1350.88  5345.3 1349.81  5371.4 1355.27  5376.7 1354.02  5387.1 1355.94
#Mann=4,-1,0
  4024.0    0.05       0  4947.2    0.12       0  5004.9    0.07       0
  5008.9    0.12       0
Bank Sta=5004.9,5008.9
Exp/Cntr=0.3,0.1

Type RM Length L Ch R = 1,5500,500,500,500
BEGIN DESCRIPTION:
SANFERNANDO082 10.0
END DESCRIPTION:
XS GIS Cut Line= 3
      2805155.64     10202303.08      2805665.65     10202655.47
      2806055.65     10202603.12
#Sta/Elev= 30
  4380.1 1319.22  4538.2 1312.92  4560.6 1311.16  4587.7 1310.11  4617.4 1306.91
  4696.2 1303.40  4718.8 1302.81  4724.9 1303.27  4732.6 1302.37  4775.6 1300.67
  4918.9 1296.19  4954.7 1296.22  4975.7 1295.01  4990.5 1293.09  4997.0 1291.06
  5008.1 1290.66  5008.4 1290.16  5012.1 1290.66  5050.4 1294.51  5121.1 1296.52
  5141.3 1298.84  5161.5 1302.66  5181.7 1304.00  5201.2 1304.35  5222.0 1306.47
  5302.7 1311.99  5343.1 1313.44  5357.1 1314.76  5363.3 1314.24  5393.5 1314.72
#Mann=3,-1,0
  4380.1    0.05       0  5008.1    0.05       0  5012.1    0.05       0
Bank Sta=5008.1,5012.1
Exp/Cntr=0.3,0.1

Type RM Length L Ch R = 1,5000,500,500,500
BEGIN DESCRIPTION:
SANFERNANDO082 9.0
END DESCRIPTION:
XS GIS Cut Line= 3
      2805455.70     10203353.10      2805662.24     10203112.36
      2806005.71     10202703.08
#Sta/Elev= 30
  4682.8 1306.04  4753.6 1306.18  4767.8 1304.79  4803.0 1303.87  4860.0 1300.70
  4909.4 1296.72  4945.6 1291.36  4952.2 1288.40  4966.5 1286.33  4973.1 1284.44
  4980.7 1284.54  4987.3 1282.93  5007.3 1282.40  5007.6 1281.90  5011.3 1282.40
  5015.9 1286.11  5022.2 1286.27  5030.2 1289.30  5038.0 1290.02  5044.5 1292.08
  5065.3 1292.70  5257.8 1289.33  5335.9 1290.40  5385.3 1292.28  5442.5 1298.24
  5449.1 1297.80  5463.4 1300.05  5484.2 1301.41  5520.6 1306.74  5534.3 1307.73
#Mann=4,-1,0
  4682.8    0.05       0  5007.3    0.05       0  5011.3    0.05       0
  5022.2    0.05       0
Bank Sta=5007.3,5011.3
Exp/Cntr=0.3,0.1

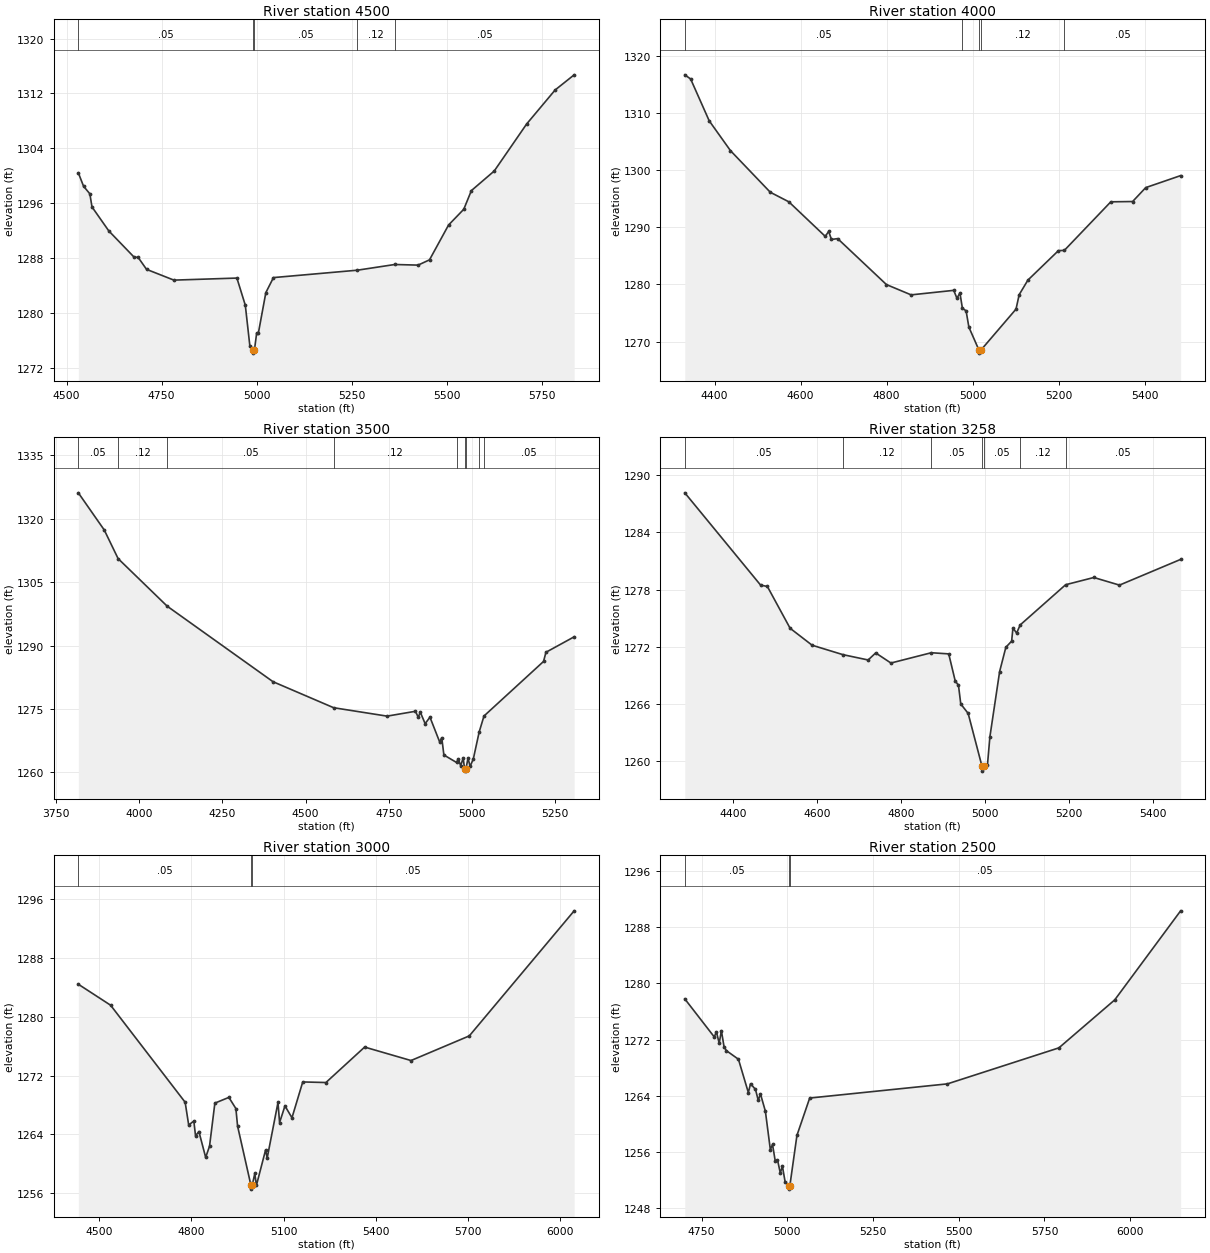
Type RM Length L Ch R = 1,4500,500,500,500
BEGIN DESCRIPTION:
SANFERNANDO082 8.0
END DESCRIPTION:
XS GIS Cut Line= 3
      2805805.70     10203853.09      2806022.24     10203437.18
      2806055.68     10202603.15
#Sta/Elev= 30
  4531.1 1300.42  4544.9 1298.46  4561.4 1297.36  4567.0 1295.45  4611.2 1291.95
  4677.6 1288.13  4688.4 1288.08  4710.5 1286.34  4782.4 1284.77  4948.0 1285.07
  4970.1 1281.11  4982.0 1275.21  4990.2 1274.62  4990.4 1274.12  4994.2 1274.62
  5000.0 1277.06  5004.5 1277.06  5024.1 1282.95  5044.1 1285.14  5264.9 1286.22
  5363.1 1287.05  5424.4 1286.96  5454.4 1287.73  5504.5 1292.81  5544.5 1295.11
  5564.5 1297.83  5624.6 1300.69  5709.8 1307.55  5784.7 1312.51  5834.7 1314.72
#Mann=5,-1,0
  4531.1    0.05       0  4990.2    0.05       0  4994.2    0.05       0
  5264.9    0.12       0  5363.1    0.05       0
Bank Sta=4990.2,4994.2
Exp/Cntr=0.3,0.1

Type RM Length L Ch R = 1,4000,500,500,500
BEGIN DESCRIPTION:
SANFERNANDO082 7.0
END DESCRIPTION:
XS GIS Cut Line= 3
      2805905.70     10204153.10      2806424.04     10203729.67
      2806505.68     10203253.12
#Sta/Elev= 30
  4330.7 1316.63  4344.3 1315.90  4387.4 1308.60  4436.9 1303.38  4529.5 1296.11
  4572.6 1294.44  4657.3 1288.40  4665.2 1289.27  4671.7 1287.86  4686.1 1288.01
  4799.5 1279.98  4856.9 1278.18  4956.0 1278.97  4963.4 1277.59  4970.4 1278.52
  4976.1 1275.85  4984.7 1275.39  4991.2 1272.54  5014.8 1268.50  5015.1 1268.00
  5018.8 1268.50  5100.8 1275.69  5108.1 1278.21  5128.4 1280.76  5199.4 1285.91
  5213.1 1285.95  5321.2 1294.44  5371.9 1294.49  5402.3 1296.92  5483.5 1299.02
#Mann=5,-1,0
  4330.7    0.05       0  4976.1    0.12       0  5014.8    0.07       0
  5018.8    0.12       0  5213.1    0.05       0
Bank Sta=5014.8,5018.8
Exp/Cntr=0.3,0.1

Type RM Length L Ch R = 1,3500,242,242,242
BEGIN DESCRIPTION:
SANFERNANDO082 6.0
END DESCRIPTION:
XS GIS Cut Line= 3
      2806155.68     10204553.12      2806876.23     10203616.01
      2806655.72     10203403.14
#Sta/Elev= 30
  3817.9 1326.16  3895.8 1317.35  3937.3 1310.59  4084.7 1299.32  4402.4 1281.44
  4584.5 1275.28  4744.9 1273.29  4830.1 1274.44  4838.3 1273.03  4844.6 1274.23
  4859.1 1271.51  4873.6 1273.04  4902.7 1267.18  4909.0 1268.18  4915.4 1264.09
  4953.4 1262.32  4958.8 1263.16  4965.8 1261.53  4973.3 1263.39  4977.6 1260.77
  4977.9 1260.27  4981.6 1260.77  4987.8 1263.37  4994.1 1261.37  5003.9 1263.20
  5021.4 1269.56  5035.8 1273.32  5214.6 1286.24  5221.8 1288.41  5306.5 1292.07
#Mann=9,-1,0
  3817.9    0.05       0  3937.3    0.12       0  4084.7    0.05       0
  4584.5    0.12       0  4953.4    0.05       0  4977.6    0.05       0
  4981.6    0.05       0  5021.4    0.12       0  5035.8    0.05       0
Bank Sta=4977.6,4981.6
Exp/Cntr=0.3,0.1

Type RM Length L Ch R = 1,3258,258,258,258
BEGIN DESCRIPTION:
Mapping XS 2ffc2bdc
END DESCRIPTION:
XS GIS Cut Line= 4
      2806798.58     10204343.49      2807015.61     10203844.32
      2807113.26     10203627.31      2806961.33     10203258.34
#Sta/Elev= 30
  4284.4 1288.16  4465.0 1278.47  4481.1 1278.33  4535.3 1273.94  4587.7 1272.16
  4661.1 1271.17  4721.2 1270.61  4739.2 1271.35  4775.5 1270.29  4871.7 1271.37
  4913.2 1271.25  4928.7 1268.40  4936.4 1267.96  4941.9 1265.99  4959.5 1265.00
  4992.5 1259.44  4992.8 1258.94  4996.5 1259.44  5005.5 1259.60  5011.3 1262.55
  5034.5 1269.40  5049.3 1271.94  5063.1 1272.59  5066.2 1273.96  5075.0 1273.44
  5083.5 1274.29  5191.7 1278.51  5258.9 1279.27  5320.0 1278.47  5465.7 1281.17
#Mann=7,-1,0
  4284.4    0.05       0  4661.1    0.12       0  4871.7    0.05       0
  4992.5    0.05       0  4996.5    0.05       0  5083.5    0.12       0
  5191.7    0.05       0
Bank Sta=4992.5,4996.5
Exp/Cntr=0.3,0.1

Type RM Length L Ch R = 1,3000,500,500,500
BEGIN DESCRIPTION:
SANFERNANDO082 5.0
END DESCRIPTION:
XS GIS Cut Line= 3
      2807030.68     10204378.11      2807272.33     10203864.08
      2807005.69     10202853.15
#Sta/Elev= 30
  4432.0 1284.42  4537.0 1281.57  4779.6 1268.38  4791.1 1265.29  4807.9 1265.82
  4813.4 1263.81  4824.3 1264.40  4846.4 1260.88  4859.0 1262.42  4876.3 1268.26
  4921.9 1269.04  4944.7 1267.52  4950.2 1265.14  4993.8 1257.07  4994.1 1256.57
  4997.8 1257.07  5006.3 1258.70  5011.5 1257.08  5041.4 1261.90  5046.6 1260.80
  5081.7 1268.35  5086.9 1265.62  5104.4 1267.88  5127.2 1266.27  5162.3 1271.14
  5237.7 1271.06  5363.7 1275.88  5514.6 1274.05  5704.3 1277.40  6045.5 1294.40
#Mann=3,-1,0
  4432.0    0.05       0  4993.8    0.05       0  4997.8    0.05       0
Bank Sta=4993.8,4997.8
Exp/Cntr=0.3,0.1

Type RM Length L Ch R = 1,2500,219,219,219
BEGIN DESCRIPTION:
SANFERNANDO082 4.0
END DESCRIPTION:
XS GIS Cut Line= 3
      2807505.68     10204153.12      2807690.11     10203918.16
      2807155.70     10202903.15
#Sta/Elev= 30
  4701.3 1277.80  4787.2 1272.38  4793.5 1273.11  4801.6 1271.48  4808.0 1273.27
  4815.7 1271.00  4822.4 1270.43  4857.7 1269.20  4886.6 1264.45  4893.0 1265.71
  4907.4 1264.90  4915.5 1263.34  4921.9 1264.26  4936.3 1261.79  4950.8 1256.30
  4957.1 1257.06  4965.2 1254.64  4971.6 1254.87  4979.7 1253.00  4986.0 1253.93
  4993.7 1251.77  5003.7 1251.19  5004.0 1250.69  5007.7 1251.19  5028.3 1258.35
  5065.5 1263.67  5467.2 1265.69  5792.1 1270.82  5955.0 1277.66  6147.1 1290.35
#Mann=3,-1,0
  4701.3    0.05       0  5003.7    0.05       0  5007.7    0.05       0
Bank Sta=5003.7,5007.7
Exp/Cntr=0.3,0.1

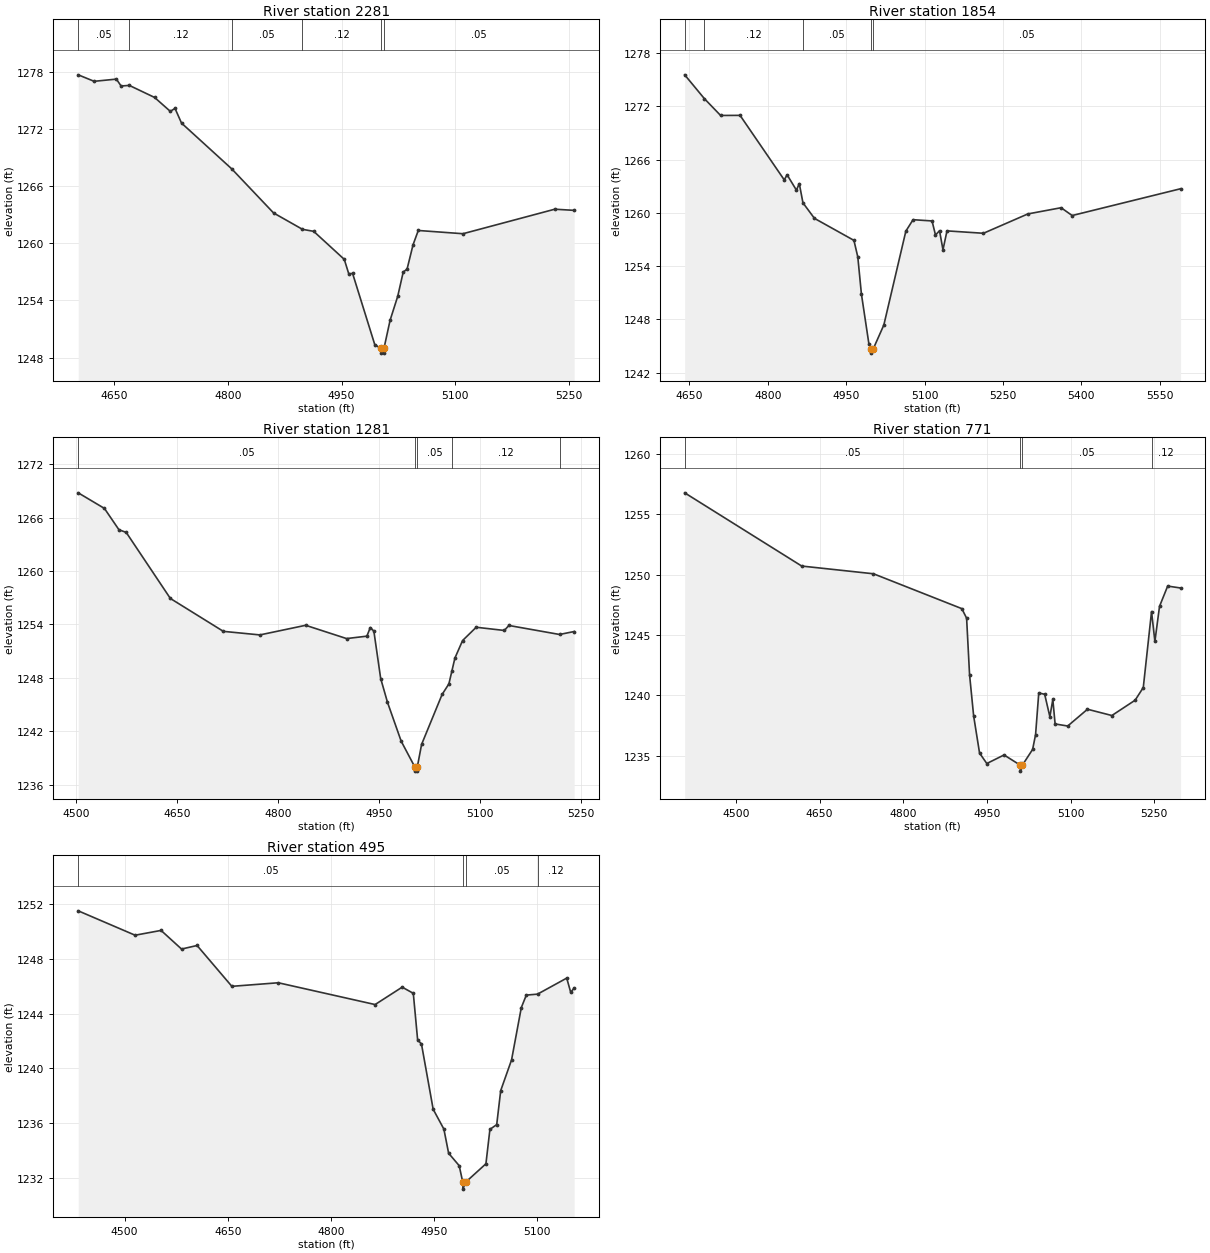
Type RM Length L Ch R = 1,2281,427,427,427
BEGIN DESCRIPTION:
Mapping XS 7d53d97f
END DESCRIPTION:
XS GIS Cut Line= 4
      2807729.27     10204186.34      2807907.85     10203938.31
      2807888.01     10203794.43      2807823.52     10203600.97
#Sta/Elev= 30
  4602.3 1277.66  4623.3 1276.98  4652.7 1277.21  4658.9 1276.49  4669.8 1276.55
  4703.1 1275.29  4723.9 1273.83  4730.1 1274.14  4738.7 1272.60  4805.0 1267.80
  4860.2 1263.18  4898.4 1261.46  4913.2 1261.25  4953.6 1258.31  4959.5 1256.80
  4964.6 1256.83  4993.9 1249.36  5002.0 1248.98  5002.3 1248.48  5005.8 1248.48
  5006.0 1248.98  5014.1 1251.93  5024.2 1254.45  5031.4 1256.98  5036.5 1257.29
  5044.4 1259.84  5051.3 1261.34  5110.3 1261.00  5231.5 1263.57  5257.1 1263.45
#Mann=6,-1,0
  4602.3    0.05       0  4669.8    0.12       0  4805.0    0.05       0
  4898.4    0.12       0  5002.0    0.07       0  5006.0    0.05       0
Bank Sta=5002,5006
Exp/Cntr=0.3,0.1

Type RM Length L Ch R = 1,1854,573,573,573
BEGIN DESCRIPTION:
Mapping XS 86dfe2b2
END DESCRIPTION:
XS GIS Cut Line= 4
      2807778.89     10204176.45      2808046.77     10204057.39
      2808245.23     10203888.70      2807968.49     10203607.01
#Sta/Elev= 30
  4641.2 1275.56  4678.8 1272.88  4709.9 1270.98  4747.1 1270.99  4831.6 1263.72
  4837.1 1264.29  4854.9 1262.56  4860.4 1263.30  4867.4 1261.13  4889.4 1259.38
  4964.9 1256.90  4972.3 1255.03  4979.2 1250.86  4993.5 1245.24  4998.0 1244.69
  4998.3 1244.19  5002.0 1244.69  5022.1 1247.36  5064.2 1257.94  5078.0 1259.23
  5114.3 1259.09  5120.9 1257.50  5128.6 1257.99  5135.2 1255.84  5142.9 1257.97
  5212.6 1257.70  5297.5 1259.88  5361.1 1260.58  5382.3 1259.70  5589.7 1262.72
#Mann=5,-1,0
  4641.2    0.05       0  4678.8    0.12       0  4867.4    0.05       0
  4998.0    0.05       0  5002.0    0.05       0
Bank Sta=4998,5002
Exp/Cntr=0.3,0.1

Type RM Length L Ch R = 1,1281,510,510,510
BEGIN DESCRIPTION:
Mapping XS e1e2723e
END DESCRIPTION:
XS GIS Cut Line= 4
      2807709.43     10204399.74      2807987.24     10204508.88
      2808304.77     10204459.26      2808389.13     10204379.87
#Sta/Elev= 30
  4503.7 1268.77  4542.6 1267.02  4564.1 1264.63  4574.9 1264.33  4640.4 1256.92
  4719.0 1253.23  4773.2 1252.83  4841.1 1253.91  4901.8 1252.42  4931.9 1252.69
  4937.0 1253.66  4942.3 1253.25  4952.4 1247.94  4962.5 1245.27  4982.8 1240.91
  5002.8 1238.05  5003.0 1237.55  5006.5 1237.55  5006.8 1238.05  5013.1 1240.55
  5043.5 1246.15  5053.6 1247.34  5058.0 1248.77  5062.5 1250.23  5073.9 1252.20
  5094.1 1253.69  5135.8 1253.33  5142.6 1253.89  5217.7 1252.88  5239.4 1253.21
#Mann=5,-1,0
  4503.7    0.05       0  5002.8    0.05       0  5006.8    0.05       0
  5058.0    0.12       0  5217.7    0.05       0
Bank Sta=5002.8,5006.8
Exp/Cntr=0.3,0.1

Type RM Length L Ch R = 1,771,276,276,276
BEGIN DESCRIPTION:
Mapping XS 9c2de4b9
END DESCRIPTION:
XS GIS Cut Line= 4
      2807600.23     10204563.44      2807927.70     10204816.48
      2808165.85     10204900.83      2808343.62     10204767.50
#Sta/Elev= 30
  4408.4 1256.79  4618.1 1250.72  4746.7 1250.08  4905.0 1247.19  4913.6 1246.40
  4918.9 1241.71  4926.2 1238.30  4936.8 1235.22  4949.8 1234.35  4980.7 1235.06
  5009.6 1234.22  5009.9 1233.72  5013.6 1234.22  5031.9 1235.52  5037.2 1236.75
  5042.9 1240.20  5053.5 1240.09  5062.8 1238.23  5068.1 1239.66  5072.2 1237.63
  5094.8 1237.46  5130.2 1238.85  5173.9 1238.33  5215.6 1239.60  5230.2 1240.65
  5245.0 1246.95  5251.0 1244.47  5259.3 1247.38  5273.9 1249.06  5297.1 1248.90
#Mann=4,-1,0
  4408.4    0.05       0  5009.6    0.05       0  5013.6    0.05       0
  5245.0    0.12       0
Bank Sta=5009.6,5013.6
Exp/Cntr=0.3,0.1

Type RM Length L Ch R = 1,495,0,0,0
BEGIN DESCRIPTION:
SANFERNANDO082 2.0
END DESCRIPTION:
XS GIS Cut Line= 3
      2807597.27     10204871.33      2808107.50     10205120.00
      2808184.86     10204986.61
#Sta/Elev= 30
  4432.4 1251.50  4515.2 1249.72  4553.0 1250.07  4582.8 1248.71  4605.4 1248.97
  4656.0 1245.99  4723.6 1246.25  4864.5 1244.66  4903.9 1245.93  4920.1 1245.48
  4926.4 1242.08  4932.0 1241.78  4949.0 1237.02  4964.6 1235.57  4971.5 1233.81
  4986.9 1232.90  4992.1 1231.69  4992.3 1231.19  4996.1 1231.69  5025.8 1233.04
  5031.6 1235.55  5041.5 1235.90  5047.3 1238.38  5063.1 1240.62  5077.3 1244.44
  5084.6 1245.35  5100.9 1245.42  5143.4 1246.59  5149.2 1245.55  5154.2 1245.87
#Mann=4,-1,0
  4432.4    0.05       0  4992.1    0.03       0  4996.1    0.05       0
  5100.9    0.12       0
Bank Sta=4992.1,4996.1
Exp/Cntr=0.3,0.1

Chan Stop Cuts=-1