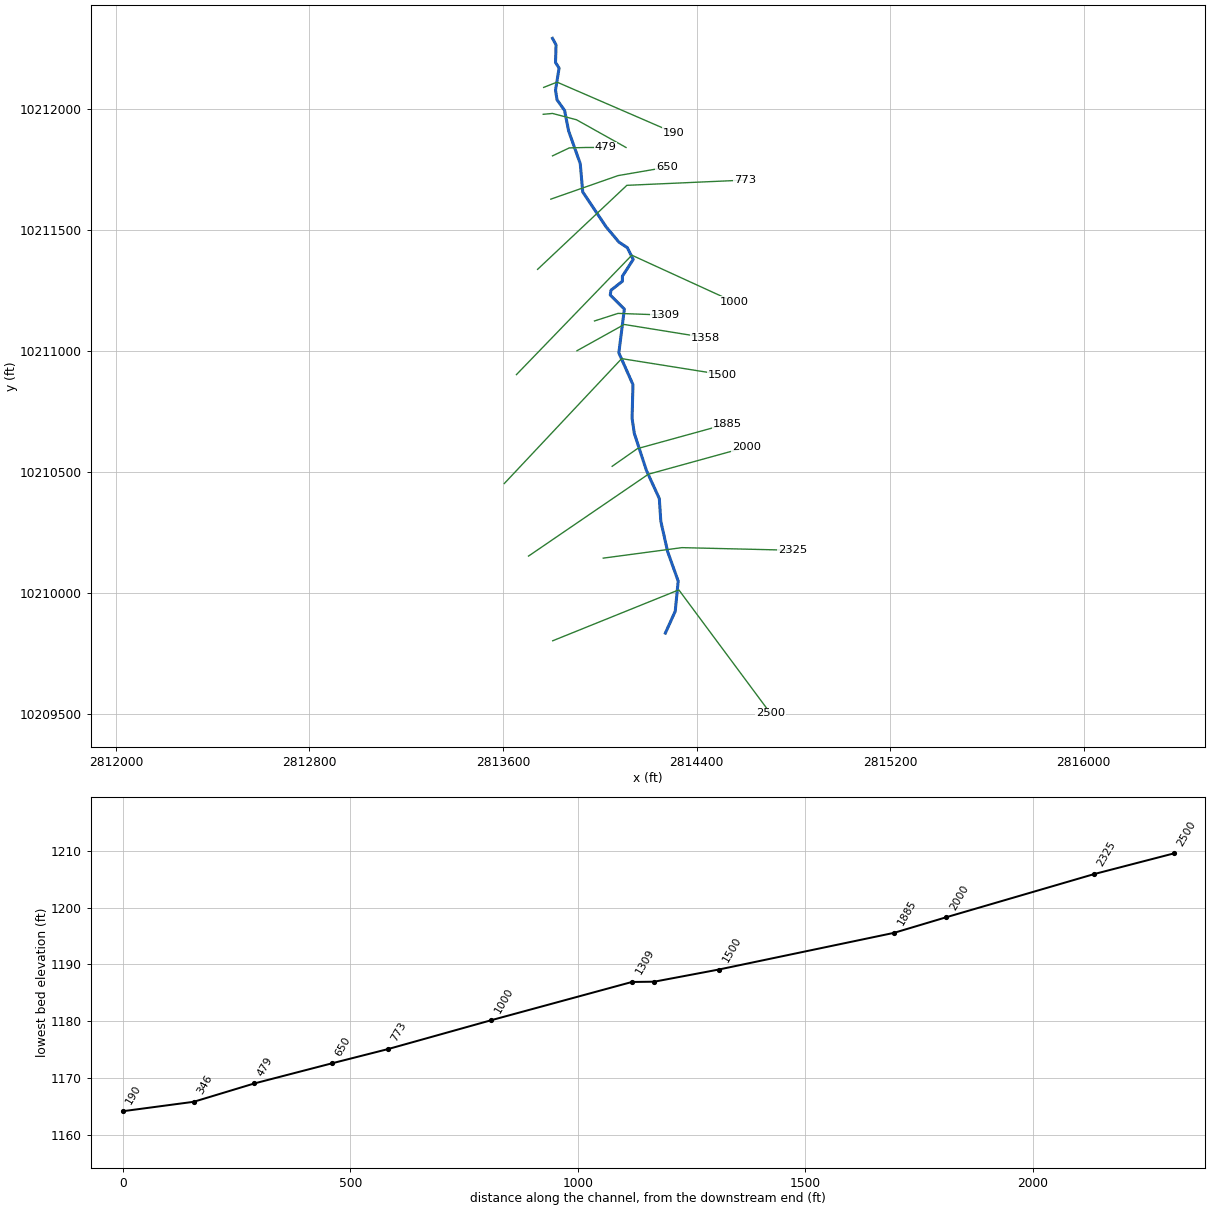
--- SANFERNANDO083.prj (project) ---

Proj Title=SANFERNANDO083 Base Level Engineering
Current Plan=p01
Default Exp/Contr=0.3,0.1
English Units
Geom File=g01
Flow File=f01
Plan File=p01
BEGIN DESCRIPTION:
SANFERNANDO083
END DESCRIPTION:

--- SANFERNANDO083.p01 (plan) ---

Plan Title=Multiple Run
Short Identifier=Multiple
Geom File=g01
Flow File=f01
Subcritical Flow
K Sum by GR= 0
Std Step Tol= 0.01
Critical Tol= 0.01
Num of Std Step Trials= 20
Max Error Tol= 0.3
Flow Tol Ratio= 0.001
Split Flow NTrial= 30
Split Flow Tol= 0.02
Split Flow Ratio= 0.02
Log Output Level= 0
Friction Slope Method= 1
Unsteady Friction Slope Method= 2
Unsteady Bridges Friction Slope Method= 1
Parabolic Critical Depth
Global Vel Dist=  1 , 1 , 1
Global Log Level= 0
CheckData=True
Encroach Param= -1, 0, 0, 0
BEGIN DESCRIPTION:
Multiple Run
END DESCRIPTION:

--- SANFERNANDO083.f01 (steady flow) ---

Flow Title=Multiple
Number of Profiles=7
Profile Names=10-year,25-year,50-year,1pct_min,100-year,1pct_plu,500-year
River Rch & RM= SANFERNANDO083,Reach-1,2500
     123     182     328     198     436     962     629
Boundary for River Rch & Prof#=SANFERNANDO083,Reach-1,1
Up Type=0
Dn Type=3
Dn Slope=0.005
Boundary for River Rch & Prof#=SANFERNANDO083,Reach-1,2
Up Type=0
Dn Type=3
Dn Slope=0.005
Boundary for River Rch & Prof#=SANFERNANDO083,Reach-1,3
Up Type=0
Dn Type=3
Dn Slope=0.005
Boundary for River Rch & Prof#=SANFERNANDO083,Reach-1,4
Up Type=0
Dn Type=3
Dn Slope=0.005
Boundary for River Rch & Prof#=SANFERNANDO083,Reach-1,5
Up Type=0
Dn Type=3
Dn Slope=0.005
Boundary for River Rch & Prof#=SANFERNANDO083,Reach-1,6
Up Type=0
Dn Type=3
Dn Slope=0.005
Boundary for River Rch & Prof#=SANFERNANDO083,Reach-1,7
Up Type=0
Dn Type=3
Dn Slope=0.005

--- SANFERNANDO083.g01 (geometry) ---

Geom Title=Existing Conditions

River Reach=SANFERNANDO083,Reach-1
Reach XY= 30
      2814271.25     10209835.00      2814312.00     10209925.00
      2814324.25     10210050.00      2814280.50     10210172.00
      2814252.50     10210297.00      2814246.25     10210391.00
      2814193.00     10210507.00      2814143.00     10210660.00
      2814133.75     10210722.00      2814137.25     10210862.00
      2814079.00     10210993.00      2814101.75     10211174.00
      2814043.50     10211232.00      2814046.50     10211252.00
      2814093.75     10211289.00      2814093.75     10211310.00
      2814138.25     10211379.00      2814114.00     10211428.00
      2814079.00     10211451.00      2814026.25     10211514.00
      2813929.75     10211658.00      2813919.50     10211775.00
      2813871.50     10211910.00      2813854.75     10211995.00
      2813823.50     10212039.00      2813817.25     10212079.00
      2813832.00     10212170.00      2813817.25     10212193.00
      2813819.50     10212266.00      2813804.75     10212293.00

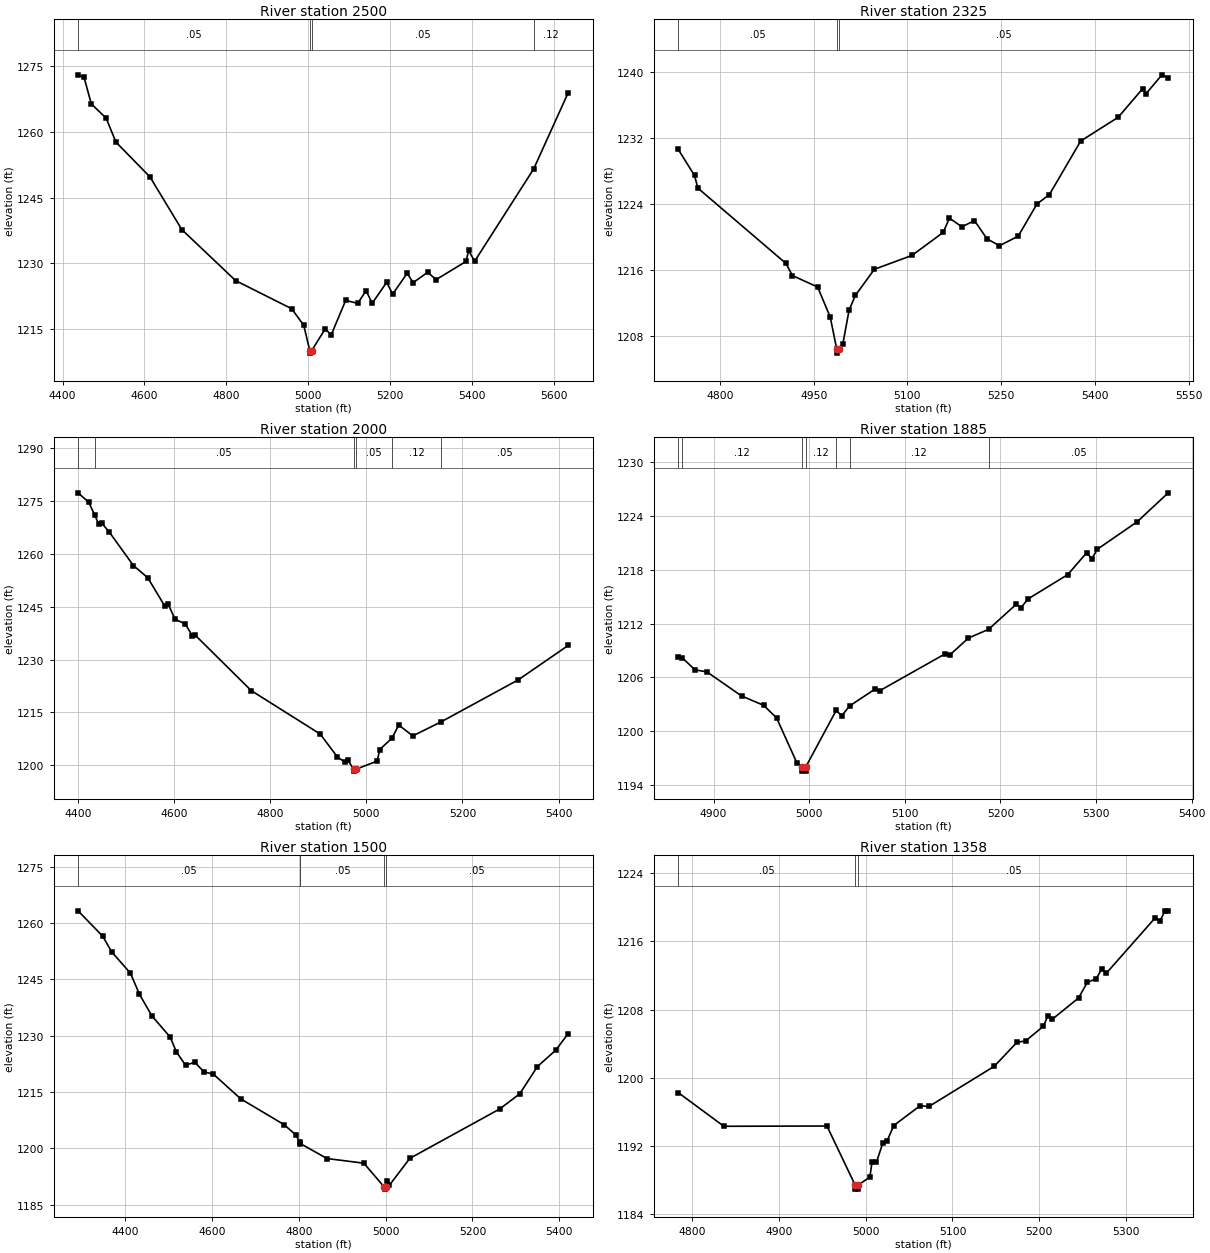
Type RM Length L Ch R = 1,2500,175,175,175
BEGIN DESCRIPTION:
SANFERNANDO083 5.0
END DESCRIPTION:
XS GIS Cut Line= 3
      2813805.67     10209803.11      2814326.92     10210013.48
      2814705.71     10209503.08
#Sta/Elev= 30
  4437.9 1273.05  4452.7 1272.44  4470.3 1266.41  4506.4 1263.19  4530.5 1257.69
  4613.7 1249.75  4691.5 1237.73  4823.0 1226.08  4959.9 1219.67  4989.5 1215.89
  5004.5 1210.03  5004.7 1209.53  5008.5 1210.03  5042.0 1215.07  5056.6 1213.69
  5092.0 1221.57  5121.3 1220.89  5142.1 1223.78  5156.7 1220.90  5192.2 1225.69
  5206.8 1223.00  5242.3 1227.75  5256.9 1225.62  5292.3 1227.97  5313.2 1226.32
  5386.3 1230.46  5392.5 1232.97  5407.1 1230.49  5551.5 1251.58  5635.6 1268.93
#Mann=4,-1,0
  4437.9    0.05       0  5004.5    0.03       0  5008.5    0.05       0
  5551.5    0.12       0
Bank Sta=5004.5,5008.5
Exp/Cntr=0.3,0.1

Type RM Length L Ch R = 1,2325,325,325,325
BEGIN DESCRIPTION:
Mapping XS 14cb9b11
END DESCRIPTION:
XS GIS Cut Line= 3
      2814014.45     10210144.69      2814339.99     10210188.09
      2814795.74     10210177.24
#Sta/Elev= 30
  4733.2 1230.62  4759.4 1227.45  4764.7 1225.92  4905.7 1216.78  4916.0 1215.31
  4956.4 1213.92  4976.6 1210.26  4986.9 1206.40  4987.1 1205.90  4990.9 1206.40
  4996.7 1207.00  5006.8 1211.14  5016.9 1212.91  5047.2 1216.07  5107.3 1217.75
  5157.3 1220.54  5167.3 1222.28  5187.3 1221.22  5207.4 1221.98  5227.4 1219.77
  5247.4 1218.93  5277.4 1220.09  5307.4 1223.99  5327.4 1225.14  5377.4 1231.63
  5437.4 1234.51  5476.7 1237.99  5481.7 1237.34  5507.4 1239.66  5517.5 1239.30
#Mann=3,-1,0
  4733.2    0.05       0  4986.9    0.03       0  4990.9    0.05       0
Bank Sta=4986.9,4990.9
Exp/Cntr=0.3,0.1

Type RM Length L Ch R = 1,2000,115,115,115
BEGIN DESCRIPTION:
SANFERNANDO083 4.0
END DESCRIPTION:
XS GIS Cut Line= 3
      2813705.65     10210153.09      2814200.97     10210491.52
      2814605.67     10210603.11
#Sta/Elev= 30
  4400.1 1277.39  4422.5 1274.69  4434.8 1271.04  4443.5 1268.42  4449.6 1268.73
  4464.5 1266.36  4515.3 1256.73  4545.1 1253.28  4581.0 1245.10  4587.1 1245.92
  4602.0 1241.45  4623.0 1240.17  4637.9 1236.79  4643.9 1236.94  4760.5 1221.19
  4904.0 1208.84  4939.9 1202.31  4954.9 1200.92  4960.9 1201.56  4973.8 1198.81
  4974.1 1198.31  4977.8 1198.81  5022.6 1201.17  5027.8 1204.45  5053.3 1207.67
  5067.4 1211.41  5096.6 1208.32  5155.6 1212.32  5316.1 1224.25  5419.8 1234.01
#Mann=6,-1,0
  4400.1    0.12       0  4434.8    0.05       0  4973.8    0.05       0
  4977.8    0.05       0  5053.3    0.12       0  5155.6    0.05       0
Bank Sta=4973.8,4977.8
Exp/Cntr=0.3,0.1

Type RM Length L Ch R = 1,1885,385,385,385
BEGIN DESCRIPTION:
Mapping XS 4e129210
END DESCRIPTION:
XS GIS Cut Line= 3
      2814051.38     10210524.26      2814155.53     10210597.16
      2814527.04     10210699.59
#Sta/Elev= 30
  4863.0 1208.30  4867.4 1208.19  4880.5 1206.85  4893.0 1206.63  4929.3 1203.94
  4952.3 1202.90  4965.9 1201.50  4987.2 1196.47  4992.6 1196.06  4992.8 1195.56
  4996.3 1195.56  4996.6 1196.06  5028.2 1202.32  5034.1 1201.74  5042.2 1202.82
  5068.5 1204.68  5073.7 1204.52  5142.4 1208.65  5147.6 1208.56  5166.6 1210.40
  5187.6 1211.37  5216.4 1214.15  5221.6 1213.79  5228.9 1214.76  5270.4 1217.47
  5290.3 1219.92  5295.5 1219.23  5301.5 1220.31  5343.0 1223.36  5375.5 1226.59
#Mann=7,-1,0
  4863.0    0.05       0  4867.4    0.12       0  4992.6    0.07       0
  4996.6    0.12       0  5028.2    0.05       0  5042.2    0.12       0
  5187.6    0.05       0
Bank Sta=4992.6,4996.6
Exp/Cntr=0.3,0.1

Type RM Length L Ch R = 1,1500,142,142,142
BEGIN DESCRIPTION:
SANFERNANDO083 3.0
END DESCRIPTION:
XS GIS Cut Line= 3
      2813605.65     10210453.08      2814090.68     10210969.26
      2814505.64     10210903.12
#Sta/Elev= 30
  4291.7 1263.20  4348.2 1256.48  4369.6 1252.20  4412.1 1246.64  4433.2 1240.98
  4461.5 1235.27  4504.0 1229.57  4518.1 1225.66  4539.2 1222.10  4560.6 1222.89
  4581.6 1220.32  4603.1 1219.74  4666.6 1213.12  4765.8 1206.30  4794.1 1203.46
  4801.7 1201.57  4803.9 1201.22  4864.9 1197.26  4949.9 1196.01  4997.2 1189.61
  4997.5 1189.11  5001.2 1189.61  5003.6 1191.24  5008.7 1190.15  5055.7 1197.30
  5262.4 1210.43  5308.9 1214.49  5349.4 1221.73  5391.7 1226.10  5420.2 1230.49
#Mann=5,-1,0
  4291.7    0.05       0  4801.7    0.12       0  4803.9    0.05       0
  4997.2    0.05       0  5001.2    0.05       0
Bank Sta=4997.2,5001.2
Exp/Cntr=0.3,0.1

Type RM Length L Ch R = 1,1358,49,49,49
BEGIN DESCRIPTION:
Mapping XS d69af65c
END DESCRIPTION:
XS GIS Cut Line= 3
      2813905.96     10211001.89      2814101.27     10211110.40
      2814437.69     10211056.14
#Sta/Elev= 30
  4784.2 1198.28  4836.8 1194.33  4955.5 1194.36  4987.8 1187.47  4988.1 1186.97
  4991.6 1186.97  4991.8 1187.47  5004.9 1188.38  5007.3 1190.09  5012.4 1190.09
  5019.6 1192.32  5024.7 1192.61  5032.4 1194.42  5062.7 1196.73  5072.9 1196.65
  5148.2 1201.36  5174.2 1204.16  5184.3 1204.33  5204.6 1206.04  5210.0 1207.30
  5215.1 1206.88  5245.1 1209.35  5255.2 1211.18  5265.3 1211.60  5271.8 1212.72
  5276.9 1212.23  5333.6 1218.76  5338.7 1218.34  5344.8 1219.56  5348.4 1219.56
#Mann=3,-1,0
  4784.2    0.05       0  4987.8    0.05       0  4991.8    0.05       0
Bank Sta=4987.8,4991.8
Exp/Cntr=0.3,0.1

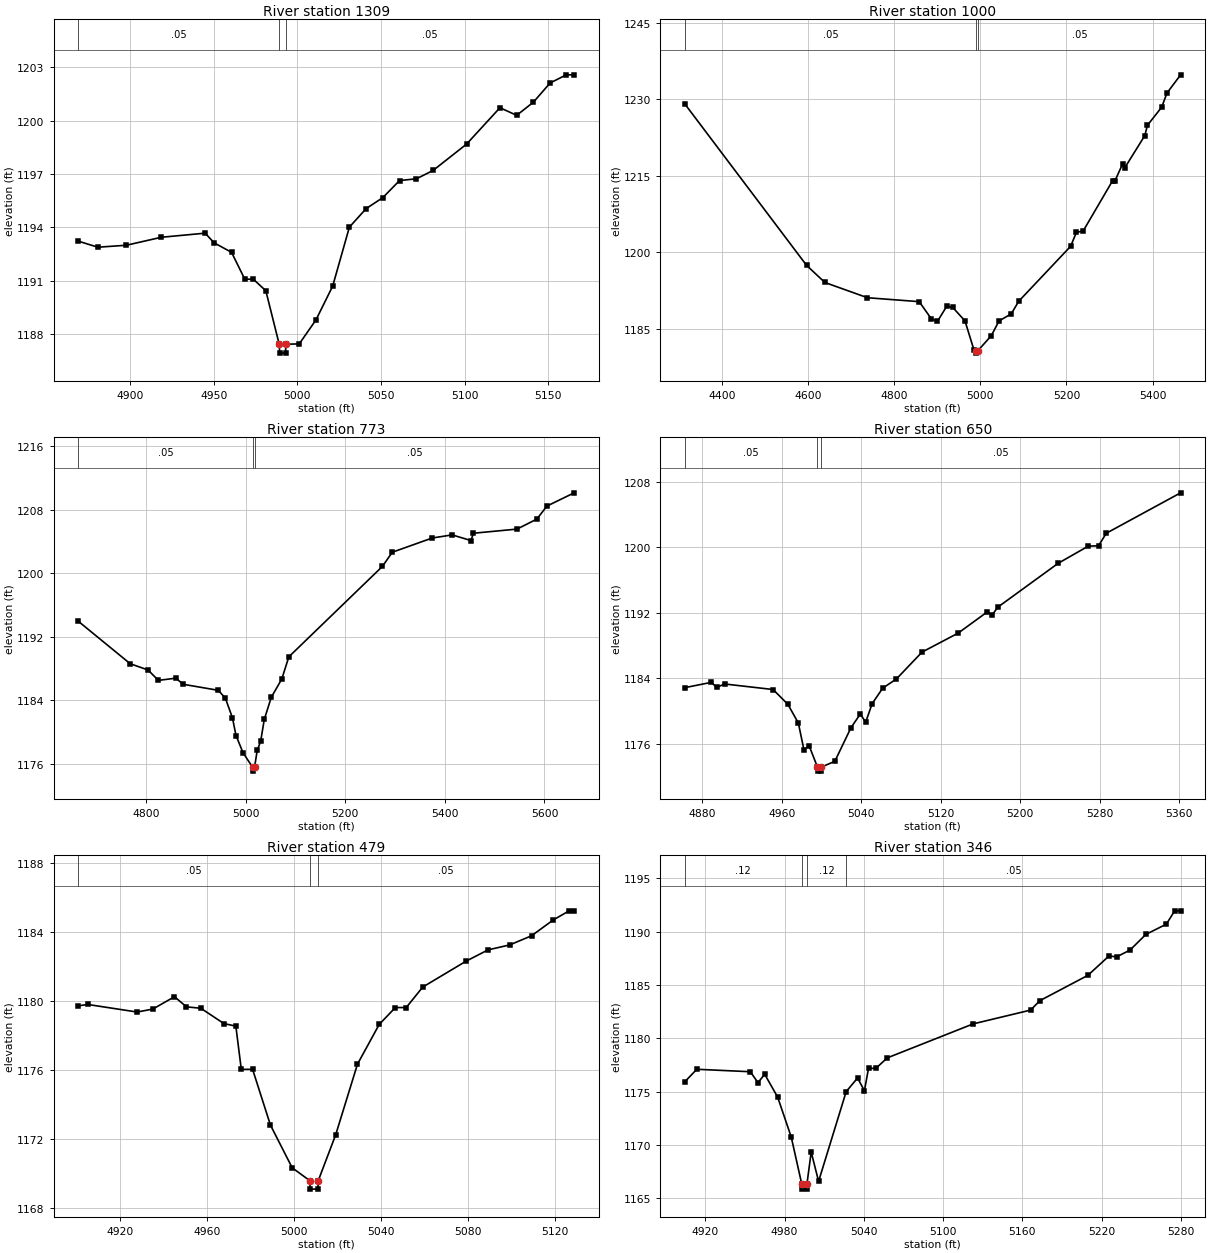
Type RM Length L Ch R = 1,1309,309,309,309
BEGIN DESCRIPTION:
Mapping XS dabb8236
END DESCRIPTION:
XS GIS Cut Line= 3
      2813978.40     10211124.93      2814075.67     10211156.19
      2814270.07     10211149.25
#Sta/Elev= 30
  4868.9 1193.22  4880.6 1192.88  4897.6 1192.99  4918.6 1193.44  4944.8 1193.67
  4950.1 1193.13  4960.6 1192.59  4968.5 1191.08  4973.6 1191.08  4981.1 1190.43
  4989.1 1187.42  4989.4 1186.92  4992.9 1186.92  4993.1 1187.42  5001.1 1187.44
  5011.1 1188.79  5021.1 1190.69  5031.1 1194.01  5041.1 1195.05  5051.1 1195.67
  5061.1 1196.63  5071.2 1196.73  5081.2 1197.20  5101.2 1198.68  5121.2 1200.73
  5131.2 1200.30  5141.2 1201.04  5151.2 1202.12  5160.9 1202.58  5165.6 1202.58
#Mann=3,-1,0
  4868.9    0.05       0  4989.1    0.05       0  4993.1    0.05       0
Bank Sta=4989.1,4993.1
Exp/Cntr=0.3,0.1

Type RM Length L Ch R = 1,1000,227,227,227
BEGIN DESCRIPTION:
SANFERNANDO083 2.0
END DESCRIPTION:
XS GIS Cut Line= 3
      2813655.68     10210903.11      2814132.66     10211396.71
      2814555.67     10211203.12
#Sta/Elev= 30
  4313.6 1229.06  4596.4 1197.41  4638.9 1194.05  4737.9 1191.06  4858.1 1190.29
  4886.4 1186.90  4900.5 1186.44  4921.9 1189.38  4936.0 1189.15  4964.3 1186.53
  4985.4 1180.77  4990.6 1180.70  4990.9 1180.20  4994.6 1180.70  5025.7 1183.64
  5043.3 1186.50  5071.8 1187.90  5089.3 1190.38  5209.8 1201.15  5223.3 1203.92
  5238.4 1204.08  5307.4 1214.03  5312.9 1214.02  5330.4 1217.29  5335.9 1216.59
  5381.9 1222.83  5388.2 1224.88  5421.2 1228.41  5433.5 1231.19  5465.2 1234.76
#Mann=3,-1,0
  4313.6    0.05       0  4990.6    0.05       0  4994.6    0.05       0
Bank Sta=4990.6,4994.6
Exp/Cntr=0.3,0.1

Type RM Length L Ch R = 1,773,123,123,123
BEGIN DESCRIPTION:
Mapping XS 66b29851
END DESCRIPTION:
XS GIS Cut Line= 3
      2813743.18     10211338.25      2814112.12     10211685.49
      2814600.39     10211707.19
#Sta/Elev= 30
  4664.2 1193.96  4768.4 1188.62  4804.0 1187.84  4825.0 1186.53  4860.2 1186.81
  4874.4 1186.04  4945.2 1185.28  4959.4 1184.29  4973.5 1181.84  4980.8 1179.59
  4995.0 1177.41  5014.0 1175.62  5014.3 1175.12  5018.0 1175.62  5023.3 1177.73
  5030.2 1178.86  5037.5 1181.62  5051.6 1184.41  5072.6 1186.69  5086.8 1189.49
  5274.5 1200.85  5294.5 1202.64  5374.6 1204.43  5414.7 1204.82  5452.4 1204.11
  5457.4 1205.03  5544.8 1205.55  5584.8 1206.81  5604.8 1208.44  5659.6 1210.11
#Mann=3,-1,0
  4664.2    0.05       0  5014.0    0.03       0  5018.0    0.05       0
Bank Sta=5014,5018
Exp/Cntr=0.3,0.1

Type RM Length L Ch R = 1,650,171,171,171
BEGIN DESCRIPTION:
Mapping XS 9753c5cd
END DESCRIPTION:
XS GIS Cut Line= 3
      2813797.89     10211628.41      2814075.67     10211725.63
      2814277.10     10211760.36
#Sta/Elev= 30
  4862.6 1182.84  4889.4 1183.49  4894.6 1182.86  4902.6 1183.29  4951.4 1182.61
  4966.2 1180.81  4976.8 1178.51  4982.4 1175.25  4987.7 1175.71  4996.0 1173.12
  4996.2 1172.62  4999.7 1172.62  5000.0 1173.12  5013.5 1173.82  5029.8 1177.95
  5039.2 1179.62  5044.5 1178.60  5051.0 1180.87  5061.6 1182.77  5075.5 1183.91
  5101.2 1187.19  5137.6 1189.52  5166.7 1192.10  5171.8 1191.73  5177.2 1192.67
  5238.1 1198.06  5268.5 1200.17  5278.7 1200.20  5286.5 1201.74  5361.3 1206.69
#Mann=3,-1,0
  4862.6    0.05       0  4996.0    0.05       0  5000.0    0.05       0
Bank Sta=4996,5000
Exp/Cntr=0.3,0.1

Type RM Length L Ch R = 1,479,133,133,133
BEGIN DESCRIPTION:
Mapping XS 00206810
END DESCRIPTION:
XS GIS Cut Line= 4
      2813804.83     10211807.23      2813874.28     10211840.22
      2813945.46     10211841.95      2814025.27     10211841.95
#Sta/Elev= 30
  4900.8 1179.72  4905.1 1179.80  4927.8 1179.36  4935.0 1179.53  4945.0 1180.25
  4950.5 1179.66  4957.1 1179.58  4967.7 1178.69  4973.2 1178.54  4975.7 1176.03
  4980.9 1176.03  4989.1 1172.79  4999.1 1170.31  5007.1 1169.57  5007.4 1169.07
  5010.9 1169.07  5011.1 1169.57  5019.1 1172.23  5029.1 1176.33  5039.1 1178.64
  5046.5 1179.62  5051.5 1179.62  5059.1 1180.81  5079.1 1182.32  5089.1 1182.97
  5099.1 1183.26  5109.1 1183.79  5119.1 1184.71  5126.4 1185.24  5128.7 1185.24
#Mann=3,-1,0
  4900.8    0.05       0  5007.1    0.05       0  5011.1    0.05       0
Bank Sta=5007.1,5011.1
Exp/Cntr=0.3,0.1

Type RM Length L Ch R = 1,346,156,156,156
BEGIN DESCRIPTION:
Mapping XS 24392c39
END DESCRIPTION:
XS GIS Cut Line= 4
      2813766.60     10211979.10      2813804.83     10211982.58
      2813903.79     10211956.54      2814108.61     10211841.98
#Sta/Elev= 30
  4904.5 1175.92  4913.6 1177.09  4954.1 1176.86  4959.9 1175.84  4965.0 1176.62
  4974.8 1174.48  4985.1 1170.73  4993.0 1166.35  4993.3 1165.85  4996.8 1165.85
  4997.0 1166.35  5000.2 1169.33  5005.8 1166.58  5026.7 1175.00  5035.3 1176.27
  5040.5 1175.08  5043.6 1177.18  5049.2 1177.18  5057.8 1178.16  5122.9 1181.35
  5166.3 1182.64  5173.4 1183.53  5209.7 1185.90  5225.7 1187.72  5231.4 1187.63
  5241.6 1188.27  5253.6 1189.74  5269.1 1190.70  5275.4 1191.95  5279.9 1191.95
#Mann=4,-1,0
  4904.5    0.12       0  4993.0    0.07       0  4997.0    0.12       0
  5026.7    0.05       0
Bank Sta=4993,4997
Exp/Cntr=0.3,0.1

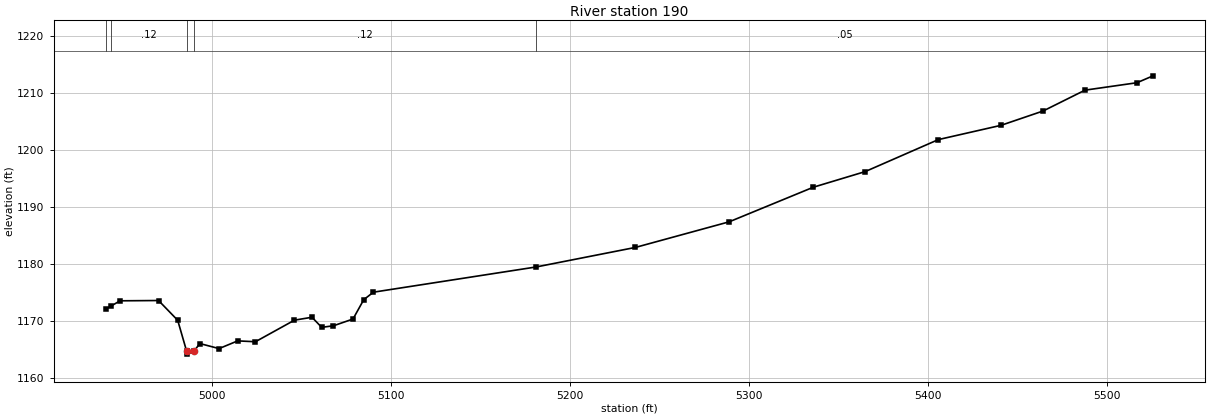
Type RM Length L Ch R = 1,190,0,0,0
BEGIN DESCRIPTION:
SANFERNANDO083 1.0
END DESCRIPTION:
XS GIS Cut Line= 3
      2813768.35     10212090.21      2813823.50     10212112.00
      2814305.70     10211903.11
#Sta/Elev= 30
  4940.7 1172.09  4943.5 1172.60  4948.6 1173.53  4970.1 1173.58  4980.8 1170.12
  4985.8 1164.69  4986.1 1164.19  4989.8 1164.69  4993.2 1166.04  5003.9 1165.16
  5014.3 1166.51  5024.2 1166.36  5046.0 1170.14  5055.8 1170.65  5061.2 1168.88
  5067.8 1169.16  5078.7 1170.34  5084.7 1173.73  5090.1 1175.04  5181.0 1179.46
  5236.4 1182.88  5288.8 1187.37  5335.8 1193.43  5364.7 1196.16  5405.6 1201.77
  5440.6 1204.27  5464.1 1206.78  5487.5 1210.43  5516.5 1211.73  5525.5 1212.94
#Mann=5,-1,0
  4940.7    0.05       0  4943.5    0.12       0  4985.8    0.07       0
  4989.8    0.12       0  5181.0    0.05       0
Bank Sta=4985.8,4989.8
Exp/Cntr=0.3,0.1

Chan Stop Cuts=-1