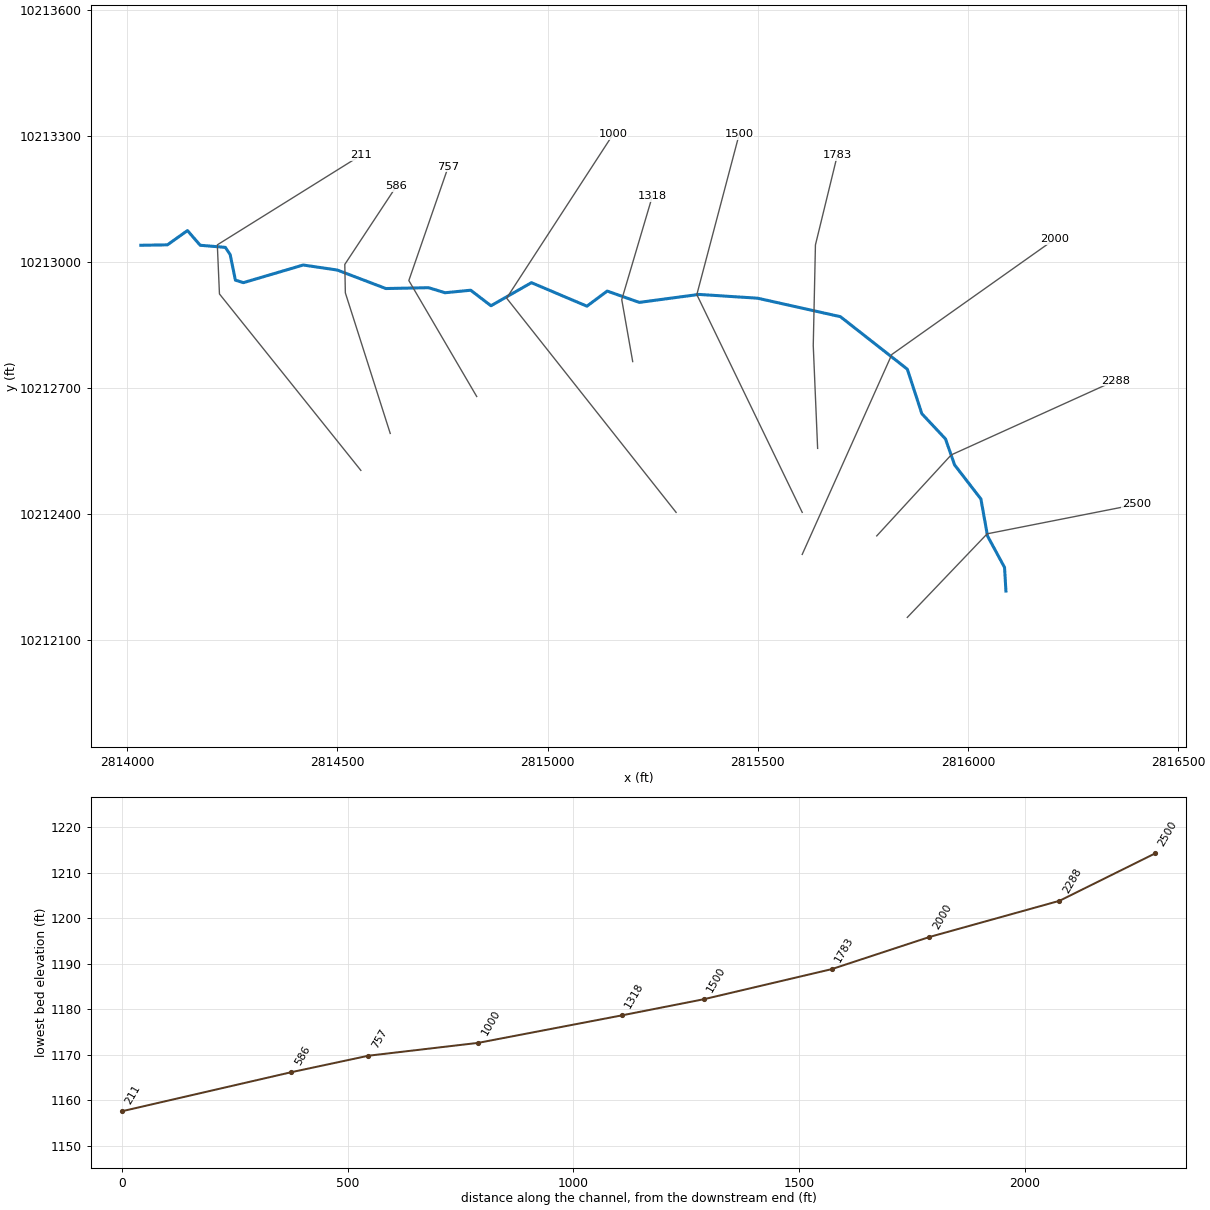
--- SANFERNANDO084.prj (project) ---

Proj Title=SANFERNANDO084 Base Level Engineering
Current Plan=p01
Default Exp/Contr=0.3,0.1
English Units
Geom File=g01
Flow File=f01
Plan File=p01
BEGIN DESCRIPTION:
SANFERNANDO084
END DESCRIPTION:

--- SANFERNANDO084.p01 (plan) ---

Plan Title=Multiple Run
Short Identifier=Multiple
Geom File=g01
Flow File=f01
Subcritical Flow
K Sum by GR= 0
Std Step Tol= 0.01
Critical Tol= 0.01
Num of Std Step Trials= 20
Max Error Tol= 0.3
Flow Tol Ratio= 0.001
Split Flow NTrial= 30
Split Flow Tol= 0.02
Split Flow Ratio= 0.02
Log Output Level= 0
Friction Slope Method= 1
Unsteady Friction Slope Method= 2
Unsteady Bridges Friction Slope Method= 1
Parabolic Critical Depth
Global Vel Dist=  1 , 1 , 1
Global Log Level= 0
CheckData=True
Encroach Param= -1, 0, 0, 0
BEGIN DESCRIPTION:
Multiple Run
END DESCRIPTION:

--- SANFERNANDO084.f01 (steady flow) ---

Flow Title=Multiple
Number of Profiles=7
Profile Names=10-year,25-year,50-year,1pct_min,100-year,1pct_plu,500-year
River Rch & RM= SANFERNANDO084,Reach-1,2500
      91     133     218     136     284     591     407
River Rch & RM= SANFERNANDO084,Reach-1,211
    1618    2852    5427    4269    7830   14361   11055
Boundary for River Rch & Prof#=SANFERNANDO084,Reach-1,1
Up Type=0
Dn Type=3
Dn Slope=0.005
Boundary for River Rch & Prof#=SANFERNANDO084,Reach-1,2
Up Type=0
Dn Type=3
Dn Slope=0.005
Boundary for River Rch & Prof#=SANFERNANDO084,Reach-1,3
Up Type=0
Dn Type=3
Dn Slope=0.005
Boundary for River Rch & Prof#=SANFERNANDO084,Reach-1,4
Up Type=0
Dn Type=3
Dn Slope=0.005
Boundary for River Rch & Prof#=SANFERNANDO084,Reach-1,5
Up Type=0
Dn Type=3
Dn Slope=0.005
Boundary for River Rch & Prof#=SANFERNANDO084,Reach-1,6
Up Type=0
Dn Type=3
Dn Slope=0.005
Boundary for River Rch & Prof#=SANFERNANDO084,Reach-1,7
Up Type=0
Dn Type=3
Dn Slope=0.005

--- SANFERNANDO084.g01 (geometry) ---

Geom Title=Existing Conditions

River Reach=SANFERNANDO084,Reach-1
Reach XY= 30
      2816090.25     10212216.00      2816087.00     10212272.00
      2816046.50     10212347.00      2816030.75     10212435.00
      2815968.25     10212516.00      2815946.50     10212578.00
      2815890.25     10212638.00      2815855.75     10212744.00
      2815696.50     10212869.00      2815499.50     10212913.00
      2815360.00     10212922.00      2815218.00     10212903.00
      2815141.75     10212930.00      2815093.50     10212894.00
      2814961.50     10212950.00      2814865.25     10212895.00
      2814817.00     10212932.00      2814756.00     10212926.00
      2814716.75     10212938.00      2814615.25     10212936.00
      2814499.75     10212980.00      2814418.50     10212992.00
      2814276.25     10212950.00      2814257.25     10212956.00
      2814244.75     10213017.00      2814233.25     10213034.00
      2814173.50     10213039.00      2814143.25     10213074.00
      2814095.50     10213040.00      2814032.25     10213039.00

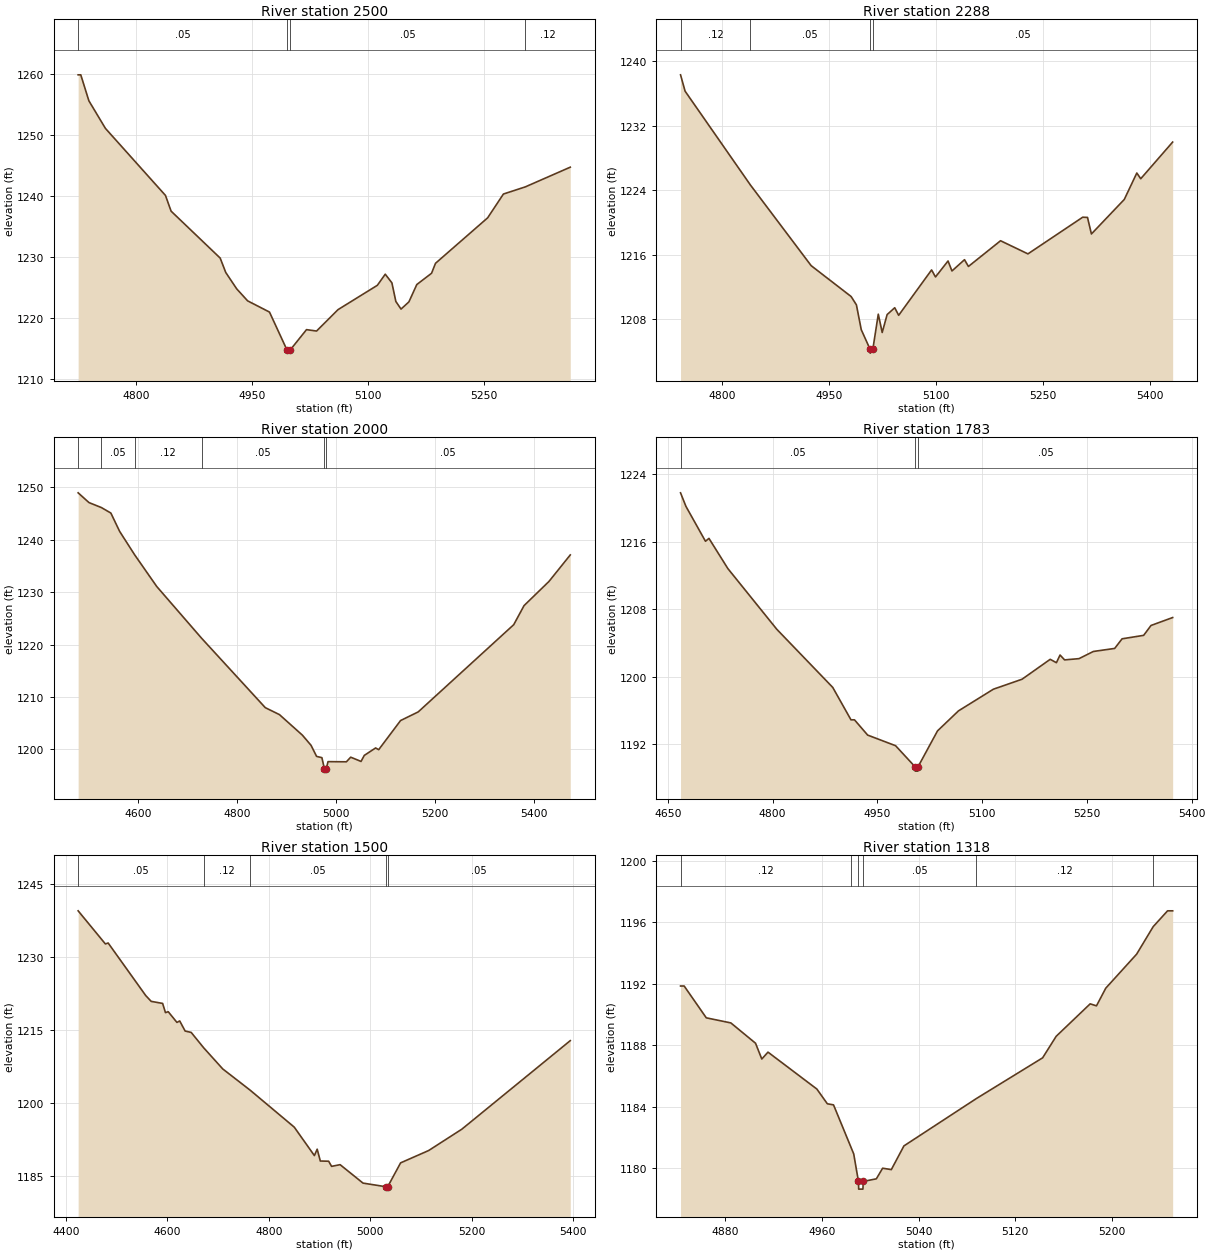
Type RM Length L Ch R = 1,2500,212,212,212
BEGIN DESCRIPTION:
SANFERNANDO084 5.0
END DESCRIPTION:
XS GIS Cut Line= 3
      2815855.71     10212153.14      2816045.59     10212352.07
      2816400.54     10212422.15
#Sta/Elev= 30
  4725.0 1259.84  4728.4 1259.84  4738.9 1255.58  4760.3 1251.06  4838.0 1240.07
  4845.3 1237.49  4908.8 1229.80  4916.0 1227.44  4930.2 1224.75  4944.3 1222.79
  4972.6 1220.95  4995.3 1214.72  4995.5 1214.22  4999.3 1214.72  5020.5 1218.07
  5033.5 1217.84  5061.3 1221.35  5112.2 1225.34  5122.4 1227.16  5131.0 1225.74
  5136.1 1222.69  5142.8 1221.44  5153.0 1222.62  5163.2 1225.46  5182.3 1227.31
  5187.4 1228.94  5254.9 1236.40  5275.3 1240.30  5303.6 1241.47  5361.8 1244.70
#Mann=4,-1,0
  4725.0    0.05       0  4995.3    0.03       0  4999.3    0.05       0
  5303.6    0.12       0
Bank Sta=4995.3,4999.3
Exp/Cntr=0.3,0.1

Type RM Length L Ch R = 1,2288,288,288,288
BEGIN DESCRIPTION:
Mapping XS a3cea9c3
END DESCRIPTION:
XS GIS Cut Line= 3
      2815782.96     10212347.16      2815960.04     10212539.87
      2816350.66     10212716.95
#Sta/Elev= 30
  4741.2 1238.33  4747.6 1236.30  4839.3 1224.66  4924.5 1214.66  4980.6 1210.83
  4988.0 1209.80  4994.8 1206.72  5007.1 1204.31  5007.4 1203.81  5011.1 1204.31
  5018.7 1208.64  5024.2 1206.37  5031.1 1208.59  5041.8 1209.44  5047.3 1208.50
  5093.5 1214.13  5099.0 1213.26  5116.6 1215.24  5122.1 1214.00  5139.7 1215.40
  5145.2 1214.56  5190.3 1217.75  5228.7 1216.12  5305.6 1220.67  5312.3 1220.64
  5317.8 1218.59  5363.9 1222.87  5381.5 1226.15  5387.0 1225.44  5431.8 1229.99
#Mann=4,-1,0
  4741.2    0.12       0  4839.3    0.05       0  5007.1    0.03       0
  5011.1    0.05       0
Bank Sta=5007.1,5011.1
Exp/Cntr=0.3,0.1

Type RM Length L Ch R = 1,2000,217,217,217
BEGIN DESCRIPTION:
SANFERNANDO084 4.0
END DESCRIPTION:
XS GIS Cut Line= 3
      2815605.67     10212303.09      2815818.84     10212779.03
      2816205.69     10213053.11
#Sta/Elev= 30
  4478.5 1248.97  4500.4 1247.11  4525.5 1246.16  4544.7 1245.11  4562.4 1241.62
  4592.7 1237.16  4637.5 1231.10  4728.1 1221.24  4857.1 1207.98  4885.8 1206.65
  4932.2 1202.73  4949.7 1200.79  4960.9 1198.68  4971.6 1198.44  4976.6 1196.37
  4976.8 1195.87  4980.6 1196.37  4984.0 1197.68  5021.2 1197.65  5029.9 1198.53
  5050.8 1197.72  5057.4 1198.87  5080.3 1200.29  5086.5 1199.96  5130.8 1205.52
  5166.5 1207.17  5359.7 1223.81  5380.6 1227.45  5431.0 1232.06  5474.1 1237.12
#Mann=6,-1,0
  4478.5    0.12       0  4525.5    0.05       0  4592.7    0.12       0
  4728.1    0.05       0  4976.6    0.03       0  4980.6    0.05       0
Bank Sta=4976.6,4980.6
Exp/Cntr=0.3,0.1

Type RM Length L Ch R = 1,1783,283,283,283
BEGIN DESCRIPTION:
Mapping XS 3ee49c61
END DESCRIPTION:
XS GIS Cut Line= 4
      2815642.33     10212555.46      2815631.92     10212800.29
      2815637.12     10213039.87      2815689.21     10213253.42
#Sta/Elev= 30
  4668.3 1221.78  4676.0 1220.18  4704.0 1216.04  4709.0 1216.38  4736.0 1212.81
  4806.1 1205.61  4886.2 1198.72  4912.3 1194.88  4917.3 1194.88  4936.2 1193.07
  4976.2 1191.81  5004.2 1189.30  5004.4 1188.80  5007.9 1188.80  5008.2 1189.30
  5036.2 1193.57  5066.2 1195.94  5116.2 1198.51  5157.2 1199.69  5197.5 1202.05
  5206.4 1201.65  5211.6 1202.56  5218.1 1201.98  5238.7 1202.13  5259.3 1202.98
  5289.8 1203.34  5300.4 1204.48  5331.3 1204.89  5341.8 1206.06  5372.8 1207.00
#Mann=3,-1,0
  4668.3    0.05       0  5004.2    0.03       0  5008.2    0.05       0
Bank Sta=5004.2,5008.2
Exp/Cntr=0.3,0.1

Type RM Length L Ch R = 1,1500,182,182,182
BEGIN DESCRIPTION:
SANFERNANDO084 3.0
END DESCRIPTION:
XS GIS Cut Line= 3
      2815605.67     10212403.15      2815354.96     10212921.50
      2815455.69     10213303.13
#Sta/Elev= 30
  4424.2 1239.54  4477.9 1232.72  4483.4 1232.91  4557.5 1222.08  4568.2 1220.89
  4590.8 1220.46  4596.4 1218.57  4601.9 1218.75  4619.0 1216.55  4624.5 1216.85
  4635.2 1214.77  4647.1 1214.49  4672.0 1211.29  4709.3 1206.97  4763.5 1202.58
  4850.4 1194.97  4890.1 1189.11  4895.6 1190.43  4901.8 1187.99  4918.2 1187.95
  4924.0 1186.89  4940.8 1187.24  4986.0 1183.44  5030.7 1182.70  5030.9 1182.20
  5034.7 1182.70  5060.1 1187.61  5115.4 1190.15  5180.9 1194.55  5394.7 1212.79
#Mann=5,-1,0
  4424.2    0.05       0  4672.0    0.12       0  4763.5    0.05       0
  5030.7    0.03       0  5034.7    0.05       0
Bank Sta=5030.7,5034.7
Exp/Cntr=0.3,0.1

Type RM Length L Ch R = 1,1318,318,318,318
BEGIN DESCRIPTION:
Mapping XS 9969e132
END DESCRIPTION:
XS GIS Cut Line= 3
      2815202.40     10212762.10      2815176.36     10212909.66
      2815249.27     10213156.17
#Sta/Elev= 30
  4843.2 1191.86  4846.2 1191.86  4864.5 1189.79  4884.8 1189.46  4905.2 1188.14
  4910.4 1187.11  4915.5 1187.56  4955.9 1185.16  4964.6 1184.20  4969.7 1184.13
  4984.4 1181.32  4986.4 1180.94  4990.3 1179.15  4990.5 1178.65  4994.0 1178.65
  4994.3 1179.15  5005.1 1179.32  5010.3 1180.01  5017.5 1179.92  5027.9 1181.46
  5087.8 1184.54  5142.6 1187.19  5153.8 1188.59  5181.9 1190.70  5187.1 1190.57
  5194.8 1191.72  5220.3 1193.93  5234.0 1195.72  5245.9 1196.75  5250.1 1196.75
#Mann=6,-1,0
  4843.2    0.12       0  4984.4    0.05       0  4990.3    0.05       0
  4994.3    0.05       0  5087.8    0.12       0  5234.0    0.05       0
Bank Sta=4990.3,4994.3
Exp/Cntr=0.3,0.1

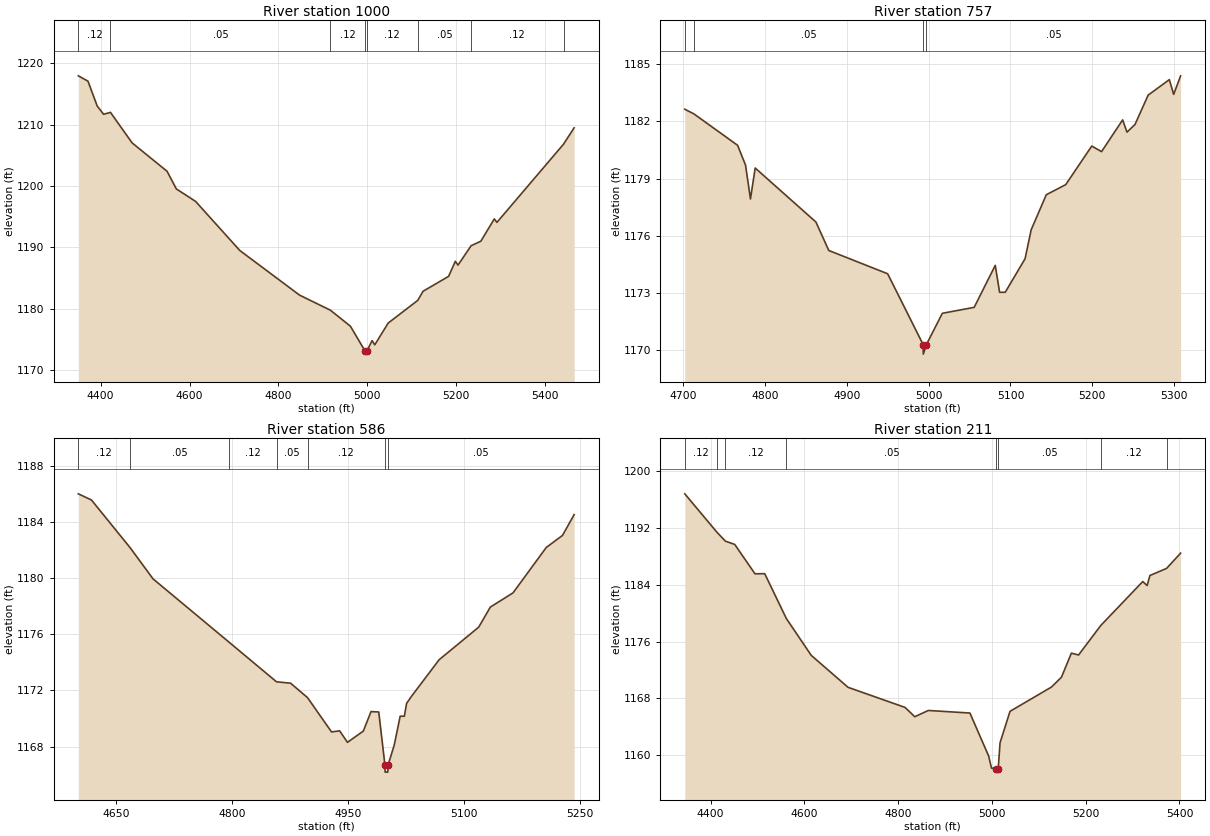
Type RM Length L Ch R = 1,1000,243,243,243
BEGIN DESCRIPTION:
SANFERNANDO084 2.0
END DESCRIPTION:
XS GIS Cut Line= 3
      2815305.70     10212403.09      2814902.45     10212913.14
      2815155.70     10213303.13
#Sta/Elev= 30
  4349.8 1217.93  4371.5 1217.06  4392.3 1213.01  4406.7 1211.67  4422.1 1211.98
  4470.8 1207.01  4549.4 1202.39  4570.2 1199.52  4613.5 1197.49  4712.9 1189.50
  4847.5 1182.22  4916.8 1179.77  4961.7 1177.17  4994.8 1173.12  4995.0 1172.62
  4998.8 1173.12  5010.5 1174.82  5016.5 1174.13  5046.8 1177.68  5113.2 1181.37
  5125.2 1182.86  5182.6 1185.28  5197.7 1187.73  5203.7 1187.11  5233.4 1190.28
  5255.1 1191.00  5285.4 1194.64  5291.3 1194.07  5441.1 1206.80  5465.0 1209.47
#Mann=8,-1,0
  4349.8    0.12       0  4422.1    0.05       0  4916.8    0.12       0
  4994.8    0.07       0  4998.8    0.12       0  5113.2    0.05       0
  5233.4    0.12       0  5441.1    0.05       0
Bank Sta=4994.8,4998.8
Exp/Cntr=0.3,0.1

Type RM Length L Ch R = 1,757,171,171,171
BEGIN DESCRIPTION:
Mapping XS aeef43c7
END DESCRIPTION:
XS GIS Cut Line= 3
      2814831.31     10212678.97      2814669.85     10212955.02
      2814763.60     10213225.85
#Sta/Elev= 30
  4701.7 1182.63  4712.7 1182.39  4766.3 1180.74  4776.0 1179.70  4782.0 1177.93
  4787.8 1179.55  4862.1 1176.72  4877.8 1175.23  4949.8 1174.01  4993.2 1170.30
  4993.4 1169.80  4997.2 1170.30  5016.7 1171.94  5055.6 1172.25  5081.4 1174.45
  5086.7 1173.04  5093.6 1173.04  5117.9 1174.80  5125.3 1176.31  5143.8 1178.15
  5167.6 1178.68  5199.4 1180.70  5211.4 1180.41  5237.2 1182.07  5242.5 1181.43
  5252.3 1181.83  5268.4 1183.37  5294.3 1184.18  5299.6 1183.41  5308.1 1184.38
#Mann=4,-1,0
  4701.7    0.12       0  4712.7    0.05       0  4993.2    0.03       0
  4997.2    0.05       0
Bank Sta=4993.2,4997.2
Exp/Cntr=0.3,0.1

Type RM Length L Ch R = 1,586,375,375,375
BEGIN DESCRIPTION:
Mapping XS 9b370f69
END DESCRIPTION:
XS GIS Cut Line= 4
      2814625.59     10212591.05      2814518.81     10212925.72
      2814517.51     10212993.43      2814640.02     10213179.14
#Sta/Elev= 30
  4601.1 1185.99  4618.1 1185.55  4668.2 1182.15  4697.7 1179.94  4795.9 1175.44
  4857.5 1172.61  4875.7 1172.51  4897.7 1171.48  4928.7 1169.04  4939.2 1169.12
  4949.3 1168.30  4969.8 1169.10  4979.8 1170.49  4989.8 1170.46  4997.8 1166.68
  4998.0 1166.18  5001.5 1166.18  5001.8 1166.68  5009.8 1168.10  5017.5 1170.16
  5022.9 1170.16  5025.8 1171.07  5031.8 1171.55  5067.9 1174.18  5119.1 1176.50
  5134.2 1177.93  5163.5 1178.94  5206.5 1182.17  5227.5 1183.03  5242.6 1184.51
#Mann=7,-1,0
  4601.1    0.12       0  4668.2    0.05       0  4795.9    0.12       0
  4857.5    0.05       0  4897.7    0.12       0  4997.8    0.03       0
  5001.8    0.05       0
Bank Sta=4997.8,5001.8
Exp/Cntr=0.3,0.1

Type RM Length L Ch R = 1,211,0,0,0
BEGIN DESCRIPTION:
SANFERNANDO084 1.0
END DESCRIPTION:
XS GIS Cut Line= 4
      2814555.70     10212503.10      2814219.33     10212923.12
      2814214.25     10213040.00      2814555.70     10213253.12
#Sta/Elev= 30
  4344.9 1196.79  4413.5 1191.38  4431.7 1190.12  4451.4 1189.67  4494.6 1185.53
  4515.4 1185.55  4561.4 1179.25  4614.6 1174.05  4693.1 1169.55  4814.7 1166.72
  4835.5 1165.41  4864.3 1166.29  4953.1 1165.93  4993.1 1159.87  4999.1 1158.17
  5009.5 1158.11  5009.7 1157.61  5013.5 1158.11  5017.3 1161.73  5038.6 1166.17
  5127.1 1169.59  5148.3 1170.97  5169.5 1174.36  5184.8 1174.10  5232.4 1178.27
  5321.7 1184.44  5331.1 1183.88  5337.0 1185.29  5372.5 1186.29  5402.5 1188.44
#Mann=8,-1,0
  4344.9    0.12       0  4413.5    0.05       0  4431.7    0.12       0
  4561.4    0.05       0  5009.5    0.03       0  5013.5    0.05       0
  5232.4    0.12       0  5372.5    0.05       0
Bank Sta=5009.5,5013.5
Exp/Cntr=0.3,0.1

Chan Stop Cuts=-1