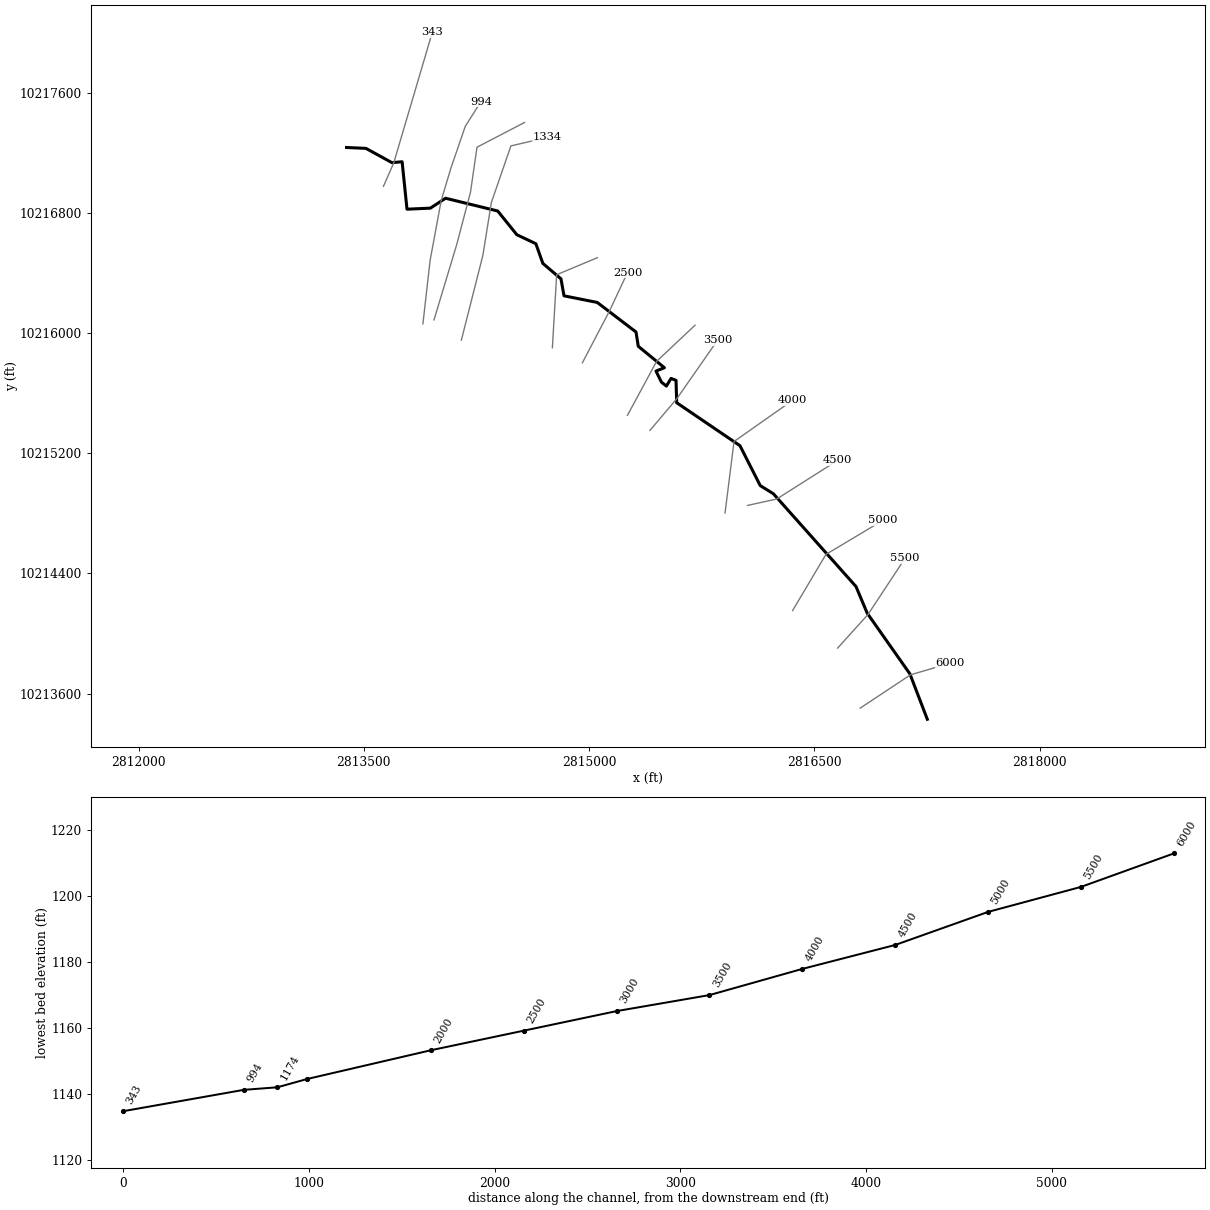
--- SANFERNANDO085.prj (project) ---

Proj Title=SANFERNANDO085 Base Level Engineering
Current Plan=p01
Default Exp/Contr=0.3,0.1
English Units
Geom File=g01
Flow File=f01
Plan File=p01
BEGIN DESCRIPTION:
SANFERNANDO085
END DESCRIPTION:

--- SANFERNANDO085.p01 (plan) ---

Plan Title=Multiple Run
Short Identifier=Multiple
Geom File=g01
Flow File=f01
Subcritical Flow
K Sum by GR= 0
Std Step Tol= 0.01
Critical Tol= 0.01
Num of Std Step Trials= 20
Max Error Tol= 0.3
Flow Tol Ratio= 0.001
Split Flow NTrial= 30
Split Flow Tol= 0.02
Split Flow Ratio= 0.02
Log Output Level= 0
Friction Slope Method= 1
Unsteady Friction Slope Method= 2
Unsteady Bridges Friction Slope Method= 1
Parabolic Critical Depth
Global Vel Dist=  1 , 1 , 1
Global Log Level= 0
CheckData=True
Encroach Param= -1, 0, 0, 0
BEGIN DESCRIPTION:
Multiple Run
END DESCRIPTION:

--- SANFERNANDO085.f01 (steady flow) ---

Flow Title=Multiple
Number of Profiles=7
Profile Names=10-year,25-year,50-year,1pct_min,100-year,1pct_plu,500-year
River Rch & RM= SANFERNANDO085,Reach-1,6000
     224     348     432     267     560    1175     771
Boundary for River Rch & Prof#=SANFERNANDO085,Reach-1,1
Up Type=0
Dn Type=3
Dn Slope=0.005
Boundary for River Rch & Prof#=SANFERNANDO085,Reach-1,2
Up Type=0
Dn Type=3
Dn Slope=0.005
Boundary for River Rch & Prof#=SANFERNANDO085,Reach-1,3
Up Type=0
Dn Type=3
Dn Slope=0.005
Boundary for River Rch & Prof#=SANFERNANDO085,Reach-1,4
Up Type=0
Dn Type=3
Dn Slope=0.005
Boundary for River Rch & Prof#=SANFERNANDO085,Reach-1,5
Up Type=0
Dn Type=3
Dn Slope=0.005
Boundary for River Rch & Prof#=SANFERNANDO085,Reach-1,6
Up Type=0
Dn Type=3
Dn Slope=0.005
Boundary for River Rch & Prof#=SANFERNANDO085,Reach-1,7
Up Type=0
Dn Type=3
Dn Slope=0.005

--- SANFERNANDO085.g01 (geometry) ---

Geom Title=Existing Conditions

River Reach=SANFERNANDO085,Reach-1
Reach XY= 30
      2817252.75     10213429.00      2817137.00     10213731.00
      2816852.75     10214135.00      2816777.75     10214313.00
      2816227.50     10214931.00      2816140.25     10214985.00
      2816005.00     10215251.00      2815583.75     10215537.00
      2815579.25     10215686.00      2815546.00     10215699.00
      2815515.00     10215648.00      2815482.25     10215674.00
      2815445.75     10215748.00      2815502.00     10215770.00
      2815327.75     10215913.00      2815312.75     10216008.00
      2815054.50     10216205.00      2814833.25     10216249.00
      2814813.00     10216362.00      2814692.25     10216465.00
      2814645.75     10216596.00      2814519.00     10216656.00
      2814391.50     10216814.00      2814044.25     10216899.00
      2813943.25     10216833.00      2813787.50     10216826.00
      2813755.00     10217142.00      2813687.00     10217136.00
      2813514.25     10217231.00      2813385.00     10217237.00

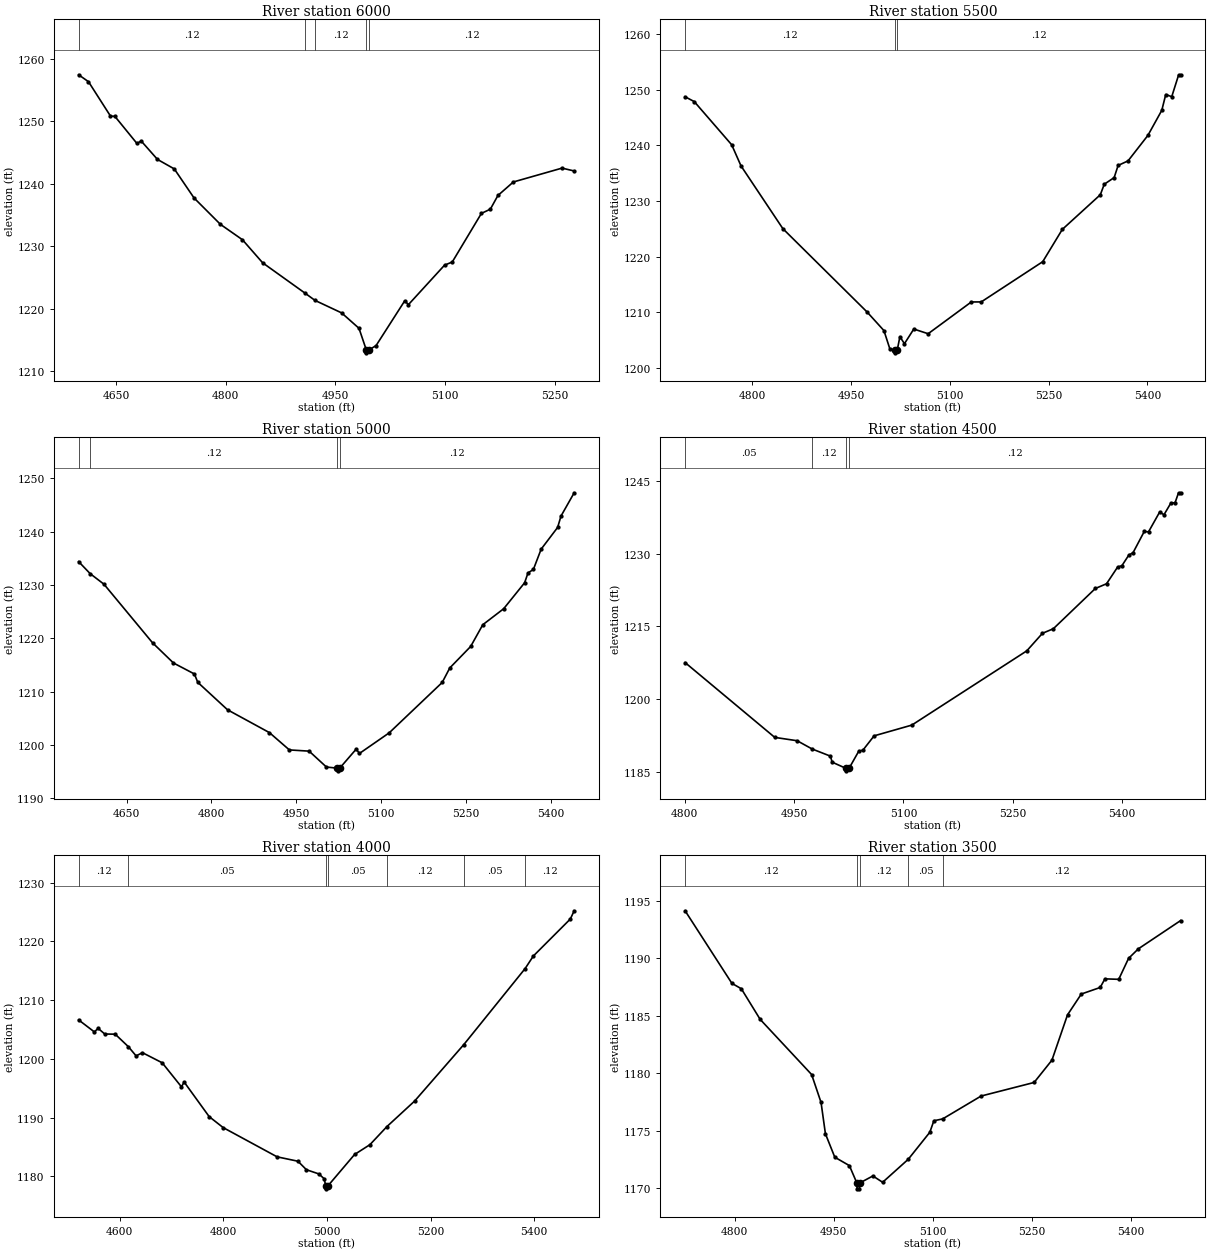
Type RM Length L Ch R = 1,6000,500,500,500
BEGIN DESCRIPTION:
SANFERNANDO085 12.0
END DESCRIPTION:
XS GIS Cut Line= 3
      2816805.71     10213503.13      2817140.25     10213724.60
      2817405.68     10213803.11
#Sta/Elev= 30
  4598.8 1257.45  4612.3 1256.34  4642.4 1250.83  4648.4 1250.79  4678.5 1246.46
  4684.5 1246.83  4706.7 1243.89  4729.7 1242.37  4756.7 1237.72  4792.8 1233.49
  4822.9 1231.03  4850.6 1227.33  4908.7 1222.46  4922.2 1221.31  4958.6 1219.31
  4982.4 1216.84  4992.3 1213.41  4992.5 1212.91  4996.3 1213.41  5005.7 1214.06
  5044.9 1221.23  5050.1 1220.64  5099.5 1226.96  5110.0 1227.46  5149.9 1235.25
  5162.1 1235.92  5172.5 1238.12  5193.6 1240.28  5260.2 1242.50  5276.8 1242.04
#Mann=5,-1,0
  4598.8    0.12       0  4908.7    0.05       0  4922.2    0.12       0
  4992.3    0.07       0  4996.3    0.12       0
Bank Sta=4992.3,4996.3
Exp/Cntr=0.3,0.1

Type RM Length L Ch R = 1,5500,500,500,500
BEGIN DESCRIPTION:
SANFERNANDO085 11.0
END DESCRIPTION:
XS GIS Cut Line= 3
      2816655.66     10213903.09      2816857.88     10214127.12
      2817105.68     10214503.11
#Sta/Elev= 30
  4698.2 1248.70  4712.1 1247.84  4768.9 1240.09  4783.1 1236.29  4846.6 1225.03
  4974.4 1210.08  5000.0 1206.74  5009.1 1203.41  5016.2 1203.25  5016.5 1202.75
  5020.2 1203.25  5024.2 1205.65  5031.1 1204.39  5045.3 1207.02  5067.1 1206.18
  5132.6 1211.88  5147.7 1211.89  5241.0 1219.11  5270.7 1224.90  5328.4 1231.12
  5334.4 1233.01  5349.4 1234.20  5355.4 1236.38  5370.5 1237.20  5400.6 1241.77
  5421.7 1246.27  5427.7 1249.11  5436.8 1248.72  5447.3 1252.65  5450.3 1252.65
#Mann=3,-1,0
  4698.2    0.12       0  5016.2    0.07       0  5020.2    0.12       0
Bank Sta=5016.2,5020.2
Exp/Cntr=0.3,0.1

Type RM Length L Ch R = 1,5000,500,500,500
BEGIN DESCRIPTION:
SANFERNANDO085 10.0
END DESCRIPTION:
XS GIS Cut Line= 3
      2816355.69     10214153.12      2816577.70     10214526.73
      2816955.69     10214753.12
#Sta/Elev= 30
  4565.4 1234.38  4585.8 1232.12  4610.2 1230.14  4695.9 1219.17  4732.9 1215.38
  4769.9 1213.32  4775.8 1211.76  4828.4 1206.61  4902.4 1202.33  4937.6 1199.09
  4972.5 1198.86  5003.1 1195.88  5022.5 1195.67  5022.7 1195.17  5026.5 1195.67
  5055.6 1199.24  5061.4 1198.43  5113.9 1202.29  5207.5 1211.73  5220.9 1214.45
  5257.8 1218.48  5279.2 1222.55  5316.1 1225.55  5353.1 1230.42  5359.0 1232.25
  5368.6 1232.92  5382.3 1236.72  5411.4 1240.79  5417.3 1242.91  5440.6 1247.28
#Mann=4,-1,0
  4565.4    0.05       0  4585.8    0.12       0  5022.5    0.07       0
  5026.5    0.12       0
Bank Sta=5022.5,5026.5
Exp/Cntr=0.3,0.1

Type RM Length L Ch R = 1,4500,500,500,500
BEGIN DESCRIPTION:
SANFERNANDO085 9.0
END DESCRIPTION:
XS GIS Cut Line= 3
      2816055.66     10214853.11      2816250.29     10214896.01
      2816655.65     10215153.09
#Sta/Elev= 30
  4800.7 1207.51  4923.6 1192.05  4954.3 1191.36  4974.9 1189.65  5000.0 1188.17
  5002.2 1186.94  5021.4 1185.64  5021.6 1185.14  5025.4 1185.64  5038.6 1189.16
  5044.5 1189.42  5059.8 1192.37  5111.5 1194.59  5269.1 1209.93  5290.6 1213.56
  5305.5 1214.50  5363.1 1222.82  5378.4 1223.79  5393.6 1227.24  5399.5 1227.53
  5408.9 1229.70  5414.8 1230.22  5430.1 1234.59  5436.0 1234.52  5451.2 1238.60
  5457.2 1238.06  5466.5 1240.44  5472.4 1240.55  5477.1 1242.59  5480.0 1242.59
#Mann=4,-1,0
  4800.7    0.05       0  4974.9    0.12       0  5021.4    0.07       0
  5025.4    0.12       0
Bank Sta=5021.4,5025.4
Exp/Cntr=0.3,0.1

Type RM Length L Ch R = 1,4000,500,500,500
BEGIN DESCRIPTION:
SANFERNANDO085 8.0
END DESCRIPTION:
XS GIS Cut Line= 3
      2815905.68     10214803.08      2815965.48     10215278.73
      2816355.67     10215553.10
#Sta/Elev= 30
  4520.6 1206.64  4550.9 1204.60  4558.3 1205.20  4571.0 1204.24  4591.2 1204.21
  4616.6 1202.08  4631.5 1200.52  4643.8 1201.06  4681.9 1199.34  4719.1 1195.24
  4724.2 1196.07  4772.6 1190.17  4799.5 1188.31  4903.6 1183.33  4943.9 1182.58
  4960.3 1181.13  4984.3 1180.42  4994.3 1179.61  4997.7 1178.38  4997.9 1177.88
  5001.7 1178.38  5053.2 1183.73  5082.8 1185.40  5115.6 1188.48  5169.0 1192.82
  5263.9 1202.43  5382.4 1215.39  5398.2 1217.52  5469.6 1223.82  5477.0 1225.22
#Mann=7,-1,0
  4520.6    0.12       0  4616.6    0.05       0  4997.7    0.05       0
  5001.7    0.05       0  5115.6    0.12       0  5263.9    0.05       0
  5382.4    0.12       0
Bank Sta=4997.7,5001.7
Exp/Cntr=0.3,0.1

Type RM Length L Ch R = 1,3500,500,500,500
BEGIN DESCRIPTION:
SANFERNANDO085 7.0
END DESCRIPTION:
XS GIS Cut Line= 3
      2815405.66     10215353.08      2815583.79     10215562.99
      2815855.67     10215953.09
#Sta/Elev= 30
  4724.7 1194.12  4795.6 1187.81  4809.9 1187.34  4838.4 1184.68  4916.4 1179.88
  4930.7 1177.45  4937.3 1174.73  4951.5 1172.69  4973.6 1171.96  4985.0 1170.44
  4985.3 1169.94  4988.8 1169.94  4989.0 1170.44  5009.2 1171.06  5024.0 1170.51
  5062.8 1172.51  5095.5 1174.86  5101.6 1175.86  5114.9 1176.02  5173.2 1178.01
  5253.5 1179.19  5280.5 1181.13  5304.1 1185.07  5325.0 1186.88  5353.6 1187.45
  5360.8 1188.20  5381.7 1188.16  5396.6 1189.98  5411.4 1190.81  5475.5 1193.27
#Mann=5,-1,0
  4724.7    0.12       0  4985.0    0.07       0  4989.0    0.12       0
  5062.8    0.05       0  5114.9    0.12       0
Bank Sta=4985,4989
Exp/Cntr=0.3,0.1

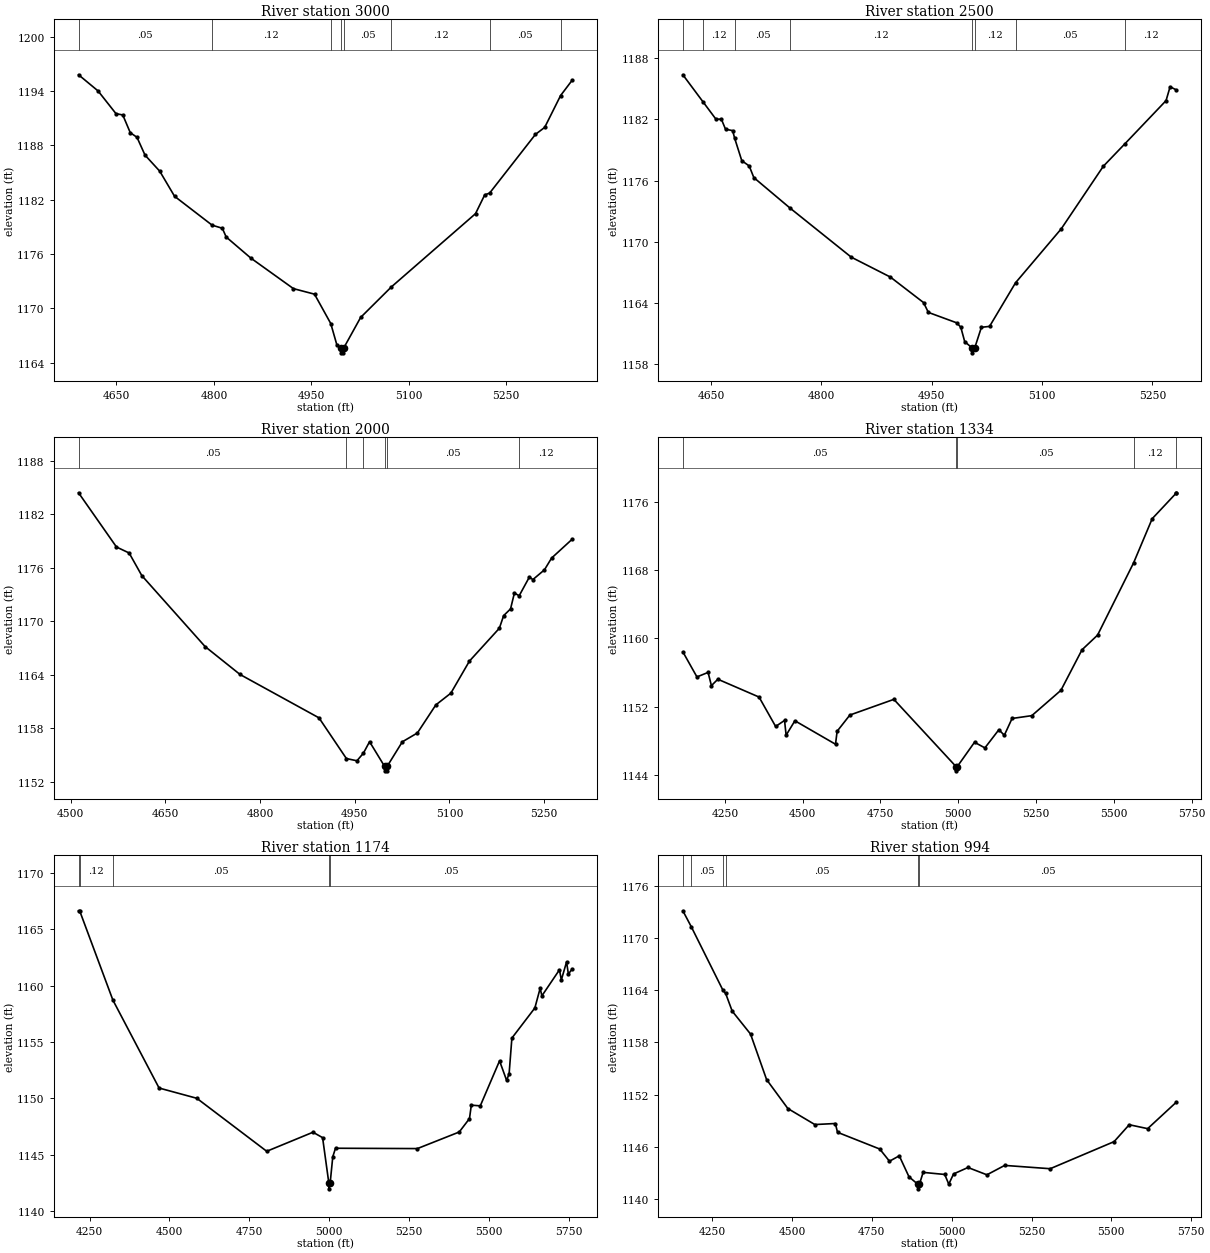
Type RM Length L Ch R = 1,3000,500,500,500
BEGIN DESCRIPTION:
SANFERNANDO085 6.0
END DESCRIPTION:
XS GIS Cut Line= 3
      2815255.68     10215453.10      2815449.70     10215812.46
      2815705.66     10216053.09
#Sta/Elev= 30
  4591.6 1195.79  4621.6 1194.01  4649.2 1191.50  4659.7 1191.35  4671.2 1189.40
  4681.6 1188.88  4693.9 1186.92  4716.6 1185.14  4739.4 1182.37  4797.2 1179.18
  4812.9 1178.84  4818.9 1177.87  4856.7 1175.55  4922.4 1172.17  4954.8 1171.56
  4979.8 1168.32  4989.4 1165.91  4995.5 1165.58  4995.8 1165.08  4999.3 1165.08
  4999.5 1165.58  5025.8 1168.99  5073.1 1172.36  5202.6 1180.45  5216.8 1182.53
  5224.3 1182.72  5294.9 1189.21  5309.1 1189.98  5333.6 1193.50  5351.3 1195.18
#Mann=8,-1,0
  4591.6    0.05       0  4797.2    0.12       0  4979.8    0.05       0
  4995.5    0.05       0  4999.5    0.05       0  5073.1    0.12       0
  5224.3    0.05       0  5333.6    0.12       0
Bank Sta=4995.5,4999.5
Exp/Cntr=0.3,0.1

Type RM Length L Ch R = 1,2500,500,500,500
BEGIN DESCRIPTION:
SANFERNANDO085 5.0
END DESCRIPTION:
XS GIS Cut Line= 3
      2814955.70     10215803.15      2815135.55     10216147.17
      2815255.67     10216403.08
#Sta/Elev= 30
  4611.8 1186.37  4639.0 1183.74  4656.9 1182.01  4664.1 1182.03  4669.8 1181.04
  4679.5 1180.90  4682.2 1180.16  4691.9 1177.96  4702.0 1177.44  4708.3 1176.30
  4757.6 1173.31  4840.7 1168.51  4893.9 1166.56  4939.0 1164.06  4945.5 1163.10
  4984.0 1162.08  4989.6 1161.65  4994.9 1160.24  5004.6 1159.64  5004.8 1159.14
  5008.6 1159.64  5017.6 1161.64  5028.7 1161.73  5064.0 1166.00  5126.2 1171.29
  5183.3 1177.41  5212.5 1179.60  5268.6 1183.84  5274.1 1185.20  5282.7 1184.88
#Mann=8,-1,0
  4611.8    0.05       0  4639.0    0.12       0  4682.2    0.05       0
  4757.6    0.12       0  5004.6    0.07       0  5008.6    0.12       0
  5064.0    0.05       0  5212.5    0.12       0
Bank Sta=5004.6,5008.6
Exp/Cntr=0.3,0.1

Type RM Length L Ch R = 1,2000,666,666,666
BEGIN DESCRIPTION:
SANFERNANDO085 4.0
END DESCRIPTION:
XS GIS Cut Line= 3
      2814755.68     10215903.11      2814784.23     10216389.58
      2815055.65     10216503.10
#Sta/Elev= 30
  4512.7 1184.42  4572.8 1178.33  4592.8 1177.66  4612.9 1175.12  4713.0 1167.16
  4768.4 1164.02  4893.4 1159.15  4936.8 1154.58  4953.5 1154.33  4963.7 1155.18
  4973.5 1156.47  4997.3 1153.70  4997.5 1153.20  5001.0 1153.20  5001.3 1153.70
  5025.4 1156.46  5049.2 1157.45  5078.4 1160.60  5102.2 1161.92  5131.6 1165.52
  5179.0 1169.21  5185.8 1170.63  5196.7 1171.38  5202.8 1173.16  5210.4 1172.86
  5226.6 1174.97  5232.0 1174.67  5250.4 1175.77  5261.7 1177.09  5294.2 1179.20
#Mann=6,-1,0
  4512.7    0.05       0  4936.8    0.12       0  4963.7    0.05       0
  4997.3    0.05       0  5001.3    0.05       0  5210.4    0.12       0
Bank Sta=4997.3,5001.3
Exp/Cntr=0.3,0.1

Type RM Length L Ch R = 1,1334,160,160,160
BEGIN DESCRIPTION:
Mapping XS 9c875d91
END DESCRIPTION:
XS GIS Cut Line= 5
      2814149.59     10215954.09      2814292.82     10216518.35
      2814349.25     10216869.91      2814479.46     10217247.51
      2814721.58     10217303.72
#Sta/Elev= 30
  4114.9 1158.43  4160.2 1155.49  4196.0 1156.02  4206.7 1154.47  4227.4 1155.22
  4359.8 1153.13  4413.1 1149.68  4441.7 1150.39  4446.8 1148.66  4475.0 1150.35
  4605.5 1147.60  4610.7 1149.12  4651.6 1151.02  4793.0 1152.86  4992.8 1144.98
  4993.0 1144.48  4996.8 1144.98  5052.2 1147.83  5085.6 1147.17  5130.5 1149.30
  5148.0 1148.65  5172.9 1150.62  5236.3 1150.95  5329.9 1153.92  5397.6 1158.67
  5447.6 1160.39  5563.4 1168.86  5623.2 1174.04  5700.1 1177.03  5701.1 1177.08
#Mann=5,-1,0
  4114.9    0.05       0  4992.8    0.05       0  4996.8    0.05       0
  5563.4    0.12       0  5700.1    0.05       0
Bank Sta=4992.8,4996.8
Exp/Cntr=0.3,0.1

Type RM Length L Ch R = 1,1174,180,180,180
BEGIN DESCRIPTION:
Mapping XS 78bde95b
END DESCRIPTION:
XS GIS Cut Line= 5
      2813967.30     10216088.65      2814119.21     10216592.13
      2814210.36     10216939.36      2814253.76     10217238.83
      2814570.60     10217403.77
#Sta/Elev= 30
  4215.4 1166.63  4218.9 1166.63  4322.9 1158.71  4467.5 1150.91  4585.6 1150.00
  4804.4 1145.30  4949.1 1146.99  4979.2 1146.51  4998.8 1142.47  4999.0 1141.97
  5002.8 1142.47  5011.1 1144.82  5019.6 1145.57  5275.9 1145.54  5406.8 1147.01
  5438.9 1148.20  5444.6 1149.39  5472.7 1149.33  5533.0 1153.32  5555.1 1151.59
  5562.9 1152.17  5571.6 1155.34  5643.5 1158.01  5660.0 1159.75  5665.6 1159.09
  5720.6 1161.40  5726.3 1160.49  5742.7 1162.09  5748.4 1161.02  5760.1 1161.46
#Mann=5,-1,0
  4215.4    0.05       0  4218.9    0.12       0  4322.9    0.05       0
  4998.8    0.03       0  5002.8    0.05       0
Bank Sta=4998.8,5002.8
Exp/Cntr=0.3,0.1

Type RM Length L Ch R = 1,994,651,651,651
BEGIN DESCRIPTION:
Mapping XS dcd4c74c
END DESCRIPTION:
XS GIS Cut Line= 6
      2813893.51     10216062.58      2813941.26     10216483.63
      2814015.05     10216882.93      2814080.15     10217099.95
      2814175.64     10217377.72      2814279.81     10217542.67
#Sta/Elev= 30
  4158.5 1173.12  4185.0 1171.28  4284.4 1163.97  4292.5 1163.63  4313.0 1161.60
  4370.4 1158.97  4420.7 1153.74  4487.2 1150.42  4571.7 1148.58  4635.9 1148.70
  4642.7 1147.69  4774.9 1145.77  4805.4 1144.37  4836.0 1144.99  4866.5 1142.58
  4895.0 1141.70  4895.2 1141.20  4899.0 1141.70  4910.7 1143.09  4978.3 1142.85
  4991.0 1141.74  5006.0 1142.91  5051.1 1143.65  5110.4 1142.81  5166.0 1143.89
  5308.5 1143.51  5508.6 1146.62  5555.9 1148.56  5613.6 1148.11  5703.7 1151.16
#Mann=6,-1,0
  4158.5    0.12       0  4185.0    0.05       0  4284.4    0.12       0
  4292.5    0.05       0  4895.0    0.03       0  4899.0    0.05       0
Bank Sta=4895,4899
Exp/Cntr=0.3,0.1

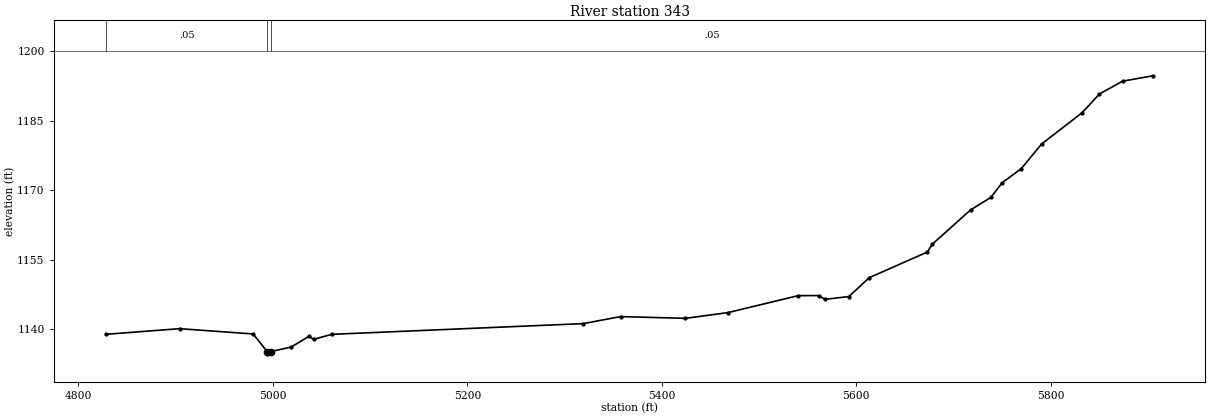
Type RM Length L Ch R = 1,343,0,0,0
BEGIN DESCRIPTION:
SANFERNANDO085 1.0
END DESCRIPTION:
XS GIS Cut Line= 3
      2813630.69     10216978.13      2813699.50     10217135.00
      2813955.68     10218003.09
#Sta/Elev= 30
  4828.7 1138.93  4904.2 1140.14  4979.8 1139.00  4994.2 1135.21  4994.5 1134.71
  4998.2 1135.21  5018.9 1136.18  5037.0 1138.46  5042.2 1137.85  5060.6 1138.92
  5319.1 1141.23  5357.6 1142.75  5424.2 1142.37  5468.0 1143.61  5540.2 1147.27
  5561.1 1147.28  5567.9 1146.48  5592.3 1147.07  5613.2 1151.14  5673.0 1156.68
  5678.2 1158.39  5717.4 1165.76  5738.3 1168.47  5750.0 1171.65  5769.6 1174.68
  5790.4 1179.98  5832.1 1186.74  5850.0 1190.80  5873.8 1193.56  5905.1 1194.72
#Mann=3,-1,0
  4828.7    0.05       0  4994.2    0.05       0  4998.2    0.05       0
Bank Sta=4994.2,4998.2
Exp/Cntr=0.3,0.1

Chan Stop Cuts=-1