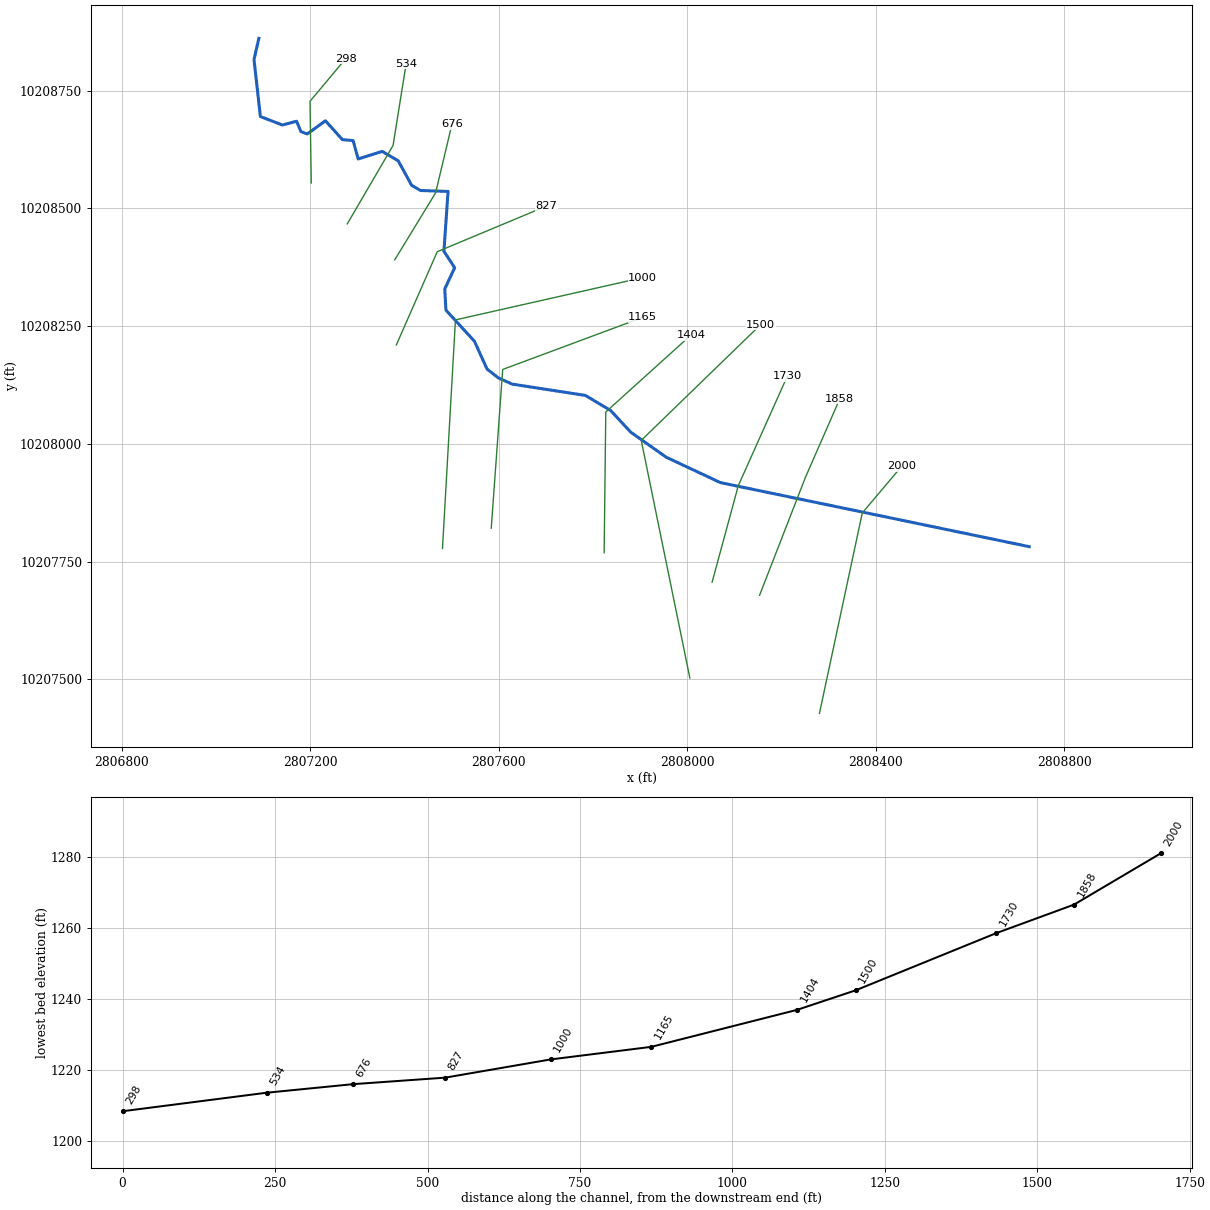
--- SANFERNANDO086.prj (project) ---

Proj Title=SANFERNANDO086 Base Level Engineering
Current Plan=p01
Default Exp/Contr=0.3,0.1
English Units
Geom File=g01
Flow File=f01
Plan File=p01
BEGIN DESCRIPTION:
SANFERNANDO086
END DESCRIPTION:

--- SANFERNANDO086.p01 (plan) ---

Plan Title=Multiple Run
Short Identifier=Multiple
Geom File=g01
Flow File=f01
Subcritical Flow
K Sum by GR= 0
Std Step Tol= 0.01
Critical Tol= 0.01
Num of Std Step Trials= 20
Max Error Tol= 0.3
Flow Tol Ratio= 0.001
Split Flow NTrial= 30
Split Flow Tol= 0.02
Split Flow Ratio= 0.02
Log Output Level= 0
Friction Slope Method= 1
Unsteady Friction Slope Method= 2
Unsteady Bridges Friction Slope Method= 1
Parabolic Critical Depth
Global Vel Dist=  1 , 1 , 1
Global Log Level= 0
CheckData=True
Encroach Param= -1, 0, 0, 0
BEGIN DESCRIPTION:
Multiple Run
END DESCRIPTION:

--- SANFERNANDO086.f01 (steady flow) ---

Flow Title=Multiple
Number of Profiles=7
Profile Names=10-year,25-year,50-year,1pct_min,100-year,1pct_plu,500-year
River Rch & RM= SANFERNANDO086,Reach-1,2000
      41      57      82      55     104     197     149
Boundary for River Rch & Prof#=SANFERNANDO086,Reach-1,1
Up Type=0
Dn Type=3
Dn Slope=0.005
Boundary for River Rch & Prof#=SANFERNANDO086,Reach-1,2
Up Type=0
Dn Type=3
Dn Slope=0.005
Boundary for River Rch & Prof#=SANFERNANDO086,Reach-1,3
Up Type=0
Dn Type=3
Dn Slope=0.005
Boundary for River Rch & Prof#=SANFERNANDO086,Reach-1,4
Up Type=0
Dn Type=3
Dn Slope=0.005
Boundary for River Rch & Prof#=SANFERNANDO086,Reach-1,5
Up Type=0
Dn Type=3
Dn Slope=0.005
Boundary for River Rch & Prof#=SANFERNANDO086,Reach-1,6
Up Type=0
Dn Type=3
Dn Slope=0.005
Boundary for River Rch & Prof#=SANFERNANDO086,Reach-1,7
Up Type=0
Dn Type=3
Dn Slope=0.005

--- SANFERNANDO086.g01 (geometry) ---

Geom Title=Existing Conditions

River Reach=SANFERNANDO086,Reach-1
Reach XY= 30
      2808725.75     10207782.00      2808070.25     10207918.00
      2807955.25     10207972.00      2807880.25     10208025.00
      2807837.50     10208071.00      2807784.00     10208103.00
      2807628.75     10208127.00      2807599.50     10208140.00
      2807575.25     10208159.00      2807548.50     10208218.00
      2807488.00     10208284.00      2807485.50     10208329.00
      2807506.50     10208374.00      2807483.75     10208409.00
      2807492.50     10208536.00      2807434.25     10208538.00
      2807415.25     10208549.00      2807386.75     10208601.00
      2807352.75     10208621.00      2807301.75     10208605.00
      2807291.00     10208644.00      2807268.25     10208646.00
      2807232.25     10208686.00      2807193.75     10208658.00
      2807180.25     10208663.00      2807171.00     10208685.00
      2807141.00     10208677.00      2807094.25     10208695.00
      2807080.75     10208816.00      2807091.00     10208861.00

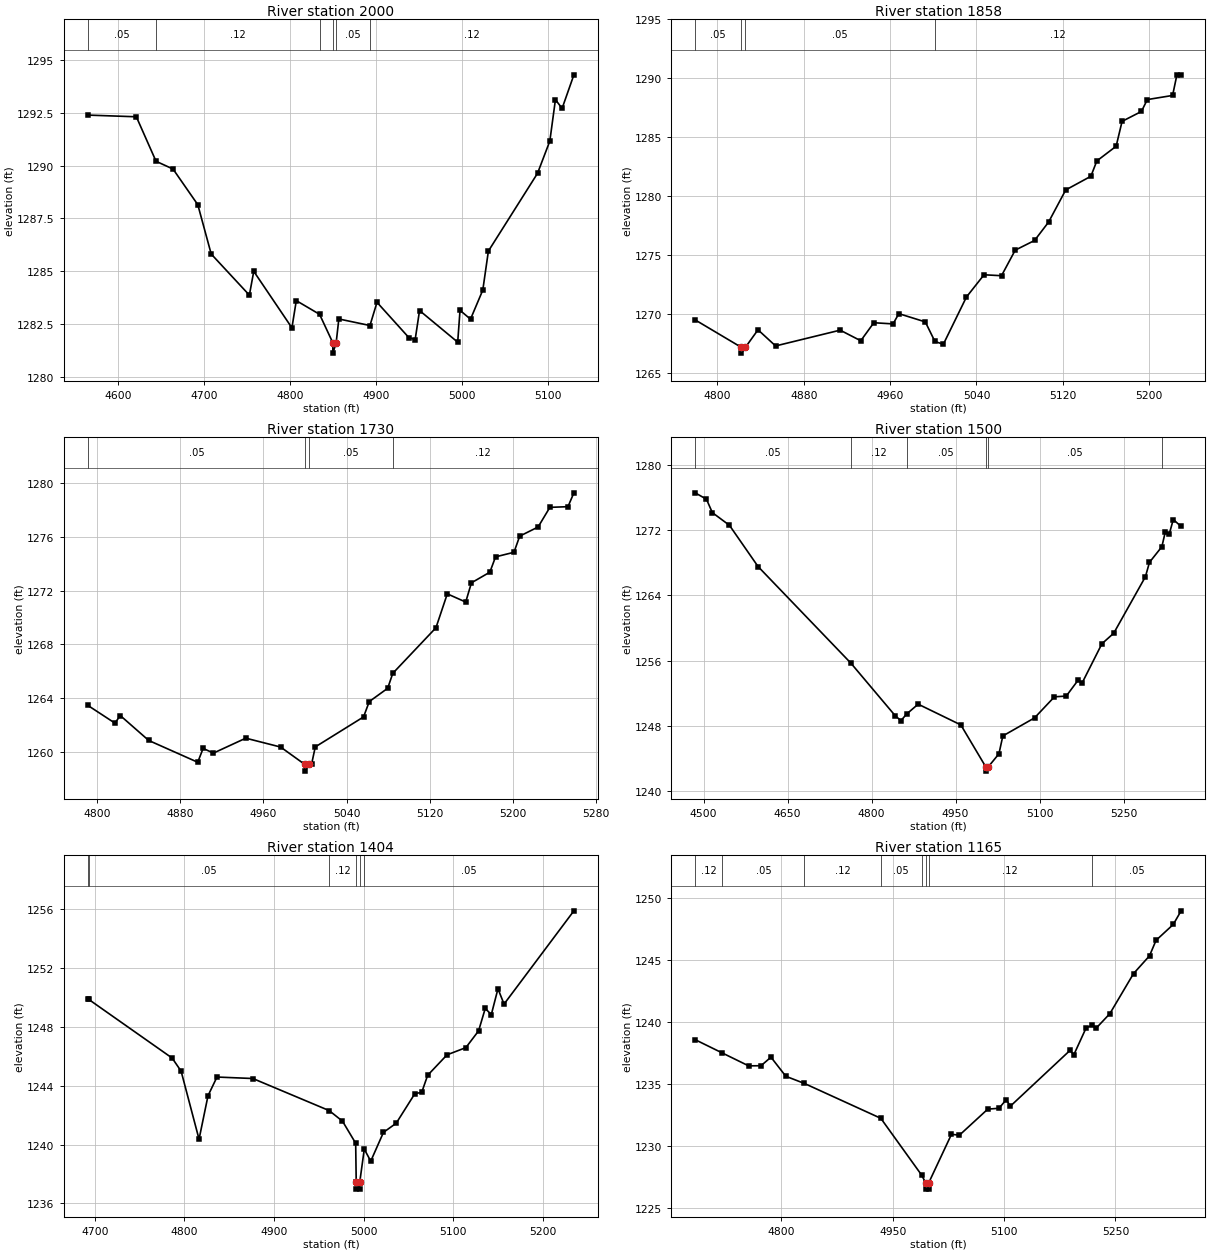
Type RM Length L Ch R = 1,2000,142,142,142
BEGIN DESCRIPTION:
SANFERNANDO086 4.0
END DESCRIPTION:
XS GIS Cut Line= 3
      2808280.68     10207428.09      2808371.55     10207853.49
      2808455.69     10207953.12
#Sta/Elev= 30
  4565.0 1292.40  4621.3 1292.32  4644.2 1290.21  4664.0 1289.84  4692.8 1288.15
  4708.4 1285.81  4752.8 1283.86  4757.9 1284.99  4802.3 1282.31  4807.4 1283.60
  4834.5 1282.95  4849.8 1281.61  4850.0 1281.11  4853.8 1281.61  4856.9 1282.73
  4893.1 1282.42  4901.3 1283.52  4938.3 1281.85  4945.7 1281.75  4950.8 1283.13
  4995.2 1281.63  4997.9 1283.14  5010.1 1282.72  5024.4 1284.10  5030.9 1285.95
  5088.1 1289.64  5102.4 1291.17  5108.9 1293.13  5116.7 1292.72  5130.4 1294.31
#Mann=6,-1,0
  4565.0    0.05       0  4644.2    0.12       0  4834.5    0.05       0
  4849.8    0.07       0  4853.8    0.05       0  4893.1    0.12       0
Bank Sta=4849.8,4853.8
Exp/Cntr=0.3,0.1

Type RM Length L Ch R = 1,1858,128,128,128
BEGIN DESCRIPTION:
Mapping XS 6bfe86ed
END DESCRIPTION:
XS GIS Cut Line= 3
      2808153.61     10207678.89      2808250.85     10207928.92
      2808323.77     10208095.59
#Sta/Elev= 30
  4779.4 1269.48  4822.0 1267.16  4822.2 1266.66  4826.0 1267.16  4837.6 1268.64
  4853.9 1267.27  4913.7 1268.61  4932.8 1267.71  4944.9 1269.24  4962.7 1269.14
  4968.1 1270.01  4992.6 1269.31  5001.5 1267.65  5009.3 1267.41  5030.7 1271.42
  5047.0 1273.31  5063.2 1273.23  5075.9 1275.40  5093.8 1276.22  5106.8 1277.78
  5122.7 1280.51  5146.0 1281.67  5151.5 1282.97  5169.4 1284.22  5174.9 1286.33
  5192.8 1287.17  5198.3 1288.18  5221.7 1288.53  5225.7 1290.28  5229.6 1290.28
#Mann=4,-1,0
  4779.4    0.05       0  4822.0    0.05       0  4826.0    0.05       0
  5001.5    0.12       0
Bank Sta=4822,4826
Exp/Cntr=0.3,0.1

Type RM Length L Ch R = 1,1730,230,230,230
BEGIN DESCRIPTION:
Mapping XS 818ec6e0
END DESCRIPTION:
XS GIS Cut Line= 3
      2808052.94     10207706.72      2808108.49     10207911.56
      2808212.64     10208144.17
#Sta/Elev= 30
  4791.4 1263.46  4817.3 1262.15  4822.5 1262.71  4849.8 1260.86  4896.9 1259.24
  4902.1 1260.27  4912.0 1259.92  4943.1 1261.03  4976.6 1260.37  4999.8 1259.08
  5000.1 1258.58  5003.8 1259.08  5006.3 1259.08  5009.9 1260.38  5056.3 1262.61
  5061.8 1263.75  5079.5 1264.74  5084.4 1265.85  5125.9 1269.24  5136.8 1271.76
  5154.5 1271.15  5160.0 1272.58  5177.7 1273.37  5183.2 1274.51  5200.9 1274.85
  5206.4 1276.05  5224.1 1276.73  5235.4 1278.19  5252.8 1278.24  5258.5 1279.27
#Mann=4,-1,0
  4791.4    0.05       0  4999.8    0.05       0  5003.8    0.05       0
  5084.4    0.12       0
Bank Sta=4999.8,5003.8
Exp/Cntr=0.3,0.1

Type RM Length L Ch R = 1,1500,96,96,96
BEGIN DESCRIPTION:
SANFERNANDO086 3.0
END DESCRIPTION:
XS GIS Cut Line= 3
      2808005.68     10207503.12      2807902.49     10208007.57
      2808155.69     10208253.11
#Sta/Elev= 30
  4485.1 1276.56  4505.2 1275.78  4515.7 1274.14  4546.3 1272.58  4597.4 1267.53
  4763.0 1255.71  4842.3 1249.26  4852.5 1248.66  4862.4 1249.46  4883.2 1250.68
  4959.4 1248.14  5004.1 1242.98  5004.3 1242.48  5008.1 1242.98  5027.4 1244.60
  5034.4 1246.79  5091.0 1249.00  5126.5 1251.58  5147.6 1251.67  5168.9 1253.63
  5175.9 1253.27  5211.3 1258.08  5232.4 1259.37  5289.0 1266.29  5296.2 1268.05
  5318.3 1269.96  5324.5 1271.79  5331.5 1271.51  5338.7 1273.29  5352.7 1272.44
#Mann=6,-1,0
  4485.1    0.05       0  4763.0    0.12       0  4862.4    0.05       0
  5004.1    0.05       0  5008.1    0.05       0  5318.3    0.12       0
Bank Sta=5004.1,5008.1
Exp/Cntr=0.3,0.1

Type RM Length L Ch R = 1,1404,239,239,239
BEGIN DESCRIPTION:
Mapping XS 40a2706b
END DESCRIPTION:
XS GIS Cut Line= 3
      2807823.77     10207769.20      2807827.24     10208067.81
      2808007.79     10208231.00
#Sta/Elev= 30
  4692.5 1249.87  4693.3 1249.87  4786.4 1245.88  4796.4 1244.99  4816.4 1240.36
  4826.4 1243.32  4836.4 1244.59  4876.4 1244.49  4961.5 1242.31  4976.4 1241.59
  4991.1 1240.09  4991.7 1237.47  4991.9 1236.97  4995.4 1236.97  4995.7 1237.47
  5000.7 1239.69  5007.9 1238.87  5022.1 1240.83  5036.3 1241.45  5057.2 1243.47
  5064.7 1243.54  5071.4 1244.71  5093.0 1246.10  5114.0 1246.59  5128.2 1247.73
  5135.6 1249.25  5142.4 1248.84  5149.8 1250.59  5156.6 1249.55  5234.5 1255.89
#Mann=6,-1,0
  4692.5    0.12       0  4693.3    0.05       0  4961.5    0.12       0
  4991.7    0.07       0  4995.7    0.12       0  5000.7    0.05       0
Bank Sta=4991.7,4995.7
Exp/Cntr=0.3,0.1

Type RM Length L Ch R = 1,1165,165,165,165
BEGIN DESCRIPTION:
Mapping XS db06c7aa
END DESCRIPTION:
XS GIS Cut Line= 3
      2807584.19     10207821.31      2807608.49     10208158.09
      2807905.63     10208268.65
#Sta/Elev= 30
  4683.8 1238.58  4720.6 1237.50  4755.8 1236.47  4772.5 1236.48  4785.9 1237.17
  4805.9 1235.63  4831.0 1235.05  4933.9 1232.24  4988.8 1227.67  4994.4 1227.03
  4994.7 1226.53  4998.2 1226.53  4998.4 1227.03  5029.1 1230.95  5039.8 1230.88
  5078.0 1232.98  5093.1 1233.05  5103.0 1233.75  5108.3 1233.21  5188.7 1237.71
  5194.0 1237.37  5210.5 1239.53  5218.3 1239.73  5224.4 1239.53  5242.5 1240.68
  5274.4 1243.91  5295.9 1245.34  5304.7 1246.59  5327.9 1247.87  5338.5 1248.97
#Mann=8,-1,0
  4683.8    0.12       0  4720.6    0.05       0  4831.0    0.12       0
  4933.9    0.05       0  4988.8    0.12       0  4994.4    0.07       0
  4998.4    0.12       0  5218.3    0.05       0
Bank Sta=4994.4,4998.4
Exp/Cntr=0.3,0.1

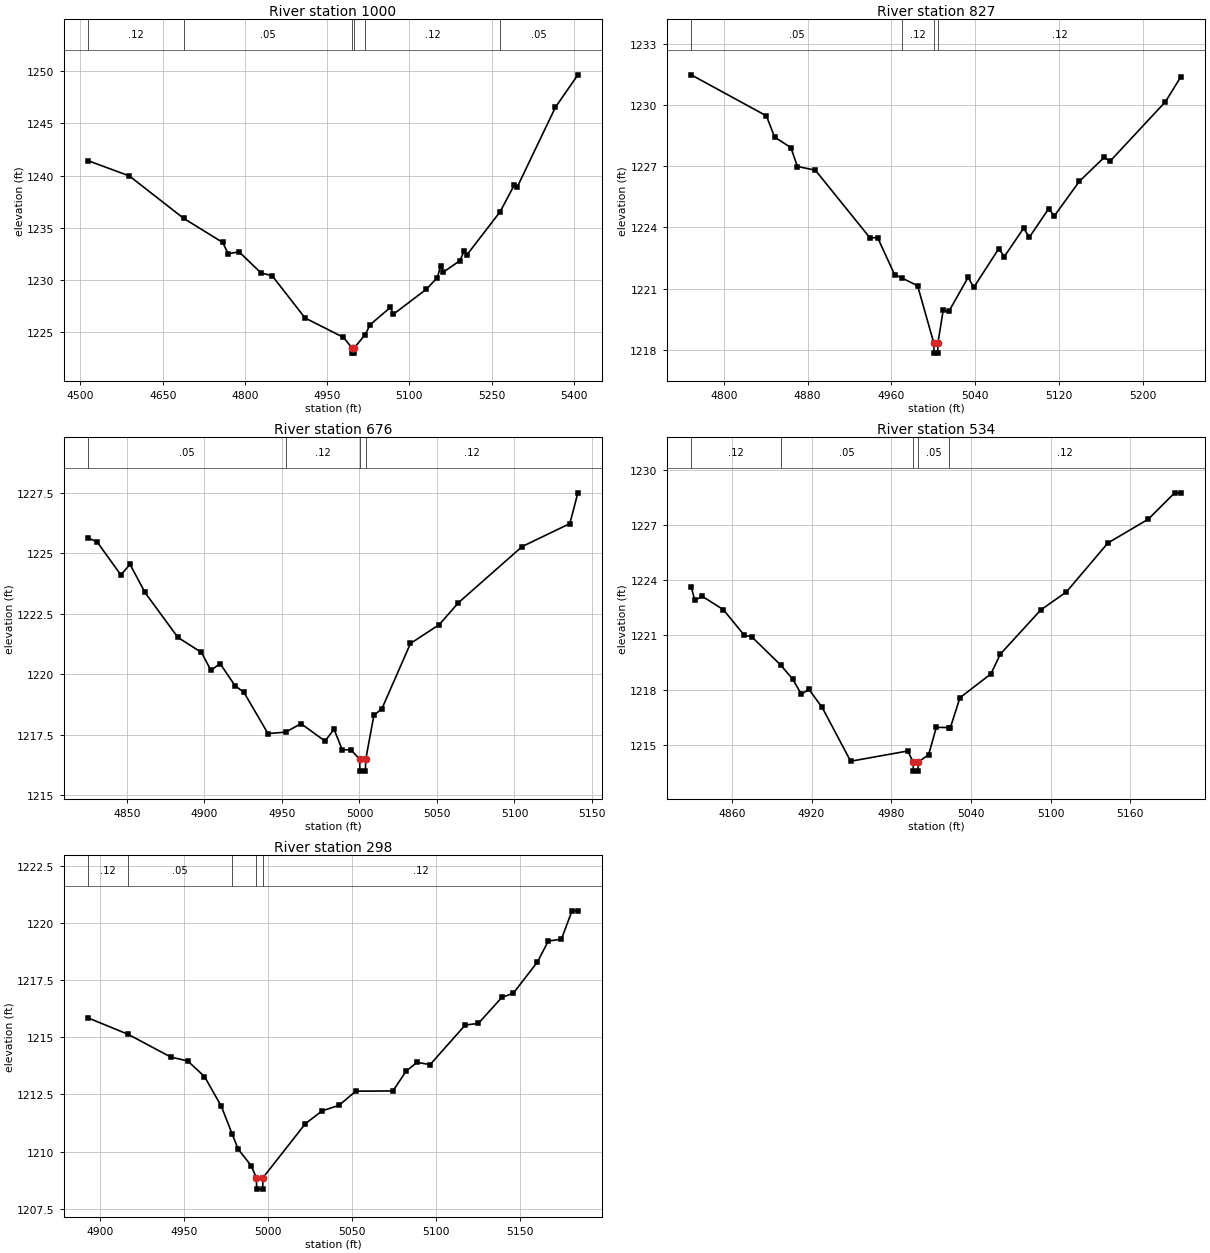
Type RM Length L Ch R = 1,1000,173,173,173
BEGIN DESCRIPTION:
SANFERNANDO086 2.0
END DESCRIPTION:
XS GIS Cut Line= 3
      2807480.68     10207778.09      2807508.20     10208263.31
      2807905.68     10208353.11
#Sta/Elev= 30
  4514.0 1241.42  4589.1 1239.96  4688.4 1235.89  4759.4 1233.59  4769.4 1232.51
  4789.5 1232.68  4829.5 1230.66  4849.6 1230.40  4909.7 1226.35  4979.8 1224.49
  4995.4 1223.48  4995.6 1222.98  4999.1 1222.98  4999.4 1223.48  5019.6 1224.76
  5028.2 1225.69  5065.6 1227.37  5070.7 1226.70  5130.7 1229.09  5151.2 1230.22
  5157.1 1231.37  5162.3 1230.75  5192.2 1231.84  5200.3 1232.81  5205.4 1232.42
  5265.5 1236.52  5291.8 1239.12  5297.0 1238.91  5366.5 1246.54  5407.5 1249.65
#Mann=6,-1,0
  4514.0    0.12       0  4688.4    0.05       0  4995.4    0.05       0
  4999.4    0.05       0  5019.6    0.12       0  5265.5    0.05       0
Bank Sta=4995.4,4999.4
Exp/Cntr=0.3,0.1

Type RM Length L Ch R = 1,827,151,151,151
BEGIN DESCRIPTION:
Mapping XS 6a1af095
END DESCRIPTION:
XS GIS Cut Line= 3
      2807382.81     10208210.22      2807469.60     10208408.09
      2807701.49     10208505.00
#Sta/Elev= 30
  4768.9 1231.47  4840.7 1229.46  4848.5 1228.42  4864.0 1227.91  4870.3 1226.98
  4887.4 1226.80  4939.6 1223.48  4946.8 1223.50  4963.0 1221.69  4970.0 1221.52
  4985.0 1221.14  5000.4 1218.34  5000.7 1217.84  5004.2 1217.84  5004.4 1218.34
  5009.4 1219.94  5014.8 1219.88  5033.2 1221.55  5038.6 1221.06  5062.4 1222.95
  5067.8 1222.57  5086.2 1223.96  5091.6 1223.51  5110.0 1224.91  5115.5 1224.56
  5139.3 1226.25  5163.1 1227.43  5168.5 1227.23  5221.5 1230.15  5236.3 1231.38
#Mann=4,-1,0
  4768.9    0.05       0  4970.0    0.12       0  5000.4    0.07       0
  5004.4    0.12       0
Bank Sta=5000.4,5004.4
Exp/Cntr=0.3,0.1

Type RM Length L Ch R = 1,676,142,142,142
BEGIN DESCRIPTION:
Mapping XS 20b092e6
END DESCRIPTION:
XS GIS Cut Line= 3
      2807379.30     10208390.69      2807466.13     10208533.09
      2807500.67     10208678.16
#Sta/Elev= 30
  4825.0 1225.62  4830.7 1225.47  4846.1 1224.10  4852.0 1224.54  4861.6 1223.38
  4882.9 1221.52  4898.1 1220.90  4904.2 1220.16  4910.1 1220.44  4919.7 1219.53
  4925.5 1219.25  4941.0 1217.55  4952.4 1217.61  4962.3 1217.96  4977.8 1217.24
  4983.6 1217.73  4988.9 1216.88  4994.4 1216.88  5000.1 1216.50  5000.3 1216.00
  5003.8 1216.00  5004.1 1216.50  5009.3 1218.30  5014.5 1218.58  5032.9 1221.27
  5051.5 1222.05  5063.8 1222.95  5104.9 1225.27  5135.7 1226.22  5140.9 1227.49
#Mann=4,-1,0
  4825.0    0.05       0  4952.4    0.12       0  5000.1    0.07       0
  5004.1    0.12       0
Bank Sta=5000.1,5004.1
Exp/Cntr=0.3,0.1

Type RM Length L Ch R = 1,534,236,236,236
BEGIN DESCRIPTION:
Mapping XS 7fa4baed
END DESCRIPTION:
XS GIS Cut Line= 3
      2807278.60     10208467.08      2807375.85     10208633.78
      2807403.63     10208807.38
#Sta/Elev= 30
  4829.4 1223.64  4832.1 1222.92  4837.9 1223.12  4853.6 1222.40  4869.3 1221.01
  4875.1 1220.91  4896.7 1219.38  4905.8 1218.61  4912.3 1217.79  4918.1 1218.04
  4928.0 1217.06  4949.5 1214.12  4992.5 1214.68  4996.5 1214.08  4996.7 1213.58
  5000.2 1213.58  5000.5 1214.08  5008.2 1214.48  5014.0 1215.97  5023.8 1215.96
  5024.6 1215.96  5031.8 1217.59  5055.1 1218.89  5062.2 1219.97  5092.6 1222.38
  5112.0 1223.37  5143.2 1226.04  5173.6 1227.34  5193.5 1228.78  5198.2 1228.78
#Mann=5,-1,0
  4829.4    0.12       0  4896.7    0.05       0  4996.5    0.05       0
  5000.5    0.05       0  5023.8    0.12       0
Bank Sta=4996.5,5000.5
Exp/Cntr=0.3,0.1

Type RM Length L Ch R = 1,298,0,0,0
BEGIN DESCRIPTION:
SANFERNANDO086 1.0
END DESCRIPTION:
XS GIS Cut Line= 3
      2807202.24     10208553.94      2807199.54     10208727.30
      2807275.14     10208817.79
#Sta/Elev= 30
  4893.1 1215.84  4917.0 1215.12  4942.3 1214.13  4952.3 1213.96  4962.3 1213.28
  4972.3 1211.98  4978.7 1210.78  4982.3 1210.11  4990.1 1209.38  4993.1 1208.86
  4993.4 1208.36  4996.9 1208.36  4997.1 1208.86  5022.3 1211.22  5032.3 1211.78
  5042.3 1212.02  5052.3 1212.64  5074.4 1212.65  5082.2 1213.51  5088.7 1213.90
  5096.5 1213.80  5117.4 1215.53  5125.2 1215.60  5139.2 1216.74  5146.0 1216.92
  5160.3 1218.28  5166.8 1219.20  5174.6 1219.28  5180.9 1220.52  5184.4 1220.52
#Mann=5,-1,0
  4893.1    0.12       0  4917.0    0.05       0  4978.7    0.12       0
  4993.1    0.07       0  4997.1    0.12       0
Bank Sta=4993.1,4997.1
Exp/Cntr=0.3,0.1

Chan Stop Cuts=-1