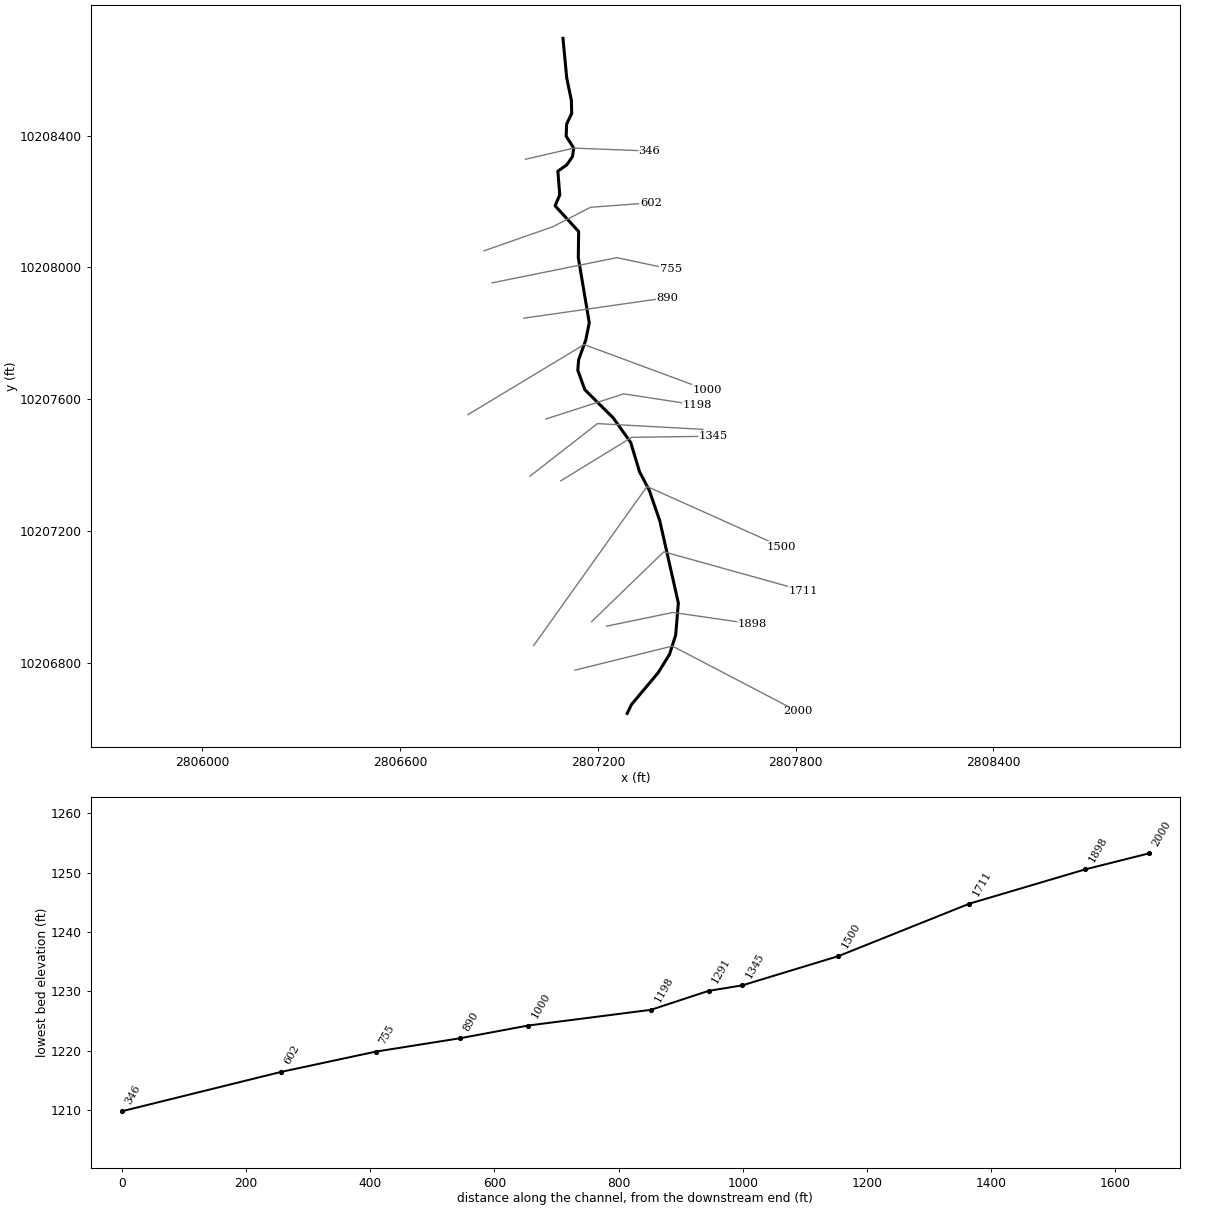
--- SANFERNANDO087.prj (project) ---

Proj Title=SANFERNANDO087 Base Level Engineering
Current Plan=p01
Default Exp/Contr=0.3,0.1
English Units
Geom File=g01
Flow File=f01
Plan File=p01
BEGIN DESCRIPTION:
SANFERNANDO087
END DESCRIPTION:

--- SANFERNANDO087.p01 (plan) ---

Plan Title=Multiple Run
Short Identifier=Multiple
Geom File=g01
Flow File=f01
Subcritical Flow
K Sum by GR= 0
Std Step Tol= 0.01
Critical Tol= 0.01
Num of Std Step Trials= 20
Max Error Tol= 0.3
Flow Tol Ratio= 0.001
Split Flow NTrial= 30
Split Flow Tol= 0.02
Split Flow Ratio= 0.02
Log Output Level= 0
Friction Slope Method= 1
Unsteady Friction Slope Method= 2
Unsteady Bridges Friction Slope Method= 1
Parabolic Critical Depth
Global Vel Dist=  1 , 1 , 1
Global Log Level= 0
CheckData=True
Encroach Param= -1, 0, 0, 0
BEGIN DESCRIPTION:
Multiple Run
END DESCRIPTION:

--- SANFERNANDO087.f01 (steady flow) ---

Flow Title=Multiple
Number of Profiles=7
Profile Names=10-year,25-year,50-year,1pct_min,100-year,1pct_plu,500-year
River Rch & RM= SANFERNANDO087,Reach-1,2000
      49      69      74      45      90     181     124
Boundary for River Rch & Prof#=SANFERNANDO087,Reach-1,1
Up Type=0
Dn Type=3
Dn Slope=0.005
Boundary for River Rch & Prof#=SANFERNANDO087,Reach-1,2
Up Type=0
Dn Type=3
Dn Slope=0.005
Boundary for River Rch & Prof#=SANFERNANDO087,Reach-1,3
Up Type=0
Dn Type=3
Dn Slope=0.005
Boundary for River Rch & Prof#=SANFERNANDO087,Reach-1,4
Up Type=0
Dn Type=3
Dn Slope=0.005
Boundary for River Rch & Prof#=SANFERNANDO087,Reach-1,5
Up Type=0
Dn Type=3
Dn Slope=0.005
Boundary for River Rch & Prof#=SANFERNANDO087,Reach-1,6
Up Type=0
Dn Type=3
Dn Slope=0.005
Boundary for River Rch & Prof#=SANFERNANDO087,Reach-1,7
Up Type=0
Dn Type=3
Dn Slope=0.005

--- SANFERNANDO087.g01 (geometry) ---

Geom Title=Existing Conditions

River Reach=SANFERNANDO087,Reach-1
Reach XY= 30
      2807289.00     10206647.00      2807302.25     10206674.00
      2807382.75     10206770.00      2807417.50     10206826.00
      2807436.25     10206885.00      2807444.25     10206982.00
      2807388.00     10207231.00      2807356.00     10207324.00
      2807326.50     10207380.00      2807299.75     10207469.00
      2807246.25     10207544.00      2807160.50     10207629.00
      2807139.25     10207688.00      2807141.75     10207720.00
      2807163.25     10207779.00      2807174.00     10207832.00
      2807140.75     10208030.00      2807141.75     10208109.00
      2807070.25     10208187.00      2807084.50     10208220.00
      2807078.75     10208292.00      2807105.75     10208311.00
      2807123.00     10208336.00      2807127.00     10208362.00
      2807104.00     10208398.00      2807105.25     10208435.00
      2807120.75     10208467.00      2807119.75     10208507.00
      2807105.75     10208574.00      2807094.25     10208695.00

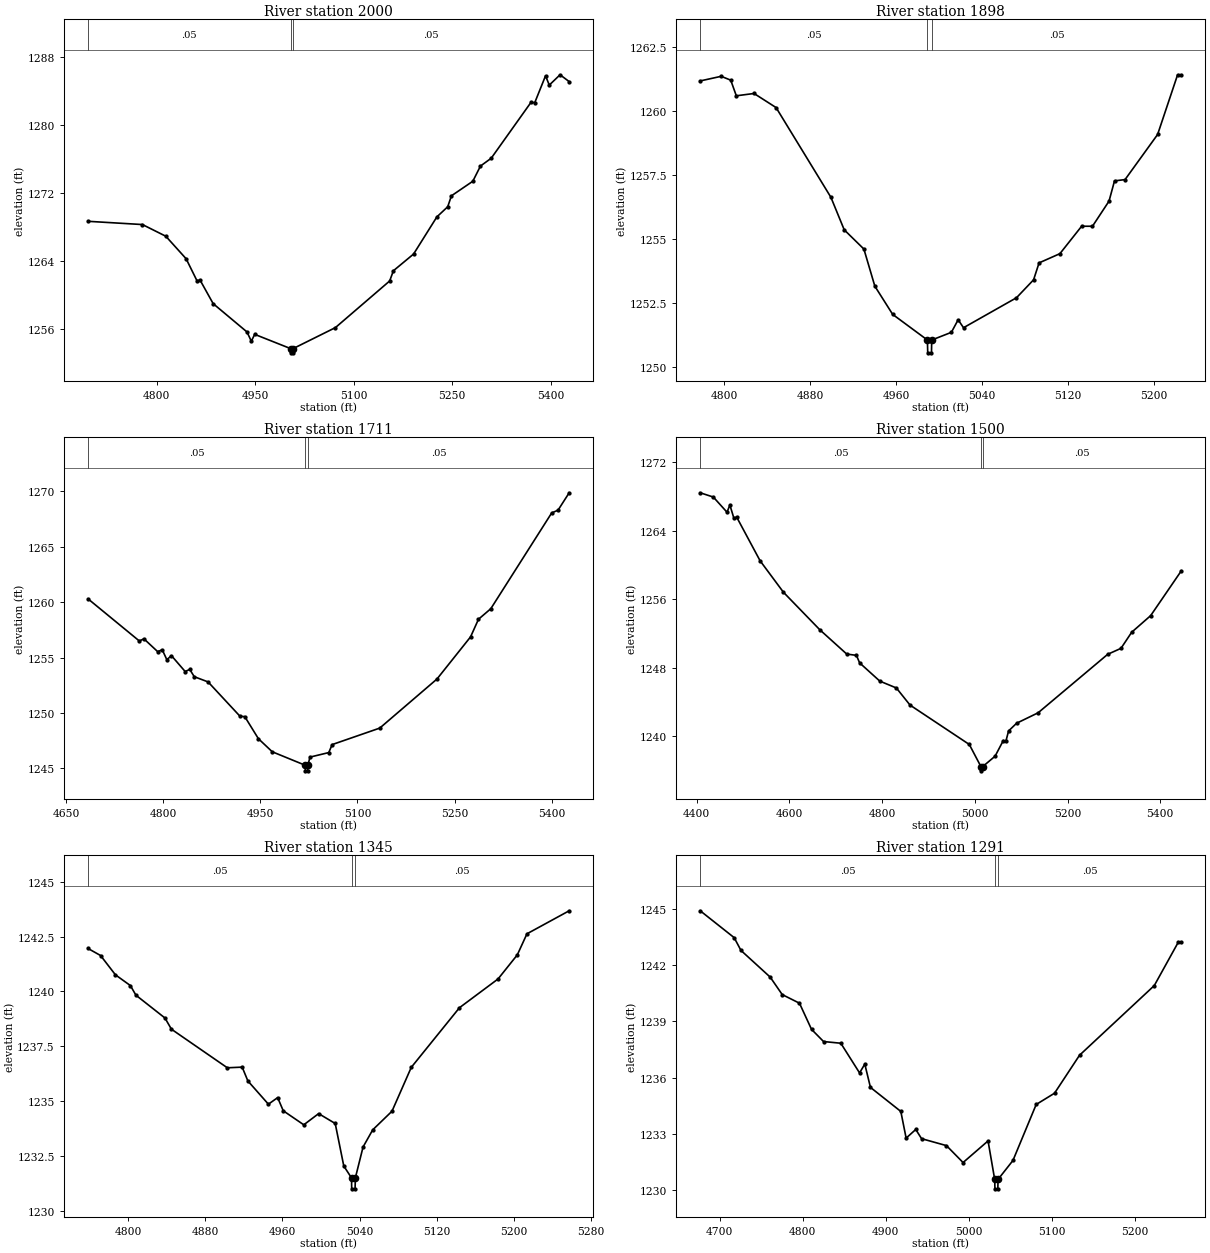
Type RM Length L Ch R = 1,2000,102,102,102
BEGIN DESCRIPTION:
SANFERNANDO087 4.0
END DESCRIPTION:
XS GIS Cut Line= 3
      2807130.72     10206778.12      2807426.32     10206851.21
      2807805.71     10206653.10
#Sta/Elev= 30
  4695.5 1268.67  4778.3 1268.29  4813.9 1266.92  4844.8 1264.28  4861.2 1261.72
  4866.3 1261.74  4886.0 1259.01  4937.5 1255.69  4944.1 1254.60  4949.2 1255.41
  5003.8 1253.74  5004.1 1253.24  5007.6 1253.24  5007.8 1253.74  5072.1 1256.20
  5154.7 1261.67  5160.4 1262.87  5191.1 1264.83  5226.6 1269.19  5243.1 1270.38
  5248.7 1271.66  5281.3 1273.37  5292.9 1275.15  5309.3 1276.07  5369.9 1282.63
  5375.6 1282.59  5392.0 1285.74  5397.7 1284.65  5414.1 1285.86  5428.0 1285.06
#Mann=3,-1,0
  4695.5    0.05       0  5003.8    0.05       0  5007.8    0.05       0
Bank Sta=5003.8,5007.8
Exp/Cntr=0.3,0.1

Type RM Length L Ch R = 1,1898,187,187,187
BEGIN DESCRIPTION:
Mapping XS 3ee988e4
END DESCRIPTION:
XS GIS Cut Line= 3
      2807226.58     10206911.57      2807427.93     10206953.23
      2807667.52     10206918.51
#Sta/Elev= 30
  4777.9 1261.17  4797.4 1261.35  4806.3 1261.20  4811.5 1260.59  4828.0 1260.68
  4848.5 1260.13  4899.5 1256.63  4911.9 1255.36  4930.2 1254.61  4940.4 1253.16
  4957.0 1252.06  4989.3 1251.06  4989.6 1250.56  4993.1 1250.56  4993.3 1251.06
  5011.6 1251.36  5017.9 1251.85  5022.9 1251.54  5072.2 1252.71  5088.1 1253.41
  5093.2 1254.07  5112.6 1254.43  5132.8 1255.50  5142.9 1255.50  5158.3 1256.48
  5163.4 1257.27  5173.2 1257.32  5203.5 1259.08  5222.1 1261.41  5225.6 1261.41
#Mann=3,-1,0
  4777.9    0.05       0  4989.3    0.05       0  4993.3    0.05       0
Bank Sta=4989.3,4993.3
Exp/Cntr=0.3,0.1

Type RM Length L Ch R = 1,1711,211,211,211
BEGIN DESCRIPTION:
Mapping XS ef4bd32e
END DESCRIPTION:
XS GIS Cut Line= 3
      2807181.40     10206925.44      2807400.16     10207137.26
      2807822.27     10207019.62
#Sta/Elev= 30
  4684.2 1260.30  4763.3 1256.50  4770.5 1256.69  4791.6 1255.54  4798.8 1255.70
  4805.8 1254.81  4813.0 1255.17  4834.1 1253.74  4841.2 1253.93  4848.2 1253.27
  4869.5 1252.80  4918.9 1249.69  4926.1 1249.67  4947.2 1247.67  4968.6 1246.49
  5019.6 1245.27  5019.8 1244.77  5023.3 1244.77  5023.6 1245.27  5026.8 1246.01
  5055.8 1246.42  5061.0 1247.14  5134.5 1248.63  5222.8 1253.06  5274.7 1256.87
  5286.9 1258.46  5305.9 1259.41  5399.9 1268.06  5409.7 1268.31  5426.9 1269.88
#Mann=3,-1,0
  4684.2    0.05       0  5019.6    0.05       0  5023.6    0.05       0
Bank Sta=5019.6,5023.6
Exp/Cntr=0.3,0.1

Type RM Length L Ch R = 1,1500,155,155,155
BEGIN DESCRIPTION:
SANFERNANDO087 3.0
END DESCRIPTION:
XS GIS Cut Line= 3
      2807005.66     10206853.08      2807349.16     10207335.36
      2807755.68     10207153.11
#Sta/Elev= 30
  4407.9 1268.41  4436.2 1267.91  4465.7 1266.14  4471.9 1266.98  4480.5 1265.44
  4486.6 1265.56  4537.0 1260.47  4587.4 1256.79  4665.8 1252.41  4723.9 1249.57
  4744.8 1249.42  4751.7 1248.54  4795.2 1246.41  4830.9 1245.61  4860.4 1243.61
  4988.2 1239.01  5013.2 1236.43  5013.4 1235.93  5017.2 1236.43  5043.8 1237.64
  5061.5 1239.47  5067.0 1239.37  5072.9 1240.59  5090.2 1241.49  5136.6 1242.71
  5286.6 1249.54  5315.3 1250.24  5338.4 1252.12  5379.3 1254.06  5445.5 1259.30
#Mann=3,-1,0
  4407.9    0.05       0  5013.2    0.05       0  5017.2    0.05       0
Bank Sta=5013.2,5017.2
Exp/Cntr=0.3,0.1

Type RM Length L Ch R = 1,1345,54,54,54
BEGIN DESCRIPTION:
Mapping XS 12f92f9a
END DESCRIPTION:
XS GIS Cut Line= 3
      2807087.63     10207352.52      2807302.93     10207484.48
      2807549.49     10207487.95
#Sta/Elev= 30
  4758.3 1241.96  4771.3 1241.64  4786.7 1240.76  4802.2 1240.27  4808.0 1239.83
  4838.1 1238.79  4844.8 1238.28  4902.8 1236.52  4918.2 1236.55  4924.1 1235.92
  4945.4 1234.86  4955.0 1235.16  4960.8 1234.56  4982.1 1233.92  4997.5 1234.43
  5014.7 1233.98  5023.6 1232.04  5031.6 1231.50  5031.8 1231.00  5035.3 1231.00
  5035.6 1231.50  5043.6 1232.91  5053.6 1233.69  5073.6 1234.54  5093.6 1236.54
  5143.6 1239.26  5183.6 1240.57  5203.6 1241.67  5213.6 1242.63  5257.4 1243.68
#Mann=3,-1,0
  4758.3    0.05       0  5031.6    0.05       0  5035.6    0.05       0
Bank Sta=5031.6,5035.6
Exp/Cntr=0.3,0.1

Type RM Length L Ch R = 1,1291,93,93,93
BEGIN DESCRIPTION:
Mapping XS f0c8e802
END DESCRIPTION:
XS GIS Cut Line= 3
      2806993.92     10207366.44      2807198.77     10207526.14
      2807518.25     10207508.78
#Sta/Elev= 30
  4676.7 1244.88  4717.6 1243.45  4725.8 1242.77  4761.0 1241.35  4775.5 1240.42
  4796.3 1239.96  4810.8 1238.57  4825.3 1237.92  4846.1 1237.83  4868.7 1236.25
  4875.0 1236.72  4881.8 1235.48  4918.4 1234.20  4924.8 1232.78  4936.4 1233.24
  4943.4 1232.75  4973.4 1232.38  4993.4 1231.48  5023.5 1232.63  5031.5 1230.58
  5031.8 1230.08  5035.3 1230.08  5035.5 1230.58  5053.5 1231.59  5081.5 1234.57
  5103.6 1235.17  5133.7 1237.19  5223.8 1240.90  5252.6 1243.20  5256.4 1243.20
#Mann=3,-1,0
  4676.7    0.05       0  5031.5    0.05       0  5035.5    0.05       0
Bank Sta=5031.5,5035.5
Exp/Cntr=0.3,0.1

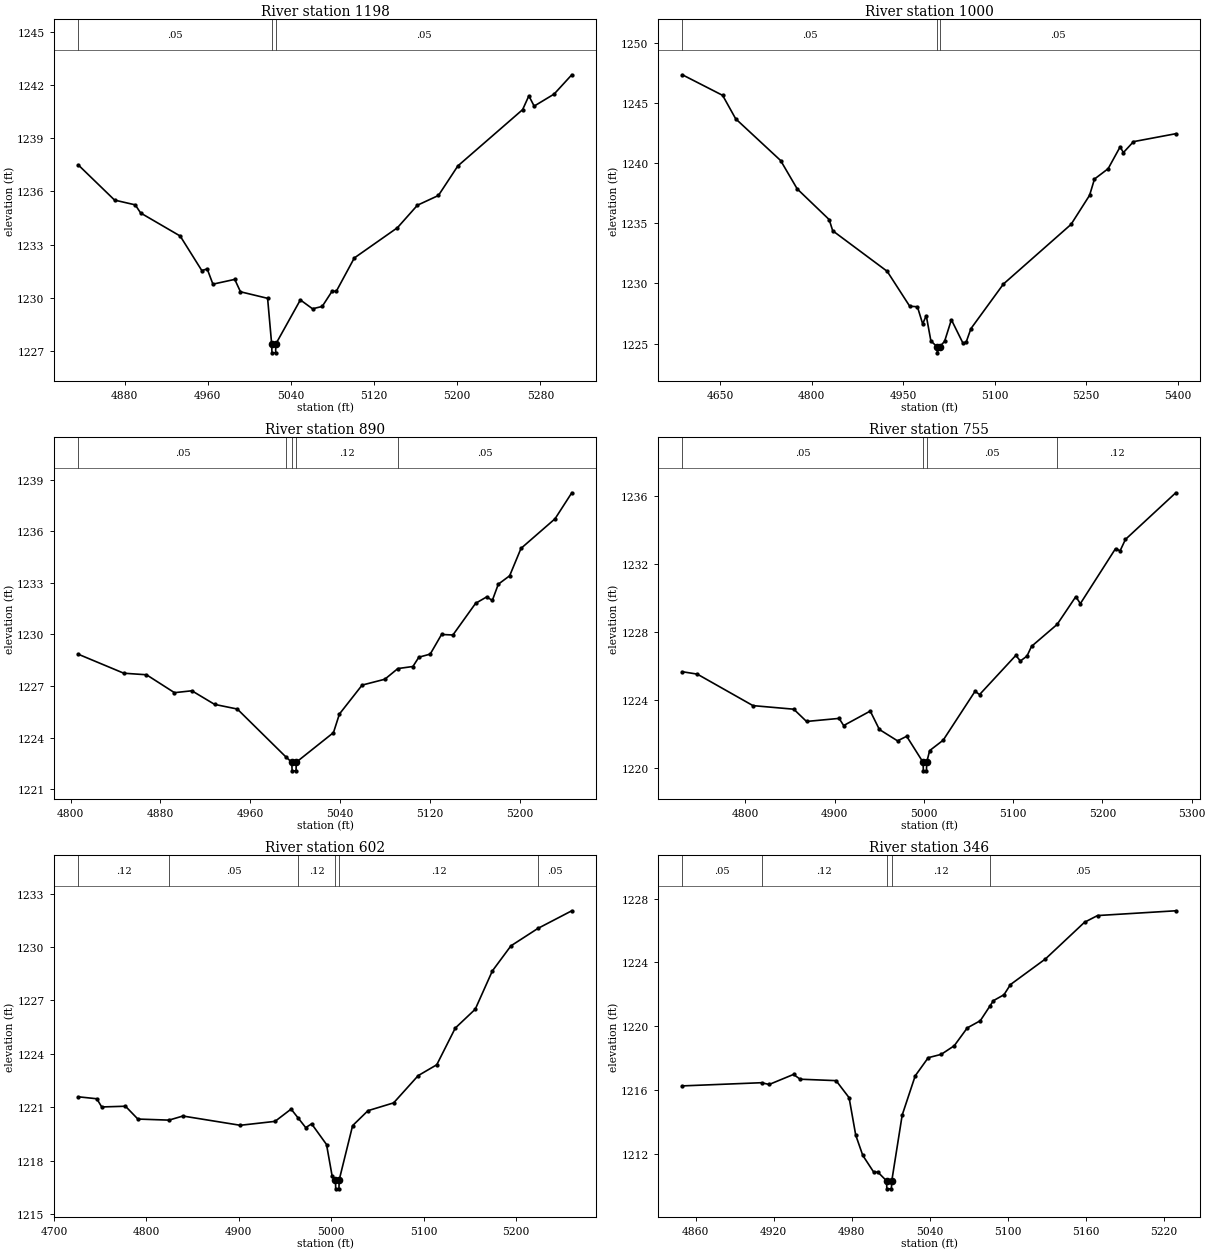
Type RM Length L Ch R = 1,1198,198,198,198
BEGIN DESCRIPTION:
Mapping XS 52c53452
END DESCRIPTION:
XS GIS Cut Line= 3
      2807042.54     10207540.04      2807278.63     10207616.42
      2807502.46     10207581.99
#Sta/Elev= 30
  4835.6 1237.49  4870.4 1235.51  4890.3 1235.24  4895.5 1234.78  4933.5 1233.48
  4954.3 1231.53  4959.5 1231.62  4965.0 1230.76  4986.0 1231.03  4991.5 1230.33
  5017.6 1229.96  5021.5 1227.38  5021.8 1226.88  5025.3 1226.88  5025.5 1227.38
  5049.1 1229.87  5060.8 1229.37  5070.1 1229.50  5079.6 1230.36  5083.7 1230.36
  5101.0 1232.24  5142.5 1233.95  5161.7 1235.22  5181.9 1235.77  5200.6 1237.44
  5262.9 1240.62  5268.9 1241.40  5274.0 1240.82  5293.2 1241.50  5310.2 1242.59
#Mann=3,-1,0
  4835.6    0.05       0  5021.5    0.05       0  5025.5    0.05       0
Bank Sta=5021.5,5025.5
Exp/Cntr=0.3,0.1

Type RM Length L Ch R = 1,1000,110,110,110
BEGIN DESCRIPTION:
SANFERNANDO087 2.0
END DESCRIPTION:
XS GIS Cut Line= 3
      2806805.67     10207553.11      2807158.42     10207765.98
      2807530.71     10207628.10
#Sta/Elev= 30
  4588.0 1247.35  4654.0 1245.64  4675.4 1243.69  4749.1 1240.22  4776.3 1237.86
  4828.7 1235.31  4834.5 1234.38  4923.8 1231.01  4960.7 1228.11  4973.4 1228.06
  4982.0 1226.64  4987.9 1227.32  4995.5 1225.22  5005.7 1224.73  5006.0 1224.23
  5009.7 1224.73  5017.9 1225.18  5029.1 1226.98  5048.3 1225.01  5053.6 1225.16
  5061.1 1226.24  5114.4 1229.95  5225.3 1234.91  5255.7 1237.33  5263.7 1238.68
  5286.1 1239.54  5305.8 1241.36  5311.1 1240.88  5327.7 1241.79  5397.0 1242.45
#Mann=3,-1,0
  4588.0    0.05       0  5005.7    0.03       0  5009.7    0.05       0
Bank Sta=5005.7,5009.7
Exp/Cntr=0.3,0.1

Type RM Length L Ch R = 1,890,135,135,135
BEGIN DESCRIPTION:
Mapping XS ce402e50
END DESCRIPTION:
XS GIS Cut Line= 2
      2806975.71     10207846.06      2807410.39     10207908.15
#Sta/Elev= 30
  4807.0 1228.85  4847.4 1227.75  4867.6 1227.66  4892.5 1226.62  4908.0 1226.73
  4928.2 1225.94  4948.4 1225.67  4992.1 1222.86  4996.9 1222.58  4997.2 1222.08
  5000.7 1222.08  5000.9 1222.58  5034.0 1224.30  5039.3 1225.38  5059.5 1227.06
  5079.7 1227.40  5091.3 1228.02  5104.7 1228.14  5110.0 1228.68  5120.1 1228.86
  5130.2 1230.00  5140.3 1229.97  5160.5 1231.81  5170.3 1232.18  5175.4 1231.98
  5180.7 1232.92  5190.8 1233.41  5200.9 1235.00  5231.2 1236.72  5246.1 1238.23
#Mann=5,-1,0
  4807.0    0.05       0  4992.1    0.12       0  4996.9    0.07       0
  5000.9    0.12       0  5091.3    0.05       0
Bank Sta=4996.9,5000.9
Exp/Cntr=0.3,0.1

Type RM Length L Ch R = 1,755,153,153,153
BEGIN DESCRIPTION:
Mapping XS 210411cf
END DESCRIPTION:
XS GIS Cut Line= 3
      2806879.31     10207953.22      2807257.79     10208029.62
      2807420.83     10207994.93
#Sta/Elev= 30
  4729.4 1225.66  4746.1 1225.52  4808.5 1223.67  4854.2 1223.46  4868.5 1222.74
  4905.0 1222.92  4910.1 1222.50  4939.9 1223.35  4950.1 1222.27  4970.5 1221.60
  4980.7 1221.87  4999.1 1220.34  4999.4 1219.84  5002.9 1219.84  5003.1 1220.34
  5006.5 1221.03  5021.6 1221.64  5057.3 1224.51  5062.4 1224.32  5103.0 1226.62
  5108.1 1226.29  5115.5 1226.58  5120.6 1227.15  5149.3 1228.44  5170.2 1230.07
  5175.3 1229.66  5214.7 1232.89  5219.8 1232.76  5225.8 1233.43  5282.2 1236.17
#Mann=4,-1,0
  4729.4    0.05       0  4999.1    0.05       0  5003.1    0.05       0
  5149.3    0.12       0
Bank Sta=4999.1,5003.1
Exp/Cntr=0.3,0.1

Type RM Length L Ch R = 1,602,256,256,256
BEGIN DESCRIPTION:
Mapping XS e33c9a0e
END DESCRIPTION:
XS GIS Cut Line= 4
      2806855.02     10208050.45      2807063.35     10208123.37
      2807177.93     10208182.39      2807361.30     10208196.23
#Sta/Elev= 30
  4726.5 1221.58  4746.4 1221.47  4751.7 1221.01  4777.4 1221.05  4790.8 1220.33
  4824.4 1220.27  4839.5 1220.50  4901.5 1219.98  4939.1 1220.20  4956.5 1220.89
  4963.8 1220.41  4972.3 1219.85  4978.7 1220.06  4994.8 1218.90  5000.9 1217.12
  5004.5 1216.91  5004.7 1216.41  5008.2 1216.41  5008.5 1216.91  5023.0 1219.96
  5039.6 1220.80  5067.4 1221.24  5093.9 1222.77  5114.0 1223.38  5134.0 1225.44
  5155.6 1226.50  5174.1 1228.65  5194.2 1230.06  5223.4 1231.04  5260.0 1232.03
#Mann=6,-1,0
  4726.5    0.12       0  4824.4    0.05       0  4963.8    0.12       0
  5004.5    0.07       0  5008.5    0.12       0  5223.4    0.05       0
Bank Sta=5004.5,5008.5
Exp/Cntr=0.3,0.1

Type RM Length L Ch R = 1,346,0,0,0
BEGIN DESCRIPTION:
SANFERNANDO087 1.0
END DESCRIPTION:
XS GIS Cut Line= 3
      2806980.67     10208328.11      2807127.00     10208362.00
      2807355.73     10208353.11
#Sta/Elev= 30
  4849.8 1216.25  4910.6 1216.45  4916.5 1216.34  4935.2 1216.97  4940.3 1216.67
  4967.9 1216.58  4977.9 1215.51  4983.0 1213.16  4988.4 1211.89  4996.8 1210.84
  5000.0 1210.84  5006.7 1210.29  5006.9 1209.79  5010.4 1209.79  5010.7 1210.29
  5018.7 1214.42  5028.7 1216.88  5038.7 1218.02  5048.7 1218.23  5058.7 1218.77
  5068.7 1219.89  5078.7 1220.34  5086.1 1221.26  5088.8 1221.60  5096.9 1221.97
  5101.9 1222.61  5128.8 1224.22  5158.8 1226.52  5168.8 1226.94  5228.9 1227.24
#Mann=5,-1,0
  4849.8    0.05       0  4910.6    0.12       0  5006.7    0.07       0
  5010.7    0.12       0  5086.1    0.05       0
Bank Sta=5006.7,5010.7
Exp/Cntr=0.3,0.1

Chan Stop Cuts=-1