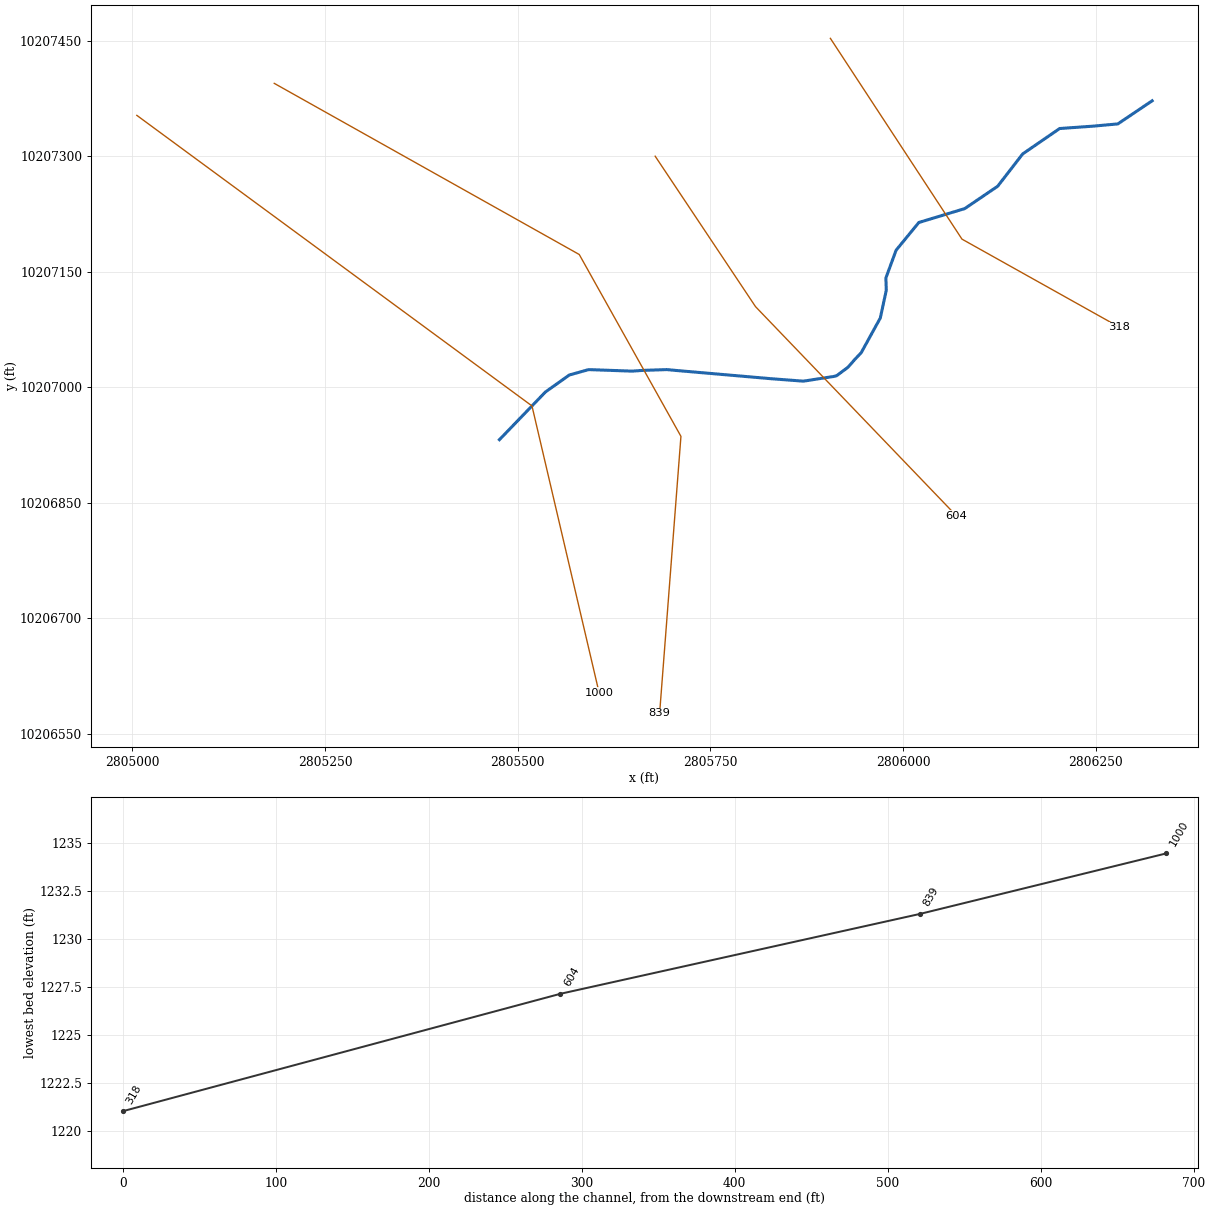
--- SANFERNANDO088.prj (project) ---

Proj Title=SANFERNANDO088 Base Level Engineering
Current Plan=p01
Default Exp/Contr=0.3,0.1
English Units
Geom File=g01
Flow File=f01
Plan File=p01
BEGIN DESCRIPTION:
SANFERNANDO088
END DESCRIPTION:

--- SANFERNANDO088.p01 (plan) ---

Plan Title=Multiple Run
Short Identifier=Multiple
Geom File=g01
Flow File=f01
Subcritical Flow
K Sum by GR= 0
Std Step Tol= 0.01
Critical Tol= 0.01
Num of Std Step Trials= 20
Max Error Tol= 0.3
Flow Tol Ratio= 0.001
Split Flow NTrial= 30
Split Flow Tol= 0.02
Split Flow Ratio= 0.02
Log Output Level= 0
Friction Slope Method= 1
Unsteady Friction Slope Method= 2
Unsteady Bridges Friction Slope Method= 1
Parabolic Critical Depth
Global Vel Dist=  1 , 1 , 1
Global Log Level= 0
CheckData=True
Encroach Param= -1, 0, 0, 0
BEGIN DESCRIPTION:
Multiple Run
END DESCRIPTION:

--- SANFERNANDO088.f01 (steady flow) ---

Flow Title=Multiple
Number of Profiles=7
Profile Names=10-year,25-year,50-year,1pct_min,100-year,1pct_plu,500-year
River Rch & RM= SANFERNANDO088,Reach-1,1000
     153     231     588     446     826    1530    1258
Boundary for River Rch & Prof#=SANFERNANDO088,Reach-1,1
Up Type=0
Dn Type=3
Dn Slope=0.005
Boundary for River Rch & Prof#=SANFERNANDO088,Reach-1,2
Up Type=0
Dn Type=3
Dn Slope=0.005
Boundary for River Rch & Prof#=SANFERNANDO088,Reach-1,3
Up Type=0
Dn Type=3
Dn Slope=0.005
Boundary for River Rch & Prof#=SANFERNANDO088,Reach-1,4
Up Type=0
Dn Type=3
Dn Slope=0.005
Boundary for River Rch & Prof#=SANFERNANDO088,Reach-1,5
Up Type=0
Dn Type=3
Dn Slope=0.005
Boundary for River Rch & Prof#=SANFERNANDO088,Reach-1,6
Up Type=0
Dn Type=3
Dn Slope=0.005
Boundary for River Rch & Prof#=SANFERNANDO088,Reach-1,7
Up Type=0
Dn Type=3
Dn Slope=0.005

--- SANFERNANDO088.g01 (geometry) ---

Geom Title=Existing Conditions

River Reach=SANFERNANDO088,Reach-1
Reach XY= 27
      2805476.25     10206932.00      2805536.00     10206994.00
      2805567.00     10207016.00      2805592.00     10207023.00
      2805648.50     10207021.00      2805662.75     10207022.00
      2805693.50     10207023.00      2805704.25     10207022.00
      2805830.75     10207011.00      2805870.75     10207008.00
      2805909.50     10207014.00      2805913.75     10207015.00
      2805928.50     10207026.00      2805937.25     10207036.00
      2805945.75     10207045.00      2805970.50     10207090.00
      2805978.25     10207126.00      2805977.75     10207142.00
      2805991.00     10207178.00      2806020.50     10207214.00
      2806080.00     10207232.00      2806122.75     10207261.00
      2806155.25     10207303.00      2806203.25     10207336.00
      2806245.75     10207339.00      2806278.75     10207342.00
      2806323.25     10207372.00

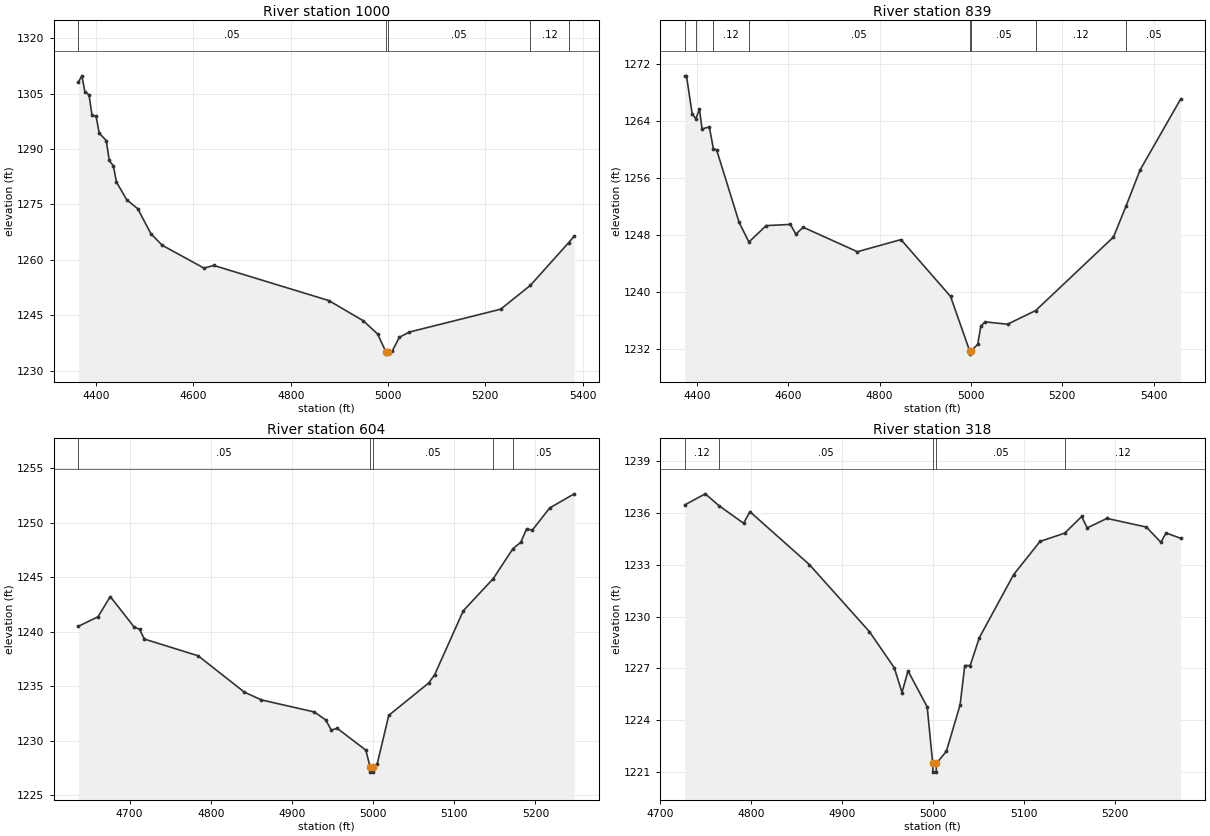
Type RM Length L Ch R = 1,1000,161,161,161
BEGIN DESCRIPTION:
SANFERNANDO088 2.0
END DESCRIPTION:
XS GIS Cut Line= 3
      2805005.72     10207353.09      2805518.49     10206975.84
      2805605.69     10206603.10
#Sta/Elev= 30
  4363.4 1308.12  4370.7 1309.85  4376.9 1305.53  4385.3 1304.72  4391.5 1299.21
  4400.0 1298.86  4406.2 1294.36  4420.8 1292.32  4427.0 1286.92  4435.5 1285.44
  4441.7 1281.10  4462.7 1276.30  4485.6 1273.84  4512.7 1267.06  4535.8 1263.96
  4621.4 1257.79  4642.2 1258.48  4878.3 1248.98  4949.3 1243.50  4978.6 1239.92
  4996.1 1234.97  4996.3 1234.47  5000.1 1234.97  5008.8 1235.30  5023.3 1239.03
  5043.9 1240.45  5231.5 1246.64  5292.5 1253.07  5371.4 1264.67  5382.8 1266.43
#Mann=5,-1,0
  4363.4    0.05       0  4996.1    0.05       0  5000.1    0.05       0
  5292.5    0.12       0  5371.4    0.05       0
Bank Sta=4996.1,5000.1
Exp/Cntr=0.3,0.1

Type RM Length L Ch R = 1,839,235,235,235
BEGIN DESCRIPTION:
Mapping XS 1d95f505
END DESCRIPTION:
XS GIS Cut Line= 4
      2805184.05     10207394.64      2805579.84     10207172.44
      2805711.79     10206936.33      2805684.12     10206576.67
#Sta/Elev= 30
  4373.8 1270.31  4377.6 1270.31  4390.0 1265.01  4398.1 1264.29  4406.0 1265.65
  4411.7 1262.87  4427.6 1263.15  4436.4 1260.11  4443.6 1259.93  4492.7 1249.79
  4514.2 1247.02  4552.0 1249.32  4605.0 1249.49  4617.0 1248.12  4633.0 1249.09
  4751.6 1245.66  4847.0 1247.36  4955.5 1239.39  4997.0 1231.81  4997.2 1231.31
  5001.0 1231.81  5014.9 1232.68  5021.7 1235.23  5030.9 1235.83  5080.1 1235.50
  5141.8 1237.42  5312.0 1247.72  5339.6 1252.08  5370.3 1257.13  5458.9 1267.05
#Mann=8,-1,0
  4373.8    0.12       0  4398.1    0.05       0  4436.4    0.12       0
  4514.2    0.05       0  4997.0    0.05       0  5001.0    0.05       0
  5141.8    0.12       0  5339.6    0.05       0
Bank Sta=4997,5001
Exp/Cntr=0.3,0.1

Type RM Length L Ch R = 1,604,286,286,286
BEGIN DESCRIPTION:
Mapping XS 74f807ed
END DESCRIPTION:
XS GIS Cut Line= 3
      2805678.37     10207300.05      2805808.58     10207104.73
      2806069.01     10206833.45
#Sta/Elev= 30
  4636.9 1240.51  4661.2 1241.39  4676.2 1243.24  4705.3 1240.48  4712.3 1240.23
  4718.3 1239.34  4784.4 1237.81  4841.5 1234.47  4862.5 1233.76  4927.4 1232.66
  4941.6 1231.93  4948.5 1230.99  4955.7 1231.16  4991.0 1229.16  4996.2 1227.64
  4996.4 1227.14  4999.9 1227.14  5000.2 1227.64  5005.1 1227.92  5019.3 1232.35
  5068.6 1235.32  5075.9 1236.09  5111.1 1241.94  5148.0 1244.89  5172.1 1247.62
  5181.9 1248.22  5189.1 1249.46  5196.0 1249.32  5217.4 1251.36  5247.7 1252.66
#Mann=5,-1,0
  4636.9    0.05       0  4996.2    0.05       0  5000.2    0.05       0
  5148.0    0.12       0  5172.1    0.05       0
Bank Sta=4996.2,5000.2
Exp/Cntr=0.3,0.1

Type RM Length L Ch R = 1,318,0,0,0
BEGIN DESCRIPTION:
SANFERNANDO088 1.0
END DESCRIPTION:
XS GIS Cut Line= 3
      2805905.70     10207453.09      2806076.45     10207192.41
      2806280.71     10207078.10
#Sta/Elev= 30
  4726.8 1236.45  4749.4 1237.09  4764.6 1236.40  4791.6 1235.39  4798.5 1236.06
  4864.0 1233.00  4930.0 1229.13  4957.4 1227.04  4965.9 1225.61  4972.5 1226.86
  4993.6 1224.78  4999.7 1221.51  5000.0 1221.01  5003.5 1221.01  5003.7 1221.51
  5014.7 1222.21  5029.8 1224.89  5035.0 1227.17  5040.9 1227.17  5051.0 1228.78
  5088.7 1232.42  5117.8 1234.34  5145.0 1234.82  5163.6 1235.78  5169.7 1235.12
  5191.4 1235.67  5234.8 1235.17  5250.8 1234.29  5256.5 1234.83  5272.5 1234.52
#Mann=5,-1,0
  4726.8    0.12       0  4764.6    0.05       0  4999.7    0.05       0
  5003.7    0.05       0  5145.0    0.12       0
Bank Sta=4999.7,5003.7
Exp/Cntr=0.3,0.1

Chan Stop Cuts=-1