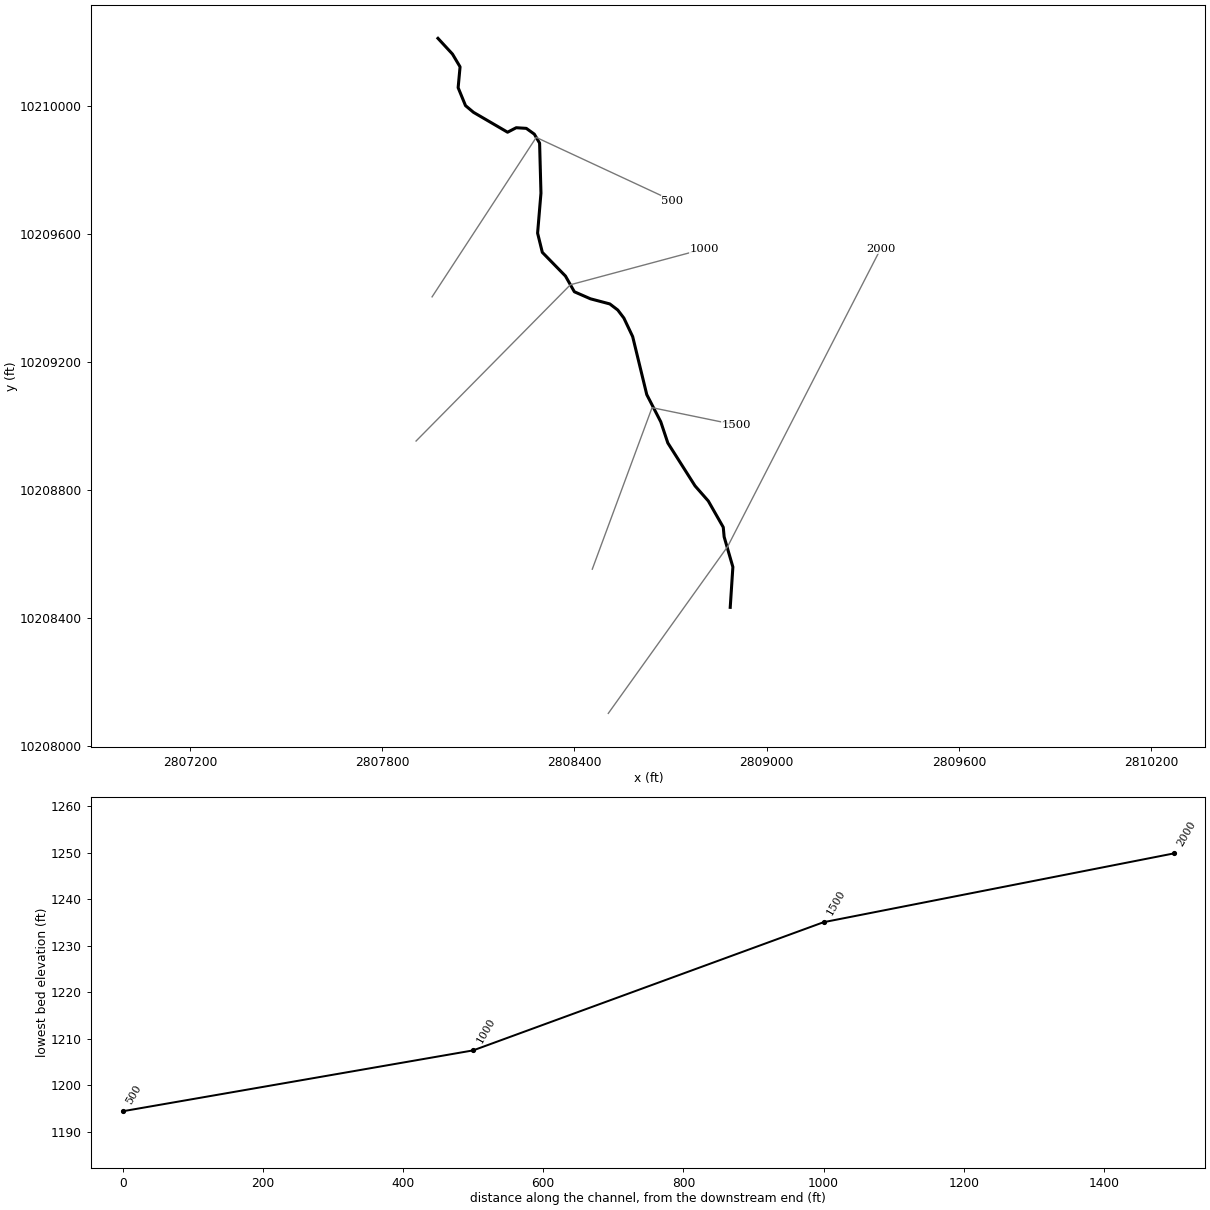
--- SANFERNANDO090.prj (project) ---

Proj Title=SANFERNANDO090 Base Level Engineering
Current Plan=p01
Default Exp/Contr=0.3,0.1
English Units
Geom File=g01
Flow File=f01
Plan File=p01
BEGIN DESCRIPTION:
SANFERNANDO090
END DESCRIPTION:

--- SANFERNANDO090.p01 (plan) ---

Plan Title=Multiple Run
Short Identifier=Multiple
Geom File=g01
Flow File=f01
Subcritical Flow
K Sum by GR= 0
Std Step Tol= 0.01
Critical Tol= 0.01
Num of Std Step Trials= 20
Max Error Tol= 0.3
Flow Tol Ratio= 0.001
Split Flow NTrial= 30
Split Flow Tol= 0.02
Split Flow Ratio= 0.02
Log Output Level= 0
Friction Slope Method= 1
Unsteady Friction Slope Method= 2
Unsteady Bridges Friction Slope Method= 1
Parabolic Critical Depth
Global Vel Dist=  1 , 1 , 1
Global Log Level= 0
CheckData=True
Encroach Param= -1, 0, 0, 0
BEGIN DESCRIPTION:
Multiple Run
END DESCRIPTION:

--- SANFERNANDO090.f01 (steady flow) ---

Flow Title=Multiple
Number of Profiles=7
Profile Names=10-year,25-year,50-year,1pct_min,100-year,1pct_plu,500-year
River Rch & RM= SANFERNANDO090,Reach-1,2000
      50      70     102      64     130     261     185
Boundary for River Rch & Prof#=SANFERNANDO090,Reach-1,1
Up Type=0
Dn Type=3
Dn Slope=0.005
Boundary for River Rch & Prof#=SANFERNANDO090,Reach-1,2
Up Type=0
Dn Type=3
Dn Slope=0.005
Boundary for River Rch & Prof#=SANFERNANDO090,Reach-1,3
Up Type=0
Dn Type=3
Dn Slope=0.005
Boundary for River Rch & Prof#=SANFERNANDO090,Reach-1,4
Up Type=0
Dn Type=3
Dn Slope=0.005
Boundary for River Rch & Prof#=SANFERNANDO090,Reach-1,5
Up Type=0
Dn Type=3
Dn Slope=0.005
Boundary for River Rch & Prof#=SANFERNANDO090,Reach-1,6
Up Type=0
Dn Type=3
Dn Slope=0.005
Boundary for River Rch & Prof#=SANFERNANDO090,Reach-1,7
Up Type=0
Dn Type=3
Dn Slope=0.005

--- SANFERNANDO090.g01 (geometry) ---

Geom Title=Existing Conditions

River Reach=SANFERNANDO090,Reach-1
Reach XY= 30
      2808886.25     10208434.00      2808894.50     10208560.00
      2808867.25     10208654.00      2808864.50     10208684.00
      2808817.75     10208766.00      2808776.50     10208813.00
      2808691.50     10208947.00      2808669.50     10209013.00
      2808625.75     10209098.00      2808581.75     10209279.00
      2808554.25     10209337.00      2808535.25     10209362.00
      2808510.50     10209381.00      2808450.00     10209397.00
      2808399.75     10209419.00      2808372.00     10209468.00
      2808299.75     10209542.00      2808285.00     10209602.00
      2808295.50     10209727.00      2808291.25     10209883.00
      2808274.75     10209911.00      2808249.75     10209929.00
      2808218.25     10209931.00      2808191.25     10209917.00
      2808085.00     10209979.00      2808060.00     10210000.00
      2808037.00     10210056.00      2808043.00     10210121.00
      2808019.25     10210161.00      2807974.00     10210210.00

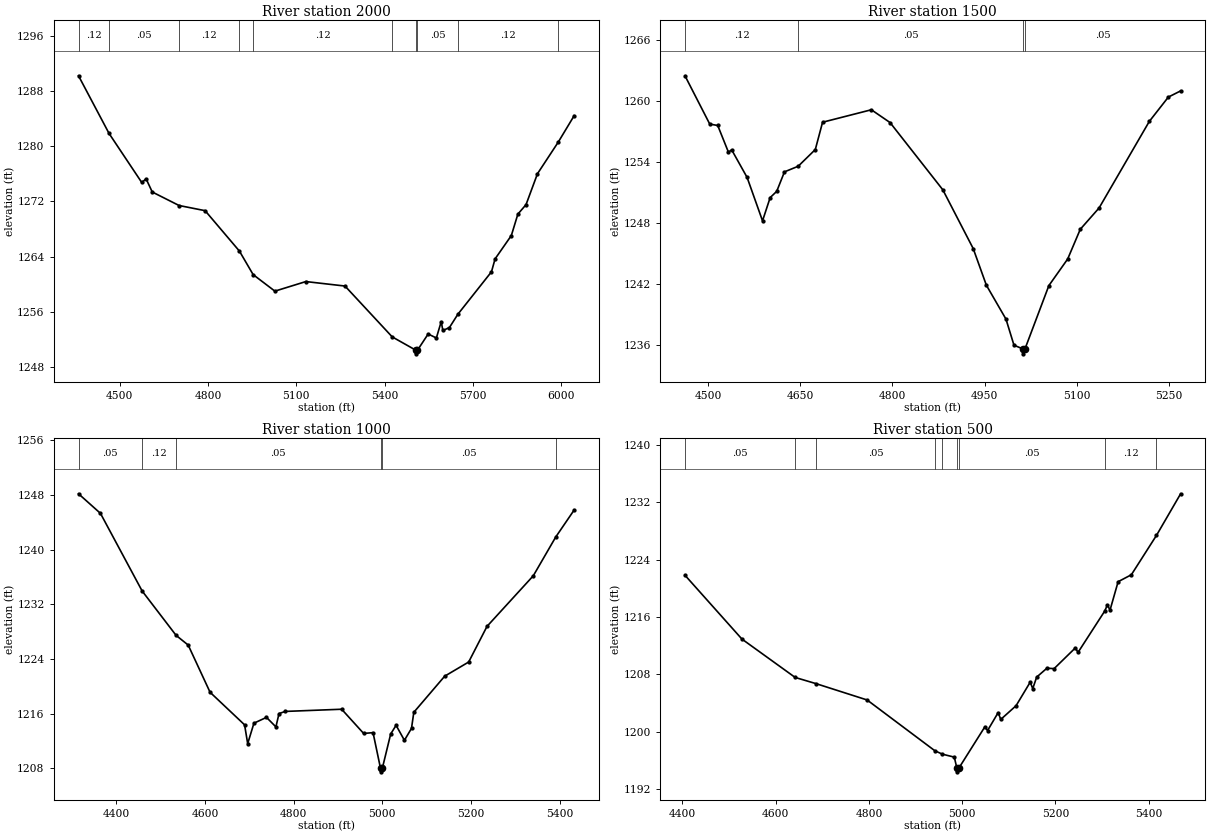
Type RM Length L Ch R = 1,2000,500,500,500
BEGIN DESCRIPTION:
SANFERNANDO090 4.0
END DESCRIPTION:
XS GIS Cut Line= 3
      2808505.66     10208103.07      2808878.28     10208623.90
      2809355.70     10209553.14
#Sta/Elev= 30
  4359.6 1290.24  4463.4 1281.87  4574.6 1274.75  4589.4 1275.28  4610.3 1273.37
  4701.5 1271.41  4790.0 1270.66  4906.7 1264.79  4953.3 1261.38  5027.2 1258.98
  5132.5 1260.37  5265.6 1259.72  5426.1 1252.34  5507.6 1250.38  5507.8 1249.88
  5511.6 1250.38  5548.3 1252.76  5576.2 1252.18  5592.7 1254.55  5598.3 1253.27
  5620.5 1253.69  5649.4 1255.63  5763.6 1261.79  5775.8 1263.66  5831.1 1267.05
  5853.3 1270.16  5881.1 1271.54  5919.9 1276.02  5991.0 1280.64  6044.7 1284.45
#Mann=10,-1,0
  4359.6    0.12       0  4463.4    0.05       0  4701.5    0.12       0
  4906.7    0.05       0  4953.3    0.12       0  5426.1    0.05       0
  5507.6    0.07       0  5511.6    0.05       0  5649.4    0.12       0
  5991.0    0.05       0
Bank Sta=5507.6,5511.6
Exp/Cntr=0.3,0.1

Type RM Length L Ch R = 1,1500,500,500,500
BEGIN DESCRIPTION:
SANFERNANDO090 3.0
END DESCRIPTION:
XS GIS Cut Line= 3
      2808455.68     10208553.11      2808642.19     10209057.32
      2808905.67     10209003.11
#Sta/Elev= 30
  4462.4 1262.49  4502.7 1257.73  4515.7 1257.59  4533.1 1254.96  4538.4 1255.19
  4563.5 1252.47  4588.6 1248.19  4601.0 1250.48  4611.7 1251.10  4624.3 1253.02
  4646.6 1253.57  4674.5 1255.22  4686.3 1257.91  4765.7 1259.14  4796.1 1257.88
  4882.0 1251.25  4931.5 1245.45  4952.9 1241.84  4984.8 1238.50  4997.8 1235.93
  5011.8 1235.58  5012.0 1235.08  5015.8 1235.58  5054.6 1241.81  5085.2 1244.43
  5105.7 1247.36  5136.3 1249.46  5218.0 1257.99  5249.0 1260.39  5269.0 1261.00
#Mann=4,-1,0
  4462.4    0.12       0  4646.6    0.05       0  5011.8    0.05       0
  5015.8    0.05       0
Bank Sta=5011.8,5015.8
Exp/Cntr=0.3,0.1

Type RM Length L Ch R = 1,1000,500,500,500
BEGIN DESCRIPTION:
SANFERNANDO090 2.0
END DESCRIPTION:
XS GIS Cut Line= 3
      2807905.69     10208953.12      2808387.36     10209440.88
      2808805.67     10209553.11
#Sta/Elev= 30
  4314.5 1248.15  4364.0 1245.29  4458.1 1233.94  4534.8 1227.45  4562.0 1226.04
  4611.4 1219.14  4689.3 1214.38  4696.3 1211.63  4710.4 1214.62  4738.7 1215.47
  4760.0 1214.08  4767.0 1216.03  4781.2 1216.34  4908.4 1216.66  4958.0 1213.12
  4979.2 1213.24  4996.1 1208.01  4996.3 1207.51  5000.1 1208.01  5019.0 1213.04
  5031.2 1214.31  5050.0 1212.12  5066.0 1213.86  5071.2 1216.21  5140.9 1221.49
  5195.0 1223.56  5236.4 1228.77  5340.9 1236.17  5391.4 1241.82  5433.1 1245.78
#Mann=6,-1,0
  4314.5    0.05       0  4458.1    0.12       0  4534.8    0.05       0
  4996.1    0.03       0  5000.1    0.05       0  5391.4    0.12       0
Bank Sta=4996.1,5000.1
Exp/Cntr=0.3,0.1

Type RM Length L Ch R = 1,500,0,0,0
BEGIN DESCRIPTION:
SANFERNANDO090 1.0
END DESCRIPTION:
XS GIS Cut Line= 3
      2807955.66     10209403.08      2808280.74     10209900.83
      2808705.70     10209703.11
#Sta/Elev= 30
  4405.5 1221.83  4527.7 1212.93  4641.9 1207.58  4686.5 1206.72  4796.2 1204.44
  4941.5 1197.36  4957.8 1196.88  4983.2 1196.47  4988.8 1194.92  4989.0 1194.42
  4992.8 1194.92  5049.0 1200.72  5054.5 1200.17  5077.3 1202.68  5082.9 1201.73
  5115.7 1203.64  5146.0 1206.92  5151.5 1206.03  5159.9 1207.63  5181.9 1208.87
  5197.3 1208.81  5243.0 1211.71  5248.6 1211.07  5305.7 1216.82  5311.7 1217.70
  5317.2 1216.96  5334.6 1220.93  5363.0 1221.90  5416.9 1227.39  5468.7 1233.19
#Mann=9,-1,0
  4405.5    0.05       0  4641.9    0.12       0  4686.5    0.05       0
  4941.5    0.12       0  4957.8    0.05       0  4988.8    0.05       0
  4992.8    0.05       0  5305.7    0.12       0  5416.9    0.05       0
Bank Sta=4988.8,4992.8
Exp/Cntr=0.3,0.1

Chan Stop Cuts=-1