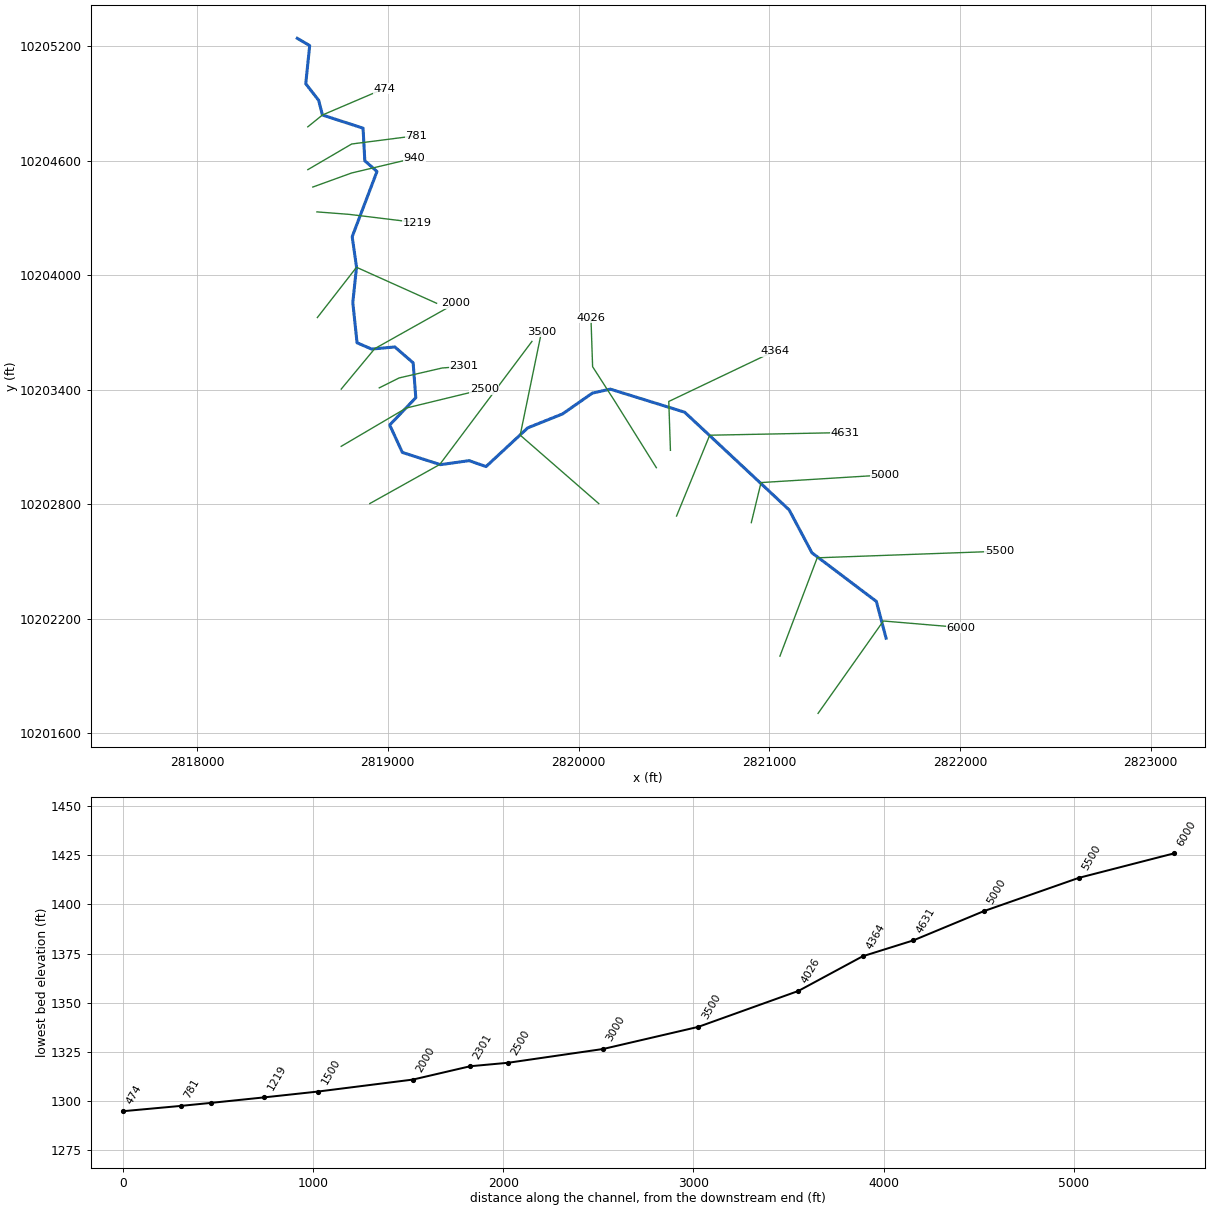
--- SANFERNANDO091.prj (project) ---

Proj Title=SANFERNANDO091 Base Level Engineering
Current Plan=p01
Default Exp/Contr=0.3,0.1
English Units
Geom File=g01
Flow File=f01
Plan File=p01
BEGIN DESCRIPTION:
SANFERNANDO091
END DESCRIPTION:

--- SANFERNANDO091.p01 (plan) ---

Plan Title=Multiple Run
Short Identifier=Multiple
Geom File=g01
Flow File=f01
Subcritical Flow
K Sum by GR= 0
Std Step Tol= 0.01
Critical Tol= 0.01
Num of Std Step Trials= 20
Max Error Tol= 0.3
Flow Tol Ratio= 0.001
Split Flow NTrial= 30
Split Flow Tol= 0.02
Split Flow Ratio= 0.02
Log Output Level= 0
Friction Slope Method= 1
Unsteady Friction Slope Method= 2
Unsteady Bridges Friction Slope Method= 1
Parabolic Critical Depth
Global Vel Dist=  1 , 1 , 1
Global Log Level= 0
CheckData=True
Encroach Param= -1, 0, 0, 0
BEGIN DESCRIPTION:
Multiple Run
END DESCRIPTION:

--- SANFERNANDO091.f01 (steady flow) ---

Flow Title=Multiple
Number of Profiles=7
Profile Names=10-year,25-year,50-year,1pct_min,100-year,1pct_plu,500-year
River Rch & RM= SANFERNANDO091,Reach-1,6000
     353     568    1213     790    1714    3715    2545
Boundary for River Rch & Prof#=SANFERNANDO091,Reach-1,1
Up Type=0
Dn Type=3
Dn Slope=0.005
Boundary for River Rch & Prof#=SANFERNANDO091,Reach-1,2
Up Type=0
Dn Type=3
Dn Slope=0.005
Boundary for River Rch & Prof#=SANFERNANDO091,Reach-1,3
Up Type=0
Dn Type=3
Dn Slope=0.005
Boundary for River Rch & Prof#=SANFERNANDO091,Reach-1,4
Up Type=0
Dn Type=3
Dn Slope=0.005
Boundary for River Rch & Prof#=SANFERNANDO091,Reach-1,5
Up Type=0
Dn Type=3
Dn Slope=0.005
Boundary for River Rch & Prof#=SANFERNANDO091,Reach-1,6
Up Type=0
Dn Type=3
Dn Slope=0.005
Boundary for River Rch & Prof#=SANFERNANDO091,Reach-1,7
Up Type=0
Dn Type=3
Dn Slope=0.005

--- SANFERNANDO091.g01 (geometry) ---

Geom Title=Existing Conditions

River Reach=SANFERNANDO091,Reach-1
Reach XY= 30
      2821612.25     10202097.00      2821561.25     10202290.00
      2821223.50     10202545.00      2821104.00     10202770.00
      2820556.25     10203282.00      2820166.25     10203403.00
      2820072.25     10203382.00      2819916.25     10203273.00
      2819733.75     10203200.00      2819515.00     10202997.00
      2819426.50     10203028.00      2819275.50     10203007.00
      2819076.25     10203071.00      2819010.00     10203215.00
      2819146.75     10203358.00      2819132.75     10203541.00
      2819037.00     10203624.00      2818915.25     10203613.00
      2818838.75     10203646.00      2818816.50     10203857.00
      2818836.00     10204043.00      2818813.25     10204202.00
      2818943.25     10204544.00      2818879.50     10204600.00
      2818870.25     10204771.00      2818657.25     10204840.00
      2818637.50     10204917.00      2818569.75     10205004.00
      2818590.50     10205204.00      2818525.50     10205242.00

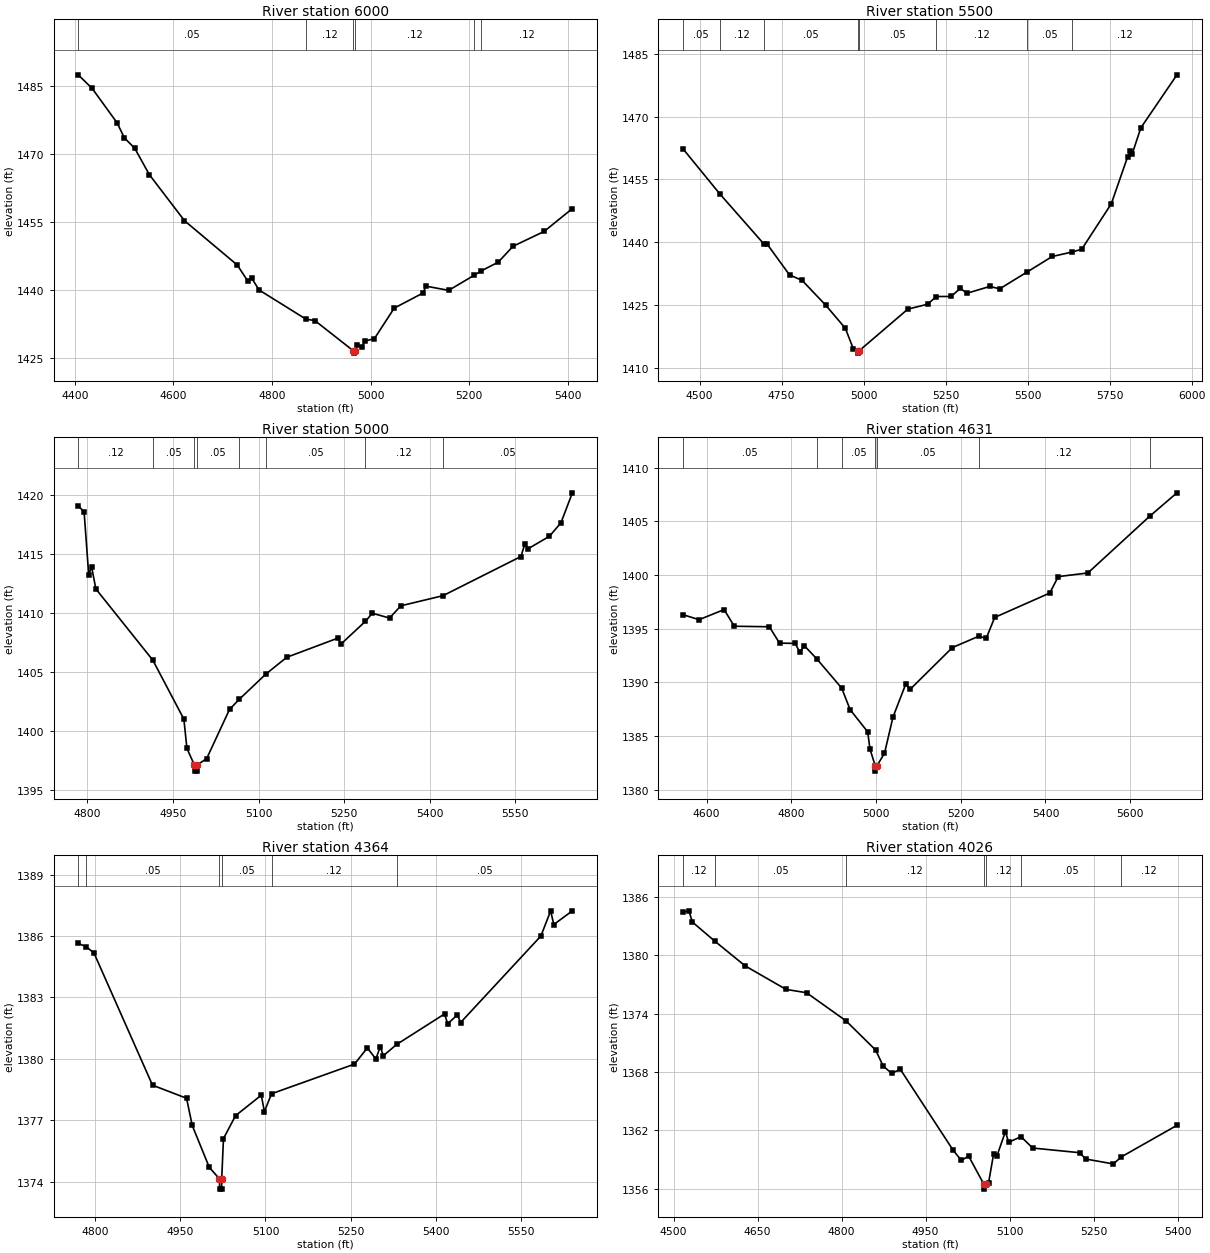
Type RM Length L Ch R = 1,6000,500,500,500
BEGIN DESCRIPTION:
SANFERNANDO091 12.0
END DESCRIPTION:
XS GIS Cut Line= 3
      2821255.67     10201703.09      2821597.90     10202187.37
      2822005.67     10202153.11
#Sta/Elev= 30
  4407.0 1487.40  4435.3 1484.39  4485.8 1476.81  4500.6 1473.48  4521.5 1471.22
  4551.1 1465.40  4622.5 1455.23  4729.5 1445.45  4750.5 1441.98  4759.1 1442.50
  4773.9 1439.94  4868.5 1433.54  4887.1 1433.18  4965.2 1426.52  4965.4 1426.02
  4969.2 1426.52  4973.3 1427.91  4982.0 1427.33  4988.1 1428.65  5007.8 1429.24
  5047.9 1435.95  5106.9 1439.31  5111.9 1440.80  5158.3 1439.86  5209.8 1443.18
  5224.8 1444.18  5258.7 1446.07  5288.8 1449.58  5351.8 1452.85  5409.2 1457.90
#Mann=6,-1,0
  4407.0    0.05       0  4868.5    0.12       0  4965.2    0.07       0
  4969.2    0.12       0  5209.8    0.05       0  5224.8    0.12       0
Bank Sta=4965.2,4969.2
Exp/Cntr=0.3,0.1

Type RM Length L Ch R = 1,5500,500,500,500
BEGIN DESCRIPTION:
SANFERNANDO091 11.0
END DESCRIPTION:
XS GIS Cut Line= 3
      2821055.68     10202003.11      2821251.12     10202518.60
      2822205.70     10202553.11
#Sta/Elev= 30
  4448.7 1462.36  4561.3 1451.57  4695.4 1439.64  4705.4 1439.61  4774.0 1432.22
  4812.3 1430.92  4883.9 1425.04  4944.2 1419.48  4969.0 1414.49  4981.4 1414.06
  4981.7 1413.56  4985.4 1414.06  5134.7 1424.06  5194.7 1425.22  5221.7 1427.07
  5266.5 1427.08  5294.8 1429.02  5314.8 1427.84  5384.8 1429.48  5414.8 1428.90
  5496.7 1432.84  5574.9 1436.62  5636.3 1437.70  5665.0 1438.36  5755.1 1449.21
  5805.1 1460.48  5813.4 1461.70  5818.4 1461.03  5845.1 1467.32  5955.2 1479.97
#Mann=8,-1,0
  4448.7    0.05       0  4561.3    0.12       0  4695.4    0.05       0
  4981.4    0.05       0  4985.4    0.05       0  5221.7    0.12       0
  5496.7    0.05       0  5636.3    0.12       0
Bank Sta=4981.4,4985.4
Exp/Cntr=0.3,0.1

Type RM Length L Ch R = 1,5000,369,369,369
BEGIN DESCRIPTION:
SANFERNANDO091 10.0
END DESCRIPTION:
XS GIS Cut Line= 3
      2820905.69     10202703.12      2820956.70     10202913.11
      2821605.67     10202953.11
#Sta/Elev= 30
  4783.9 1419.09  4794.2 1418.55  4802.2 1413.25  4807.3 1413.90  4814.8 1412.03
  4914.6 1405.99  4969.1 1400.99  4974.4 1398.51  4987.7 1397.08  4988.0 1396.58
  4991.5 1396.58  4991.7 1397.08  5009.0 1397.64  5049.1 1401.81  5066.6 1402.69
  5112.6 1404.80  5149.3 1406.23  5239.1 1407.86  5244.2 1407.34  5287.3 1409.28
  5299.5 1409.97  5329.6 1409.56  5349.6 1410.60  5423.5 1411.46  5560.0 1414.78
  5567.0 1415.86  5572.0 1415.42  5610.1 1416.50  5630.2 1417.64  5650.2 1420.18
#Mann=8,-1,0
  4783.9    0.12       0  4914.6    0.05       0  4987.7    0.05       0
  4991.7    0.05       0  5066.6    0.12       0  5112.6    0.05       0
  5287.3    0.12       0  5423.5    0.05       0
Bank Sta=4987.7,4991.7
Exp/Cntr=0.3,0.1

Type RM Length L Ch R = 1,4631,267,267,267
BEGIN DESCRIPTION:
Mapping XS fe2457c5
END DESCRIPTION:
XS GIS Cut Line= 3
      2820513.86     10202737.71      2820687.49     10203161.37
      2821395.80     10203175.26
#Sta/Elev= 30
  4544.0 1396.31  4582.3 1395.84  4641.4 1396.78  4665.4 1395.23  4748.2 1395.18
  4772.2 1393.66  4809.2 1393.63  4820.0 1392.82  4831.0 1393.41  4860.9 1392.16
  4919.0 1389.47  4938.9 1387.46  4980.3 1385.40  4985.7 1383.80  4998.1 1382.24
  4998.3 1381.74  5002.1 1382.24  5020.0 1383.40  5040.1 1386.78  5070.1 1389.84
  5080.1 1389.34  5180.1 1393.24  5242.6 1394.30  5260.1 1394.10  5280.1 1396.05
  5410.1 1398.32  5430.1 1399.85  5500.1 1400.19  5646.2 1405.48  5710.3 1407.65
#Mann=7,-1,0
  4544.0    0.05       0  4860.9    0.12       0  4919.0    0.05       0
  4998.1    0.05       0  5002.1    0.05       0  5242.6    0.12       0
  5646.2    0.05       0
Bank Sta=4998.1,5002.1
Exp/Cntr=0.3,0.1

Type RM Length L Ch R = 1,4364,338,338,338
BEGIN DESCRIPTION:
Mapping XS 9701edeb
END DESCRIPTION:
XS GIS Cut Line= 3
      2820481.68     10203082.15      2820473.00     10203338.25
      2821028.59     10203603.02
#Sta/Elev= 30
  4769.7 1385.64  4784.0 1385.47  4797.4 1385.17  4900.7 1378.71  4960.8 1378.07
  4970.8 1376.74  5000.8 1374.70  5018.8 1374.13  5019.1 1373.63  5022.6 1373.63
  5022.8 1374.13  5025.9 1376.10  5047.2 1377.22  5092.6 1378.22  5098.1 1377.42
  5110.7 1378.29  5257.0 1379.74  5279.7 1380.53  5294.8 1379.99  5302.4 1380.59
  5308.0 1380.15  5331.4 1380.70  5415.9 1382.19  5421.5 1381.71  5438.6 1382.15
  5444.2 1381.77  5585.9 1386.00  5603.1 1387.23  5608.6 1386.56  5641.4 1387.23
#Mann=6,-1,0
  4769.7    0.12       0  4784.0    0.05       0  5018.8    0.05       0
  5022.8    0.05       0  5110.7    0.12       0  5331.4    0.05       0
Bank Sta=5018.8,5022.8
Exp/Cntr=0.3,0.1

Type RM Length L Ch R = 1,4026,526,526,526
BEGIN DESCRIPTION:
Mapping XS 810f4ae7
END DESCRIPTION:
XS GIS Cut Line= 4
      2820407.88     10202991.05      2820190.88     10203338.25
      2820073.69     10203520.54      2820065.01     10203776.65
#Sta/Elev= 30
  4516.5 1384.41  4527.5 1384.55  4533.3 1383.41  4573.7 1381.43  4627.7 1378.90
  4700.8 1376.48  4737.4 1376.14  4807.7 1373.26  4860.9 1370.25  4874.2 1368.61
  4889.5 1367.86  4904.8 1368.28  4998.7 1360.01  5013.9 1358.91  5026.8 1359.37
  5054.1 1356.47  5054.4 1355.97  5058.1 1356.47  5062.5 1356.62  5071.3 1359.53
  5077.3 1359.36  5092.5 1361.87  5098.4 1360.78  5120.4 1361.36  5141.2 1360.19
  5225.3 1359.71  5235.9 1359.06  5285.3 1358.56  5299.5 1359.28  5398.9 1362.52
#Mann=7,-1,0
  4516.5    0.12       0  4573.7    0.05       0  4807.7    0.12       0
  5054.1    0.07       0  5058.1    0.12       0  5120.4    0.05       0
  5299.5    0.12       0
Bank Sta=5054.1,5058.1
Exp/Cntr=0.3,0.1

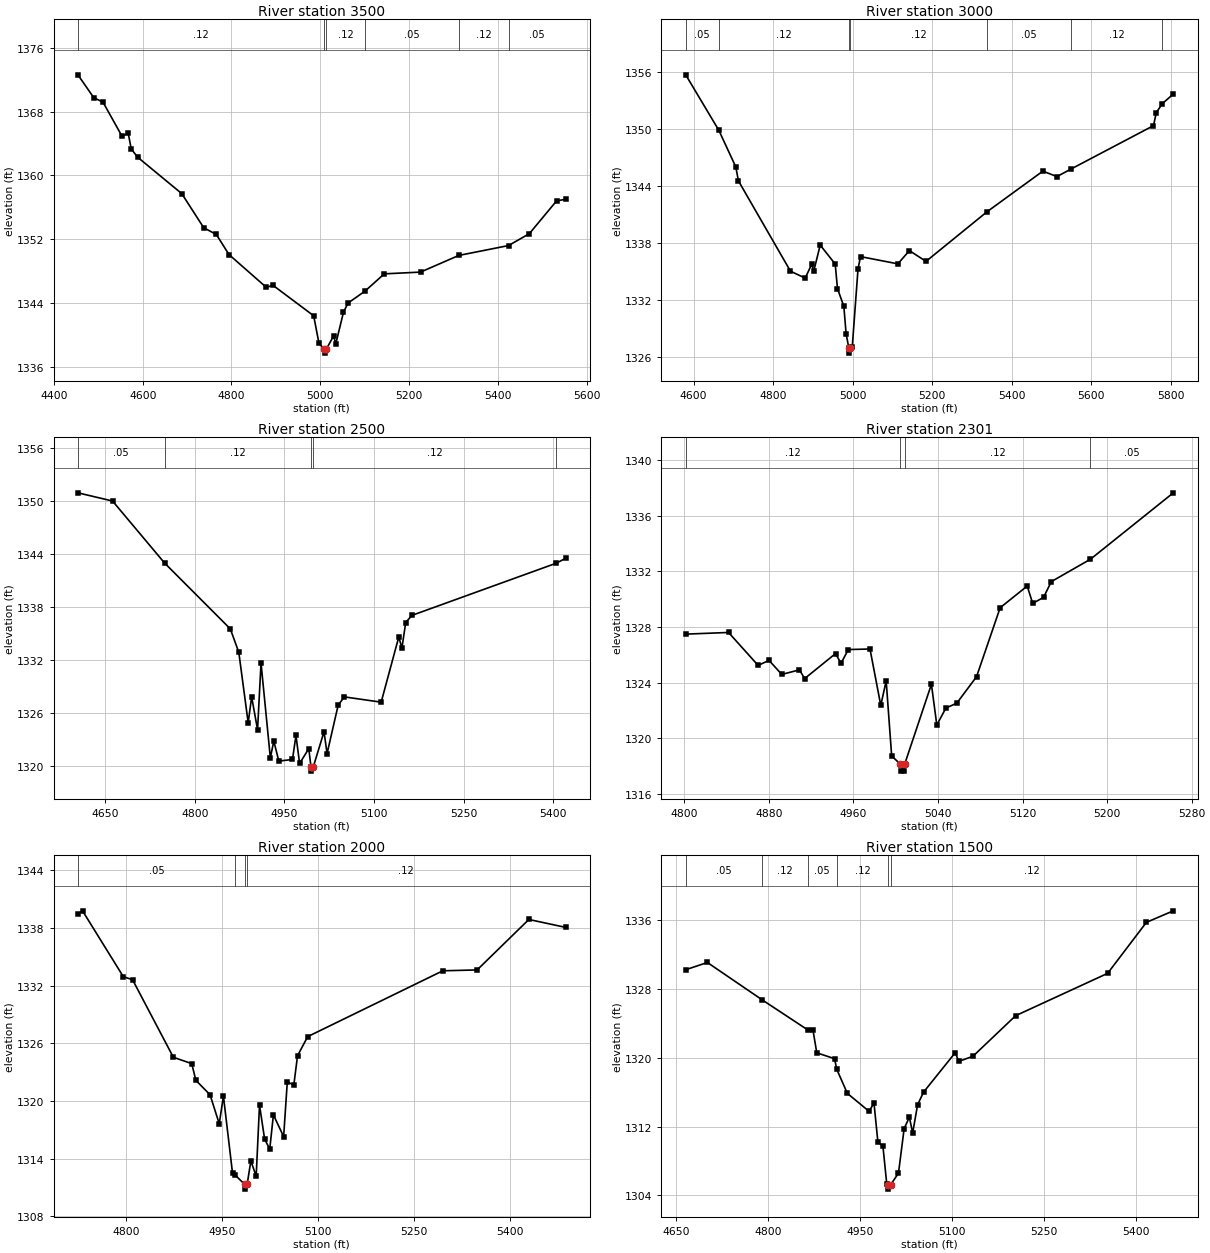
Type RM Length L Ch R = 1,3500,500,500,500
BEGIN DESCRIPTION:
SANFERNANDO091 7.0
END DESCRIPTION:
XS GIS Cut Line= 3
      2820105.68     10202803.11      2819694.00     10203161.77
      2819805.68     10203703.07
#Sta/Elev= 30
  4454.0 1372.61  4489.6 1369.75  4510.5 1369.18  4553.2 1364.92  4567.4 1365.26
  4574.1 1363.32  4588.3 1362.28  4688.0 1357.70  4737.4 1353.42  4765.9 1352.57
  4794.4 1350.05  4878.8 1345.92  4893.1 1346.21  4985.2 1342.37  4997.2 1338.90
  5009.6 1338.18  5009.8 1337.68  5013.6 1338.18  5030.0 1339.82  5035.1 1338.86
  5052.4 1342.82  5062.6 1343.96  5101.0 1345.47  5144.3 1347.63  5226.0 1347.85
  5312.1 1349.94  5424.2 1351.18  5471.1 1352.67  5532.7 1356.80  5552.7 1356.98
#Mann=6,-1,0
  4454.0    0.12       0  5009.6    0.07       0  5013.6    0.12       0
  5101.0    0.05       0  5312.1    0.12       0  5424.2    0.05       0
Bank Sta=5009.6,5013.6
Exp/Cntr=0.3,0.1

Type RM Length L Ch R = 1,3000,500,500,500
BEGIN DESCRIPTION:
SANFERNANDO091 6.0
END DESCRIPTION:
XS GIS Cut Line= 3
      2818905.67     10202803.11      2819272.03     10203007.67
      2819755.66     10203653.07
#Sta/Elev= 30
  4580.4 1355.66  4663.7 1349.83  4706.4 1345.98  4712.9 1344.52  4843.8 1335.03
  4880.9 1334.30  4896.9 1335.74  4902.6 1335.08  4918.6 1337.77  4956.3 1335.78
  4962.0 1333.20  4978.0 1331.34  4983.7 1328.46  4990.7 1326.92  4991.0 1326.42
  4994.7 1326.92  4999.2 1327.09  5013.7 1335.29  5020.0 1336.56  5113.8 1335.80
  5142.9 1337.19  5184.6 1336.06  5338.3 1341.28  5478.4 1345.54  5513.8 1344.97
  5549.6 1345.77  5756.6 1350.32  5763.8 1351.70  5779.0 1352.64  5806.5 1353.64
#Mann=7,-1,0
  4580.4    0.05       0  4663.7    0.12       0  4990.7    0.07       0
  4994.7    0.12       0  5338.3    0.05       0  5549.6    0.12       0
  5779.0    0.05       0
Bank Sta=4990.7,4994.7
Exp/Cntr=0.3,0.1

Type RM Length L Ch R = 1,2500,199,199,199
BEGIN DESCRIPTION:
SANFERNANDO091 5.0
END DESCRIPTION:
XS GIS Cut Line= 3
      2818755.71     10203103.12      2819096.87     10203303.79
      2819505.67     10203403.11
#Sta/Elev= 30
  4604.2 1350.95  4662.2 1350.02  4749.3 1342.99  4859.4 1335.52  4873.6 1332.86
  4889.3 1324.87  4895.1 1327.81  4905.0 1324.09  4910.8 1331.64  4926.4 1320.90
  4932.2 1322.80  4940.6 1320.53  4963.5 1320.71  4969.3 1323.44  4975.4 1320.26
  4990.8 1321.94  4994.4 1319.89  4994.7 1319.39  4998.4 1319.89  5016.3 1323.86
  5021.4 1321.38  5039.9 1326.85  5050.2 1327.81  5112.0 1327.21  5141.5 1334.61
  5146.7 1333.34  5153.1 1336.24  5163.4 1337.05  5404.4 1342.95  5420.7 1343.51
#Mann=5,-1,0
  4604.2    0.05       0  4749.3    0.12       0  4994.4    0.07       0
  4998.4    0.12       0  5404.4    0.05       0
Bank Sta=4994.4,4998.4
Exp/Cntr=0.3,0.1

Type RM Length L Ch R = 1,2301,301,301,301
BEGIN DESCRIPTION:
Mapping XS 378d01c7
END DESCRIPTION:
XS GIS Cut Line= 4
      2818955.17     10203409.60      2819059.32     10203461.67
      2819285.01     10203513.76      2819397.81     10203522.43
#Sta/Elev= 30
  4801.4 1327.49  4841.9 1327.61  4869.9 1325.24  4880.2 1325.60  4892.3 1324.59
  4909.0 1324.92  4913.9 1324.29  4943.1 1326.09  4948.3 1325.39  4955.2 1326.38
  4975.7 1326.42  4985.9 1322.36  4991.0 1324.13  4996.2 1318.72  5004.5 1318.13
  5004.7 1317.63  5008.2 1317.63  5008.5 1318.13  5033.8 1323.88  5038.9 1320.95
  5047.5 1322.17  5057.8 1322.52  5076.5 1324.43  5098.8 1329.39  5124.4 1330.95
  5129.6 1329.70  5139.9 1330.14  5147.2 1331.27  5184.2 1332.88  5262.6 1337.66
#Mann=4,-1,0
  4801.4    0.12       0  5004.5    0.07       0  5008.5    0.12       0
  5184.2    0.05       0
Bank Sta=5004.5,5008.5
Exp/Cntr=0.3,0.1

Type RM Length L Ch R = 1,2000,500,500,500
BEGIN DESCRIPTION:
SANFERNANDO091 4.0
END DESCRIPTION:
XS GIS Cut Line= 3
      2818755.68     10203403.11      2818931.61     10203615.24
      2819355.66     10203853.10
#Sta/Elev= 30
  4724.4 1339.47  4731.6 1339.80  4795.4 1332.94  4809.7 1332.64  4873.5 1324.56
  4902.2 1323.90  4908.7 1322.16  4930.8 1320.66  4945.2 1317.64  4951.7 1320.53
  4966.0 1312.47  4970.4 1312.28  4984.8 1311.34  4985.1 1310.84  4988.8 1311.34
  4994.6 1313.78  5002.9 1312.18  5008.1 1319.59  5016.1 1316.04  5024.1 1315.01
  5029.8 1318.57  5045.8 1316.31  5051.5 1322.00  5061.7 1321.67  5067.5 1324.72
  5083.4 1326.71  5294.5 1333.56  5348.1 1333.65  5428.9 1338.90  5486.2 1338.08
#Mann=4,-1,0
  4724.4    0.05       0  4970.4    0.12       0  4984.8    0.07       0
  4988.8    0.12       0
Bank Sta=4984.8,4988.8
Exp/Cntr=0.3,0.1

Type RM Length L Ch R = 1,1500,281,281,281
BEGIN DESCRIPTION:
SANFERNANDO091 3.0
END DESCRIPTION:
XS GIS Cut Line= 3
      2818630.68     10203778.10      2818835.94     10204041.71
      2819255.71     10203853.10
#Sta/Elev= 30
  4665.9 1330.21  4701.2 1331.05  4790.9 1326.69  4864.3 1323.24  4873.1 1323.24
  4879.4 1320.56  4908.4 1319.88  4911.8 1318.67  4929.2 1315.85  4964.5 1313.77
  4972.6 1314.72  4979.0 1310.17  4987.1 1309.76  4993.4 1305.32  4995.7 1305.23
  4996.0 1304.73  4999.7 1305.23  5012.5 1306.59  5021.7 1311.75  5030.2 1313.09
  5035.6 1311.25  5043.6 1314.52  5053.3 1315.99  5105.1 1320.59  5110.6 1319.56
  5133.8 1320.16  5203.3 1324.87  5353.2 1329.79  5416.3 1335.71  5460.2 1337.05
#Mann=6,-1,0
  4665.9    0.05       0  4790.9    0.12       0  4864.3    0.05       0
  4911.8    0.12       0  4995.7    0.07       0  4999.7    0.12       0
Bank Sta=4995.7,4999.7
Exp/Cntr=0.3,0.1

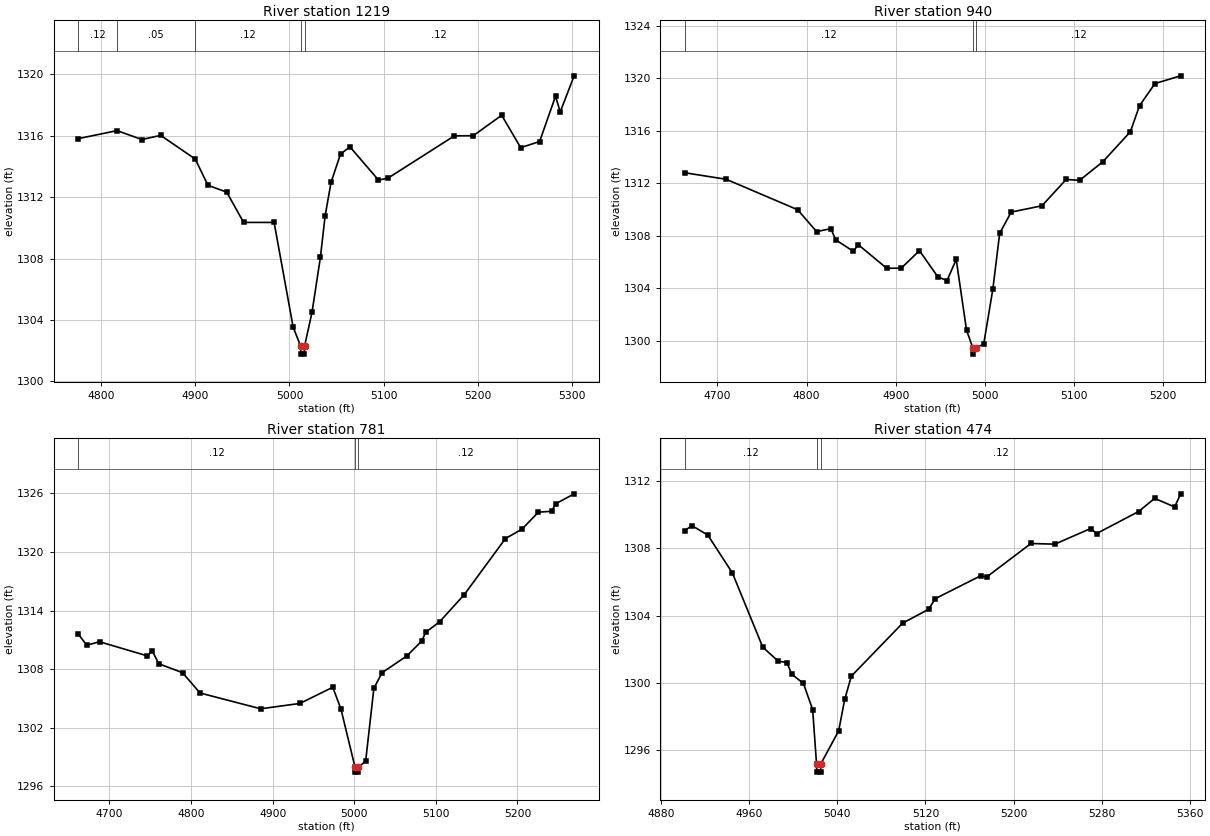
Type RM Length L Ch R = 1,1219,279,279,279
BEGIN DESCRIPTION:
Mapping XS d09a1b2a
END DESCRIPTION:
XS GIS Cut Line= 3
      2818628.42     10204332.17      2818797.65     10204319.15
      2819152.09     10204275.93
#Sta/Elev= 30
  4775.7 1315.82  4816.9 1316.34  4843.2 1315.76  4863.2 1316.03  4899.9 1314.49
  4913.4 1312.78  4933.4 1312.33  4951.3 1310.36  4983.7 1310.36  5003.9 1303.55
  5012.0 1302.28  5012.2 1301.78  5015.7 1301.78  5016.0 1302.28  5024.0 1304.51
  5032.9 1308.09  5037.9 1310.78  5044.2 1312.97  5054.3 1314.82  5064.3 1315.28
  5094.6 1313.12  5104.6 1313.24  5175.2 1316.00  5195.3 1316.01  5225.5 1317.34
  5245.7 1315.23  5265.8 1315.63  5282.7 1318.58  5287.7 1317.56  5302.5 1319.91
#Mann=5,-1,0
  4775.7    0.12       0  4816.9    0.05       0  4899.9    0.12       0
  5012.0    0.07       0  5016.0    0.12       0
Bank Sta=5012,5016
Exp/Cntr=0.3,0.1

Type RM Length L Ch R = 1,940,159,159,159
BEGIN DESCRIPTION:
Mapping XS bec9c96e
END DESCRIPTION:
XS GIS Cut Line= 3
      2818606.72     10204462.39      2818810.67     10204536.16
      2819140.56     10204614.29
#Sta/Elev= 30
  4663.5 1312.81  4710.0 1312.31  4790.0 1309.99  4811.3 1308.32  4827.3 1308.55
  4832.6 1307.70  4852.6 1306.81  4857.9 1307.33  4889.8 1305.53  4906.1 1305.53
  4926.6 1306.87  4947.2 1304.87  4957.5 1304.59  4967.8 1306.20  4979.4 1300.80
  4986.3 1299.48  4986.6 1298.98  4990.3 1299.48  4998.6 1299.74  5008.9 1303.95
  5016.5 1308.18  5029.4 1309.81  5063.9 1310.29  5091.1 1312.30  5106.1 1312.23
  5132.2 1313.65  5163.0 1315.93  5173.3 1317.92  5190.6 1319.61  5219.4 1320.20
#Mann=3,-1,0
  4663.5    0.12       0  4986.3    0.07       0  4990.3    0.12       0
Bank Sta=4986.3,4990.3
Exp/Cntr=0.3,0.1

Type RM Length L Ch R = 1,781,307,307,307
BEGIN DESCRIPTION:
Mapping XS 410689a1
END DESCRIPTION:
XS GIS Cut Line= 3
      2818580.65     10204553.53      2818810.67     10204688.07
      2819149.22     10204731.48
#Sta/Elev= 30
  4661.8 1311.58  4672.1 1310.45  4687.8 1310.80  4746.5 1309.35  4752.3 1309.90
  4760.3 1308.55  4789.5 1307.63  4811.0 1305.55  4885.3 1303.93  4933.5 1304.48
  4973.7 1306.14  4983.7 1303.91  5001.0 1297.94  5001.3 1297.44  5004.8 1297.44
  5005.0 1297.94  5014.0 1298.57  5024.1 1306.03  5034.1 1307.63  5064.4 1309.34
  5082.7 1310.87  5087.7 1311.78  5104.7 1312.85  5135.0 1315.64  5185.4 1321.38
  5205.5 1322.33  5225.7 1324.08  5242.0 1324.17  5247.0 1324.94  5269.6 1325.96
#Mann=3,-1,0
  4661.8    0.12       0  5001.0    0.07       0  5005.0    0.12       0
Bank Sta=5001,5005
Exp/Cntr=0.3,0.1

Type RM Length L Ch R = 1,474,0,0,0
BEGIN DESCRIPTION:
SANFERNANDO091 1.0
END DESCRIPTION:
XS GIS Cut Line= 3
      2818580.65     10204778.08      2818657.25     10204840.00
      2818980.70     10204978.12
#Sta/Elev= 30
  4901.5 1309.06  4908.0 1309.35  4922.4 1308.79  4944.7 1306.54  4972.3 1302.13
  4986.3 1301.30  4994.3 1301.22  4998.5 1300.53  5009.2 1299.98  5017.6 1298.42
  5021.1 1295.21  5021.3 1294.71  5024.8 1294.71  5025.1 1295.21  5041.2 1297.16
  5046.7 1299.03  5052.7 1300.41  5099.3 1303.56  5122.9 1304.38  5128.8 1305.01
  5170.1 1306.37  5175.6 1306.30  5215.8 1308.29  5237.5 1308.25  5270.0 1309.18
  5275.4 1308.88  5313.6 1310.19  5328.1 1310.97  5346.3 1310.46  5351.7 1311.24
#Mann=3,-1,0
  4901.5    0.12       0  5021.1    0.07       0  5025.1    0.12       0
Bank Sta=5021.1,5025.1
Exp/Cntr=0.3,0.1

Chan Stop Cuts=-1