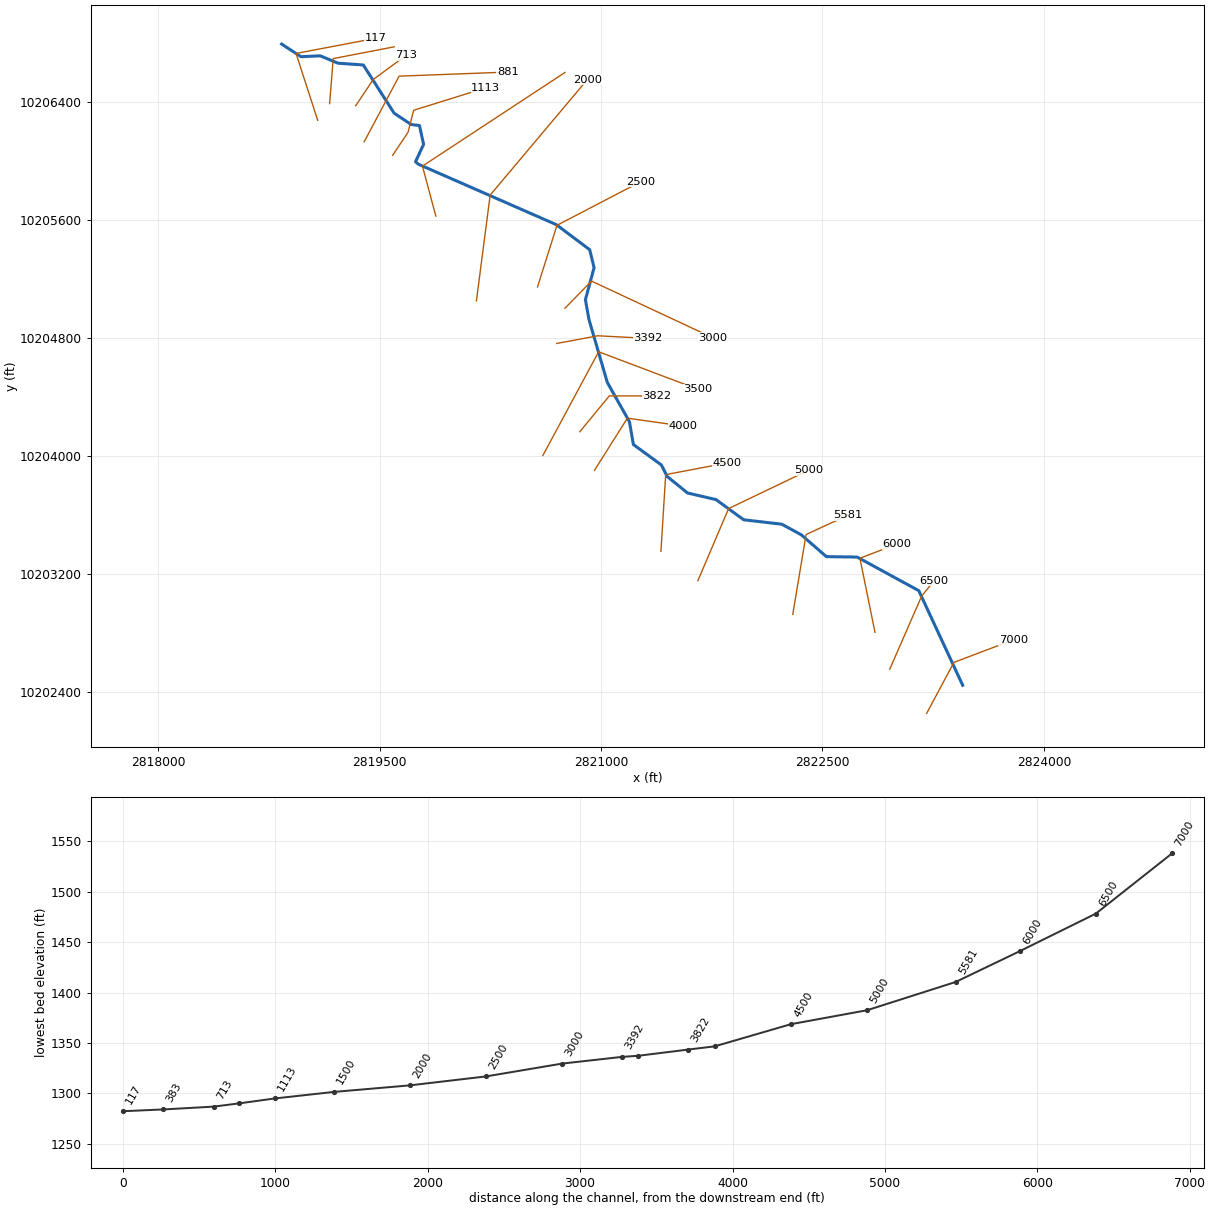
--- SANFERNANDO093.prj (project) ---

Proj Title=SANFERNANDO093 Base Level Engineering
Current Plan=p01
Default Exp/Contr=0.3,0.1
English Units
Geom File=g01
Flow File=f01
Plan File=p01
BEGIN DESCRIPTION:
SANFERNANDO093
END DESCRIPTION:

--- SANFERNANDO093.p01 (plan) ---

Plan Title=Multiple Run
Short Identifier=Multiple
Geom File=g01
Flow File=f01
Subcritical Flow
K Sum by GR= 0
Std Step Tol= 0.01
Critical Tol= 0.01
Num of Std Step Trials= 20
Max Error Tol= 0.3
Flow Tol Ratio= 0.001
Split Flow NTrial= 30
Split Flow Tol= 0.02
Split Flow Ratio= 0.02
Log Output Level= 0
Friction Slope Method= 1
Unsteady Friction Slope Method= 2
Unsteady Bridges Friction Slope Method= 1
Parabolic Critical Depth
Global Vel Dist=  1 , 1 , 1
Global Log Level= 0
CheckData=True
Encroach Param= -1, 0, 0, 0
BEGIN DESCRIPTION:
Multiple Run
END DESCRIPTION:

--- SANFERNANDO093.f01 (steady flow) ---

Flow Title=Multiple
Number of Profiles=7
Profile Names=10-year,25-year,50-year,1pct_min,100-year,1pct_plu,500-year
River Rch & RM= SANFERNANDO093,Reach-1,7000
     180     277     626     470     875    1631    1324
River Rch & RM= SANFERNANDO093,Reach-1,1113
     231     363     816     641    1148    2057    1728
Boundary for River Rch & Prof#=SANFERNANDO093,Reach-1,1
Up Type=0
Dn Type=3
Dn Slope=0.005
Boundary for River Rch & Prof#=SANFERNANDO093,Reach-1,2
Up Type=0
Dn Type=3
Dn Slope=0.005
Boundary for River Rch & Prof#=SANFERNANDO093,Reach-1,3
Up Type=0
Dn Type=3
Dn Slope=0.005
Boundary for River Rch & Prof#=SANFERNANDO093,Reach-1,4
Up Type=0
Dn Type=3
Dn Slope=0.005
Boundary for River Rch & Prof#=SANFERNANDO093,Reach-1,5
Up Type=0
Dn Type=3
Dn Slope=0.005
Boundary for River Rch & Prof#=SANFERNANDO093,Reach-1,6
Up Type=0
Dn Type=3
Dn Slope=0.005
Boundary for River Rch & Prof#=SANFERNANDO093,Reach-1,7
Up Type=0
Dn Type=3
Dn Slope=0.005

--- SANFERNANDO093.g01 (geometry) ---

Geom Title=Existing Conditions

River Reach=SANFERNANDO093,Reach-1
Reach XY= 30
      2823449.75     10202444.00      2823152.25     10203086.00
      2822734.75     10203314.00      2822526.50     10203317.00
      2822356.25     10203465.00      2822225.00     10203537.00
      2821966.50     10203567.00      2821778.50     10203704.00
      2821585.75     10203749.00      2821448.00     10203861.00
      2821408.75     10203939.00      2821218.75     10204078.00
      2821192.50     10204232.00      2821042.50     10204499.00
      2820918.00     10204926.00      2820894.00     10205061.00
      2820952.75     10205278.00      2820923.00     10205400.00
      2820697.25     10205570.00      2819763.25     10205980.00
      2819743.00     10205997.00      2819797.75     10206115.00
      2819770.00     10206243.00      2819713.50     10206250.00
      2819598.00     10206327.00      2819389.25     10206654.00
      2819218.00     10206666.00      2819097.75     10206716.00
      2818967.50     10206710.00      2818836.00     10206796.00

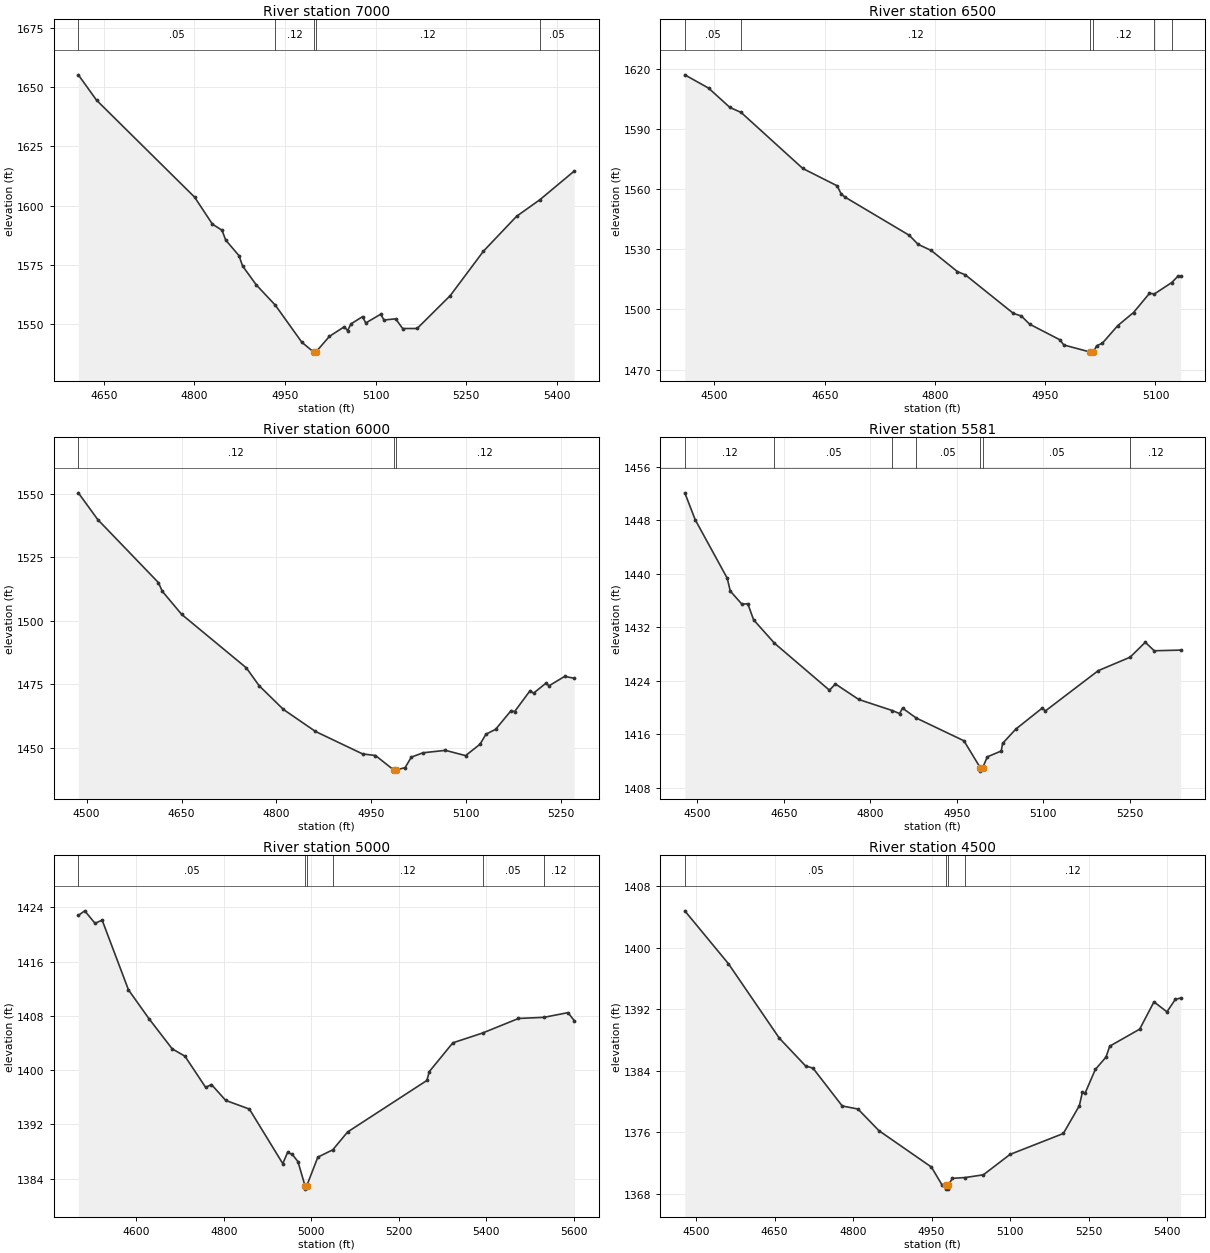
Type RM Length L Ch R = 1,7000,500,500,500
BEGIN DESCRIPTION:
SANFERNANDO093 13.0
END DESCRIPTION:
XS GIS Cut Line= 3
      2823205.71     10202253.15      2823390.18     10202599.15
      2823791.13     10202751.45
#Sta/Elev= 30
  4607.9 1655.20  4638.0 1644.53  4800.5 1603.64  4829.9 1592.28  4845.8 1589.72
  4851.9 1585.57  4873.9 1579.01  4879.8 1574.69  4902.5 1566.70  4934.2 1558.09
  4978.0 1542.50  4997.4 1538.42  4997.7 1537.92  5001.4 1538.42  5023.6 1544.98
  5048.4 1549.05  5053.7 1547.38  5059.4 1550.26  5078.5 1553.29  5083.8 1550.63
  5108.6 1554.32  5114.0 1551.88  5133.4 1552.37  5144.9 1548.29  5168.9 1548.30
  5223.8 1562.18  5278.7 1580.88  5333.6 1595.59  5371.9 1602.52  5428.9 1614.62
#Mann=5,-1,0
  4607.9    0.05       0  4934.2    0.12       0  4997.4    0.07       0
  5001.4    0.12       0  5371.9    0.05       0
Bank Sta=4997.4,5001.4
Exp/Cntr=0.3,0.1

Type RM Length L Ch R = 1,6500,500,500,500
BEGIN DESCRIPTION:
SANFERNANDO093 12.0
END DESCRIPTION:
XS GIS Cut Line= 3
      2822955.68     10202553.10      2823171.53     10203048.52
      2823255.66     10203153.08
#Sta/Elev= 30
  4459.6 1616.93  4492.0 1610.30  4520.9 1600.69  4536.2 1598.19  4620.1 1570.27
  4666.9 1561.61  4672.4 1557.51  4677.8 1555.94  4765.0 1536.95  4777.0 1532.45
  4794.9 1529.38  4830.5 1518.87  4841.4 1517.21  4906.8 1497.99  4917.5 1496.73
  4928.7 1492.67  4969.8 1484.89  4975.3 1482.29  5011.5 1478.72  5011.7 1478.22
  5015.5 1478.72  5019.9 1481.88  5027.8 1483.20  5048.7 1491.95  5070.1 1498.45
  5091.8 1508.01  5098.6 1507.74  5122.2 1513.42  5131.0 1516.73  5134.2 1516.73
#Mann=6,-1,0
  4459.6    0.05       0  4536.2    0.12       0  5011.5    0.07       0
  5015.5    0.12       0  5098.6    0.05       0  5122.2    0.12       0
Bank Sta=5011.5,5015.5
Exp/Cntr=0.3,0.1

Type RM Length L Ch R = 1,6000,419,419,419
BEGIN DESCRIPTION:
SANFERNANDO093 11.0
END DESCRIPTION:
XS GIS Cut Line= 3
      2822855.68     10202803.14      2822753.56     10203305.88
      2823005.66     10203403.10
#Sta/Elev= 30
  4487.0 1550.34  4517.6 1539.85  4613.5 1515.04  4619.6 1511.64  4650.2 1502.55
  4752.3 1481.54  4772.7 1474.47  4810.9 1465.17  4861.6 1456.51  4936.0 1447.68
  4956.4 1447.05  4985.0 1441.41  4985.2 1440.91  4989.0 1441.41  5003.1 1442.27
  5013.0 1446.41  5031.5 1448.13  5066.9 1449.08  5098.7 1447.01  5121.5 1451.49
  5130.9 1455.43  5146.1 1457.35  5170.7 1464.74  5176.0 1464.28  5200.7 1472.58
  5206.0 1471.55  5225.3 1475.42  5230.6 1474.48  5255.2 1478.16  5270.2 1477.43
#Mann=3,-1,0
  4487.0    0.12       0  4985.0    0.07       0  4989.0    0.12       0
Bank Sta=4985,4989
Exp/Cntr=0.3,0.1

Type RM Length L Ch R = 1,5581,581,581,581
BEGIN DESCRIPTION:
Mapping XS eb0667bf
END DESCRIPTION:
XS GIS Cut Line= 3
      2822298.61     10202925.30      2822388.88     10203466.93
      2822671.33     10203597.81
#Sta/Elev= 30
  4478.3 1452.14  4496.4 1448.11  4551.9 1439.37  4557.2 1437.45  4577.5 1435.47
  4587.6 1435.55  4597.7 1433.14  4633.9 1429.64  4729.3 1422.61  4739.7 1423.54
  4780.2 1421.22  4838.6 1419.56  4851.0 1419.11  4856.1 1419.93  4879.6 1418.46
  4962.7 1415.04  4991.1 1411.00  4991.4 1410.50  4995.1 1411.00  5003.3 1412.64
  5027.4 1413.51  5029.8 1414.65  5052.7 1416.79  5098.5 1419.93  5104.1 1419.51
  5195.7 1425.53  5251.1 1427.55  5277.4 1429.78  5292.9 1428.51  5338.7 1428.61
#Mann=7,-1,0
  4478.3    0.12       0  4633.9    0.05       0  4838.6    0.12       0
  4879.6    0.05       0  4991.1    0.05       0  4995.1    0.05       0
  5251.1    0.12       0
Bank Sta=4991.1,4995.1
Exp/Cntr=0.3,0.1

Type RM Length L Ch R = 1,5000,500,500,500
BEGIN DESCRIPTION:
SANFERNANDO093 9.0
END DESCRIPTION:
XS GIS Cut Line= 3
      2821655.67     10203153.09      2821863.94     10203643.06
      2822405.66     10203903.10
#Sta/Elev= 30
  4467.6 1422.82  4482.2 1423.50  4505.8 1421.66  4522.0 1422.13  4582.2 1411.85
  4629.5 1407.56  4682.2 1403.15  4711.3 1402.07  4758.6 1397.47  4771.9 1397.89
  4804.5 1395.55  4858.6 1394.27  4934.9 1386.23  4945.9 1387.89  4956.6 1387.59
  4969.5 1386.54  4985.7 1382.97  4986.0 1382.47  4989.7 1382.97  5015.1 1387.19
  5049.2 1388.27  5083.1 1390.90  5264.2 1398.49  5269.8 1399.80  5323.6 1404.04
  5391.4 1405.48  5473.6 1407.63  5532.0 1407.80  5586.8 1408.49  5600.9 1407.33
#Mann=6,-1,0
  4467.6    0.05       0  4985.7    0.05       0  4989.7    0.05       0
  5049.2    0.12       0  5391.4    0.05       0  5532.0    0.12       0
Bank Sta=4985.7,4989.7
Exp/Cntr=0.3,0.1

Type RM Length L Ch R = 1,4500,500,500,500
BEGIN DESCRIPTION:
SANFERNANDO093 8.0
END DESCRIPTION:
XS GIS Cut Line= 3
      2821405.68     10203353.08      2821437.72     10203873.39
      2821855.69     10203953.11
#Sta/Elev= 30
  4478.7 1404.80  4562.0 1397.93  4659.1 1388.26  4709.2 1384.65  4723.5 1384.35
  4779.3 1379.44  4809.4 1379.04  4849.4 1376.23  4949.6 1371.50  4969.7 1369.20
  4977.7 1369.13  4977.9 1368.63  4981.4 1368.63  4981.7 1369.13  4989.7 1370.03
  5014.5 1370.14  5048.8 1370.49  5099.7 1373.14  5201.5 1375.86  5232.1 1379.47
  5237.9 1381.22  5243.0 1381.09  5262.6 1384.18  5283.0 1385.79  5290.1 1387.21
  5347.3 1389.42  5374.6 1392.97  5399.4 1391.67  5415.3 1393.29  5425.5 1393.47
#Mann=4,-1,0
  4478.7    0.05       0  4977.7    0.03       0  4981.7    0.05       0
  5014.5    0.12       0
Bank Sta=4977.7,4981.7
Exp/Cntr=0.3,0.1

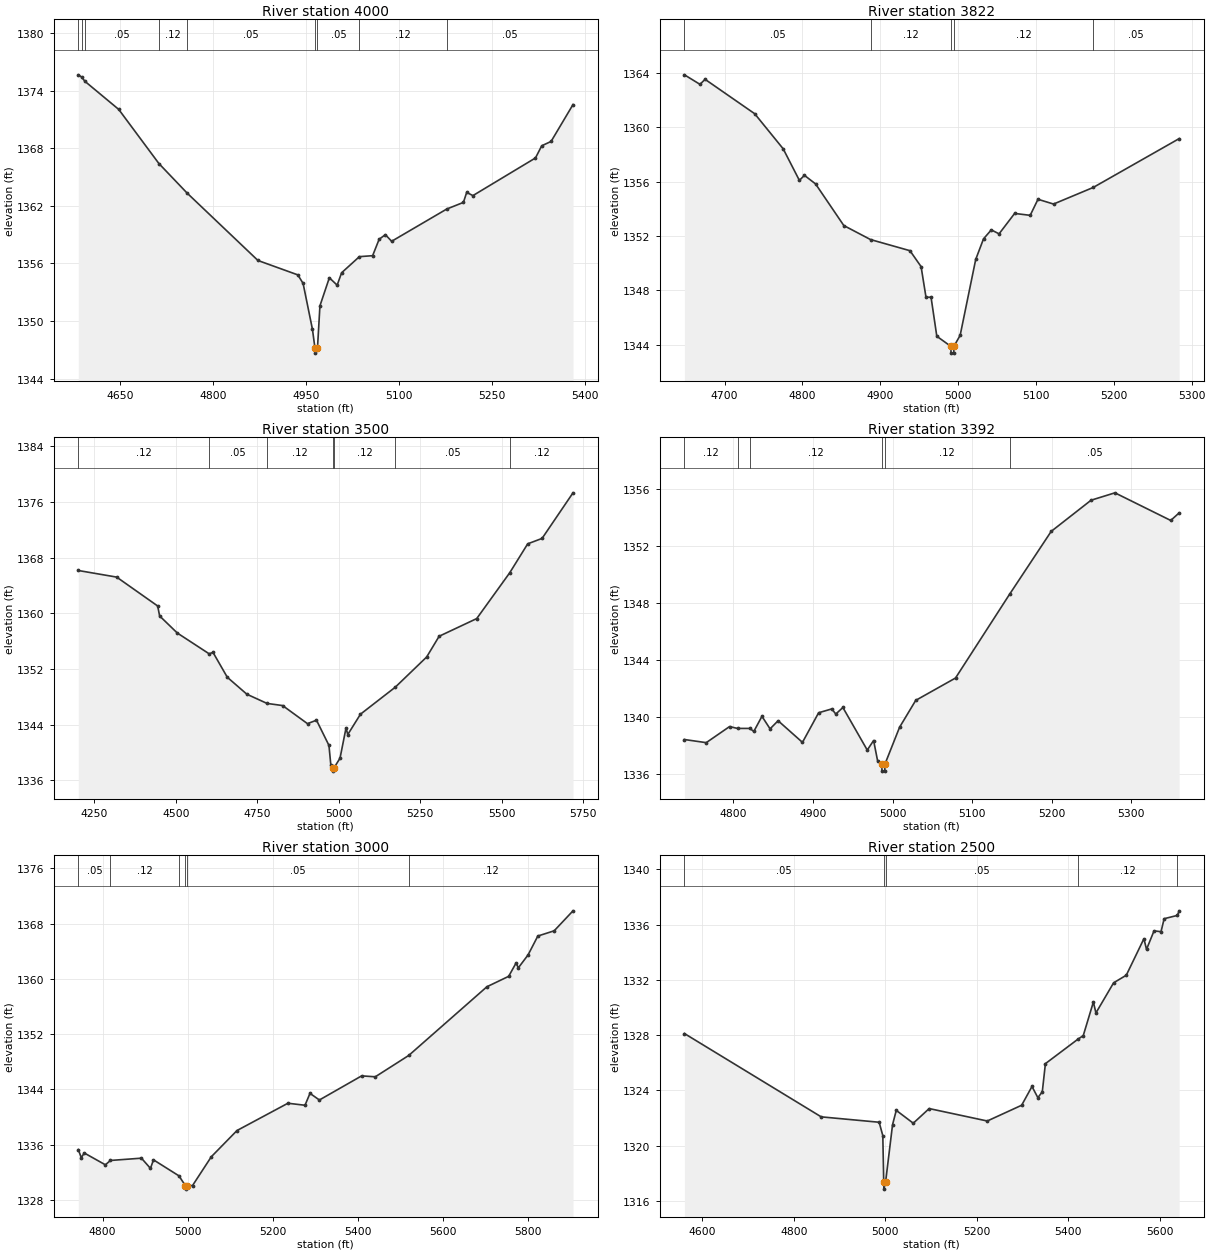
Type RM Length L Ch R = 1,4000,178,178,178
BEGIN DESCRIPTION:
SANFERNANDO093 7.0
END DESCRIPTION:
XS GIS Cut Line= 3
      2820955.68     10203903.11      2821178.57     10204256.84
      2821555.66     10204203.11
#Sta/Elev= 30
  4581.9 1375.64  4587.3 1375.41  4592.7 1374.96  4647.2 1372.04  4712.1 1366.40
  4757.7 1363.32  4872.1 1356.30  4936.5 1354.80  4945.0 1353.91  4960.1 1349.13
  4964.2 1347.15  4964.5 1346.65  4968.2 1347.15  4972.2 1351.58  4987.4 1354.50
  5000.0 1353.73  5007.2 1355.02  5035.9 1356.70  5057.3 1356.80  5067.8 1358.51
  5077.9 1358.99  5088.0 1358.30  5177.0 1361.66  5203.9 1362.35  5209.2 1363.39
  5219.3 1363.06  5320.3 1366.98  5330.4 1368.25  5345.5 1368.70  5380.9 1372.54
#Mann=9,-1,0
  4581.9    0.05       0  4587.3    0.12       0  4592.7    0.05       0
  4712.1    0.12       0  4757.7    0.05       0  4964.2    0.03       0
  4968.2    0.05       0  5035.9    0.12       0  5177.0    0.05       0
Bank Sta=4964.2,4968.2
Exp/Cntr=0.3,0.1

Type RM Length L Ch R = 1,3822,322,322,322
BEGIN DESCRIPTION:
Mapping XS 256238df
END DESCRIPTION:
XS GIS Cut Line= 3
      2820856.22     10204164.83      2821055.84     10204407.85
      2821377.05     10204407.85
#Sta/Elev= 30
  4648.3 1363.85  4668.3 1363.15  4674.8 1363.52  4738.6 1360.99  4775.2 1358.41
  4796.0 1356.09  4802.5 1356.46  4816.8 1355.83  4853.1 1352.77  4887.4 1351.74
  4938.1 1350.92  4952.4 1349.75  4958.7 1347.50  4965.2 1347.50  4972.6 1344.63
  4990.6 1343.89  4990.9 1343.39  4994.4 1343.39  4994.6 1343.89  5002.6 1344.70
  5022.6 1350.28  5032.6 1351.79  5042.6 1352.45  5052.6 1352.16  5072.6 1353.66
  5092.6 1353.52  5102.6 1354.70  5122.6 1354.35  5173.6 1355.57  5284.0 1359.16
#Mann=5,-1,0
  4648.3    0.05       0  4887.4    0.12       0  4990.6    0.07       0
  4994.6    0.12       0  5173.6    0.05       0
Bank Sta=4990.6,4994.6
Exp/Cntr=0.3,0.1

Type RM Length L Ch R = 1,3500,108,108,108
BEGIN DESCRIPTION:
SANFERNANDO093 6.0
END DESCRIPTION:
XS GIS Cut Line= 3
      2820605.68     10204003.11      2820983.44     10204707.40
      2821655.65     10204453.12
#Sta/Elev= 30
  4200.8 1366.17  4318.6 1365.22  4444.4 1361.07  4450.4 1359.64  4504.5 1357.19
  4602.3 1354.20  4614.2 1354.40  4658.0 1350.83  4718.1 1348.39  4779.9 1347.07
  4827.8 1346.76  4904.1 1344.16  4931.7 1344.66  4969.9 1341.04  4975.6 1338.25
  4981.8 1337.84  4982.0 1337.34  4985.8 1337.84  5003.9 1339.20  5022.3 1343.54
  5027.7 1342.60  5066.6 1345.52  5173.4 1349.40  5269.7 1353.74  5308.0 1356.72
  5423.3 1359.26  5524.7 1365.85  5579.7 1370.00  5623.8 1370.78  5718.7 1377.33
#Mann=7,-1,0
  4200.8    0.12       0  4602.3    0.05       0  4779.9    0.12       0
  4981.8    0.07       0  4985.8    0.12       0  5173.4    0.05       0
  5524.7    0.12       0
Bank Sta=4981.8,4985.8
Exp/Cntr=0.3,0.1

Type RM Length L Ch R = 1,3392,392,392,392
BEGIN DESCRIPTION:
Mapping XS 2a54e748
END DESCRIPTION:
XS GIS Cut Line= 3
      2820699.97     10204763.76      2820977.72     10204815.84
      2821316.28     10204798.48
#Sta/Elev= 30
  4738.4 1338.43  4765.8 1338.21  4795.1 1339.34  4805.1 1339.21  4820.5 1339.21
  4825.6 1339.00  4835.8 1340.06  4846.0 1339.18  4856.1 1339.75  4886.7 1338.23
  4907.0 1340.31  4923.5 1340.58  4928.6 1340.22  4937.5 1340.68  4968.1 1337.69
  4976.1 1338.36  4981.2 1336.91  4986.4 1336.71  4986.6 1336.21  4990.1 1336.21
  4990.4 1336.71  5008.7 1339.29  5029.0 1341.18  5079.0 1342.75  5147.0 1348.64
  5199.2 1353.05  5249.3 1355.24  5279.3 1355.76  5349.4 1353.82  5360.0 1354.35
#Mann=6,-1,0
  4738.4    0.12       0  4805.1    0.05       0  4820.5    0.12       0
  4986.4    0.07       0  4990.4    0.12       0  5147.0    0.05       0
Bank Sta=4986.4,4990.4
Exp/Cntr=0.3,0.1

Type RM Length L Ch R = 1,3000,500,500,500
BEGIN DESCRIPTION:
SANFERNANDO093 5.0
END DESCRIPTION:
XS GIS Cut Line= 3
      2820755.67     10205003.10      2820935.23     10205187.11
      2821755.72     10204803.10
#Sta/Elev= 30
  4742.9 1335.30  4750.0 1334.14  4757.0 1334.81  4806.6 1333.10  4818.5 1333.73
  4891.4 1334.06  4912.6 1332.58  4919.7 1333.82  4979.6 1331.50  4994.7 1330.08
  4995.0 1329.58  4998.7 1330.08  5011.5 1330.10  5055.7 1334.27  5116.0 1338.06
  5235.7 1342.01  5275.9 1341.72  5287.6 1343.44  5309.7 1342.48  5409.0 1345.97
  5441.2 1345.84  5519.8 1348.93  5703.5 1358.87  5754.7 1360.38  5772.0 1362.30
  5777.5 1361.62  5800.3 1363.48  5823.2 1366.21  5861.7 1366.97  5905.9 1369.86
#Mann=6,-1,0
  4742.9    0.05       0  4818.5    0.12       0  4979.6    0.05       0
  4994.7    0.05       0  4998.7    0.05       0  5519.8    0.12       0
Bank Sta=4994.7,4998.7
Exp/Cntr=0.3,0.1

Type RM Length L Ch R = 1,2500,500,500,500
BEGIN DESCRIPTION:
SANFERNANDO093 4.0
END DESCRIPTION:
XS GIS Cut Line= 3
      2820569.43     10205147.46      2820701.46     10205565.82
      2821270.79     10205862.74
#Sta/Elev= 30
  4561.3 1328.11  4860.1 1322.08  4986.7 1321.69  4994.7 1320.72  4996.7 1317.35
  4997.0 1316.85  5000.7 1317.35  5016.0 1321.52  5024.1 1322.55  5061.2 1321.62
  5096.0 1322.68  5222.9 1321.78  5298.0 1322.92  5320.6 1324.28  5333.4 1323.47
  5343.1 1323.89  5349.9 1325.93  5420.5 1327.69  5432.6 1327.96  5454.7 1330.39
  5460.3 1329.60  5498.9 1331.78  5526.6 1332.33  5565.1 1334.97  5570.8 1334.20
  5587.2 1335.54  5602.5 1335.48  5609.3 1336.42  5638.3 1336.66  5642.1 1336.99
#Mann=5,-1,0
  4561.3    0.05       0  4996.7    0.05       0  5000.7    0.05       0
  5420.5    0.12       0  5638.3    0.05       0
Bank Sta=4996.7,5000.7
Exp/Cntr=0.3,0.1

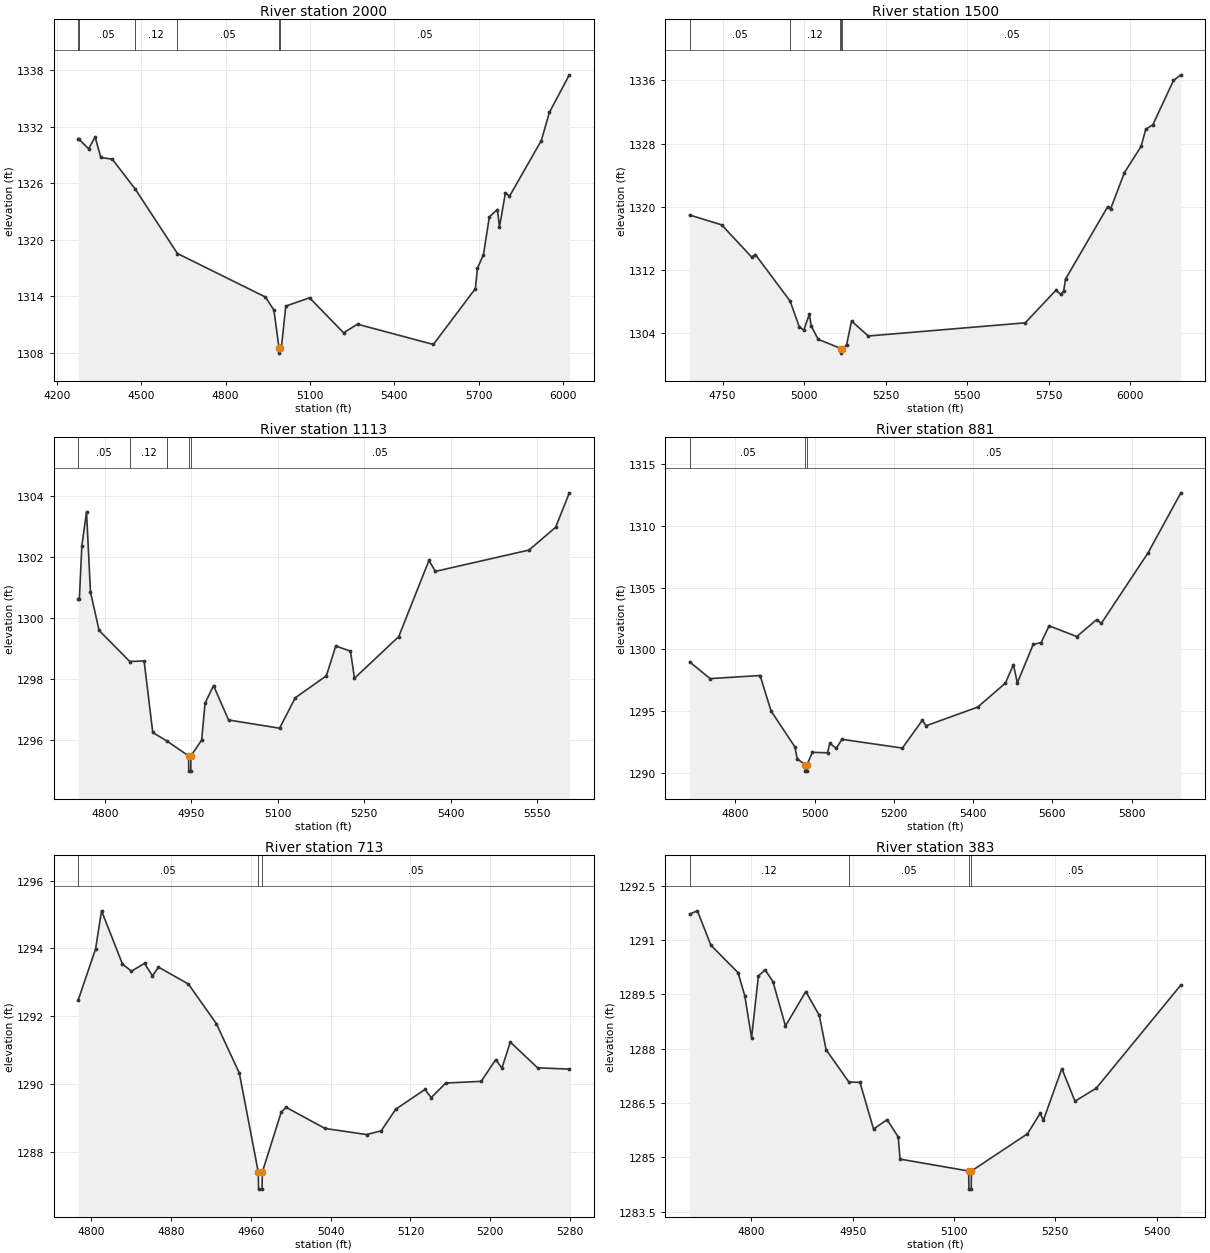
Type RM Length L Ch R = 1,2000,500,500,500
BEGIN DESCRIPTION:
SANFERNANDO093 3.0
END DESCRIPTION:
XS GIS Cut Line= 3
      2820155.68     10205053.08      2820248.77     10205770.76
      2820905.70     10206553.13
#Sta/Elev= 30
  4276.3 1330.71  4280.2 1330.64  4313.4 1329.66  4336.8 1330.90  4357.0 1328.73
  4397.7 1328.55  4479.5 1325.37  4629.2 1318.54  4942.0 1313.92  4972.1 1312.53
  4990.3 1308.47  4990.5 1307.97  4994.3 1308.47  4998.7 1308.58  5014.1 1312.96
  5098.6 1313.84  5219.6 1310.13  5269.0 1311.04  5538.4 1308.89  5687.9 1314.82
  5695.1 1316.98  5716.5 1318.41  5737.4 1322.43  5766.0 1323.21  5773.5 1321.37
  5794.6 1325.00  5808.9 1324.61  5922.1 1330.53  5950.7 1333.51  6021.6 1337.50
#Mann=6,-1,0
  4276.3    0.12       0  4280.2    0.05       0  4479.5    0.12       0
  4629.2    0.05       0  4990.3    0.03       0  4994.3    0.05       0
Bank Sta=4990.3,4994.3
Exp/Cntr=0.3,0.1

Type RM Length L Ch R = 1,1500,387,387,387
BEGIN DESCRIPTION:
SANFERNANDO093 2.0
END DESCRIPTION:
XS GIS Cut Line= 3
      2819880.69     10205628.11      2819790.10     10205967.42
      2820755.65     10206603.09
#Sta/Elev= 30
  4648.8 1318.95  4747.1 1317.70  4838.9 1313.63  4850.6 1313.94  4957.2 1308.04
  4985.2 1304.78  4998.9 1304.36  5016.1 1306.37  5022.0 1304.90  5043.1 1303.20
  5109.9 1302.09  5113.4 1301.95  5113.6 1301.45  5117.4 1301.95  5130.5 1302.52
  5145.6 1305.52  5196.8 1303.62  5678.6 1305.29  5772.9 1309.43  5787.1 1308.90
  5796.2 1309.28  5802.1 1310.83  5931.6 1320.01  5940.5 1319.72  5982.9 1324.33
  6034.1 1327.65  6048.3 1329.82  6070.2 1330.39  6133.4 1336.00  6156.0 1336.71
#Mann=5,-1,0
  4648.8    0.05       0  4957.2    0.12       0  5109.9    0.05       0
  5113.4    0.07       0  5117.4    0.05       0
Bank Sta=5113.4,5117.4
Exp/Cntr=0.3,0.1

Type RM Length L Ch R = 1,1113,232,232,232
BEGIN DESCRIPTION:
Mapping XS cffc9f55
END DESCRIPTION:
XS GIS Cut Line= 4
      2819588.27     10206040.99      2819692.42     10206197.21
      2819730.61     10206346.51      2820218.35     10206498.71
#Sta/Elev= 30
  4753.3 1300.63  4755.5 1300.63  4759.8 1302.37  4767.9 1303.48  4774.8 1300.85
  4789.8 1299.59  4843.0 1298.57  4867.9 1298.59  4882.9 1296.24  4908.3 1295.95
  4945.1 1295.47  4945.4 1294.97  4948.9 1294.97  4949.1 1295.47  4967.8 1295.99
  4973.7 1297.20  4988.4 1297.78  5014.5 1296.65  5103.1 1296.38  5130.4 1297.38
  5184.3 1298.10  5200.6 1299.08  5226.2 1298.91  5233.1 1298.02  5310.0 1299.39
  5362.4 1301.89  5373.6 1301.53  5536.1 1302.23  5582.4 1302.98  5606.1 1304.11
#Mann=5,-1,0
  4753.3    0.05       0  4843.0    0.12       0  4908.3    0.05       0
  4945.1    0.03       0  4949.1    0.05       0
Bank Sta=4945.1,4949.1
Exp/Cntr=0.3,0.1

Type RM Length L Ch R = 1,881,168,168,168
BEGIN DESCRIPTION:
Mapping XS 723ed503
END DESCRIPTION:
XS GIS Cut Line= 3
      2819395.85     10206133.63      2819631.94     10206578.04
      2820368.09     10206605.82
#Sta/Elev= 30
  4684.6 1298.99  4736.3 1297.63  4862.5 1297.88  4890.1 1295.01  4950.4 1292.09
  4956.1 1291.13  4976.4 1290.63  4976.7 1290.13  4980.2 1290.13  4980.4 1290.63
  4994.4 1291.65  5032.7 1291.62  5038.3 1292.39  5054.6 1291.97  5069.0 1292.71
  5221.6 1292.00  5271.6 1294.24  5281.6 1293.81  5411.7 1295.32  5481.8 1297.27
  5501.8 1298.77  5511.8 1297.29  5551.8 1300.40  5571.8 1300.55  5591.9 1301.91
  5661.9 1301.04  5711.9 1302.41  5723.6 1302.10  5842.0 1307.84  5924.5 1312.69
#Mann=3,-1,0
  4684.6    0.05       0  4976.4    0.03       0  4980.4    0.05       0
Bank Sta=4976.4,4980.4
Exp/Cntr=0.3,0.1

Type RM Length L Ch R = 1,713,330,330,330
BEGIN DESCRIPTION:
Mapping XS 5c0c8493
END DESCRIPTION:
XS GIS Cut Line= 3
      2819338.23     10206377.72      2819456.31     10206554.84
      2819681.33     10206721.01
#Sta/Elev= 30
  4786.7 1292.47  4804.2 1293.98  4810.2 1295.11  4831.2 1293.54  4840.2 1293.33
  4853.3 1293.56  4861.3 1293.19  4867.3 1293.45  4897.3 1292.95  4925.4 1291.78
  4948.4 1290.32  4967.4 1287.40  4967.7 1286.90  4971.2 1286.90  4971.4 1287.40
  4990.5 1289.18  4995.5 1289.31  5034.3 1288.69  5076.0 1288.51  5090.6 1288.62
  5105.3 1289.26  5134.5 1289.84  5140.8 1289.60  5155.4 1290.03  5190.9 1290.08
  5205.5 1290.72  5211.7 1290.47  5220.1 1291.24  5247.4 1290.48  5279.3 1290.44
#Mann=3,-1,0
  4786.7    0.05       0  4967.4    0.03       0  4971.4    0.05       0
Bank Sta=4967.4,4971.4
Exp/Cntr=0.3,0.1

Type RM Length L Ch R = 1,383,266,266,266
BEGIN DESCRIPTION:
Mapping XS 70d5e092
END DESCRIPTION:
XS GIS Cut Line= 3
      2819161.17     10206391.68      2819185.47     10206697.21
      2819598.63     10206777.06
#Sta/Elev= 30
  4708.5 1291.72  4720.0 1291.81  4740.0 1290.86  4780.2 1290.10  4790.2 1289.46
  4800.2 1288.30  4810.3 1290.01  4820.3 1290.18  4831.9 1289.85  4850.4 1288.63
  4880.5 1289.58  4900.5 1288.92  4910.6 1287.97  4944.3 1287.08  4960.7 1287.07
  4980.8 1285.78  5000.9 1286.04  5017.4 1285.56  5020.0 1284.95  5121.7 1284.62
  5121.9 1284.12  5125.4 1284.12  5125.7 1284.62  5208.7 1285.65  5227.3 1286.21
  5232.4 1286.03  5259.6 1287.45  5279.1 1286.55  5310.6 1286.91  5435.8 1289.76
#Mann=4,-1,0
  4708.5    0.12       0  4944.3    0.05       0  5121.7    0.03       0
  5125.7    0.05       0
Bank Sta=5121.7,5125.7
Exp/Cntr=0.3,0.1

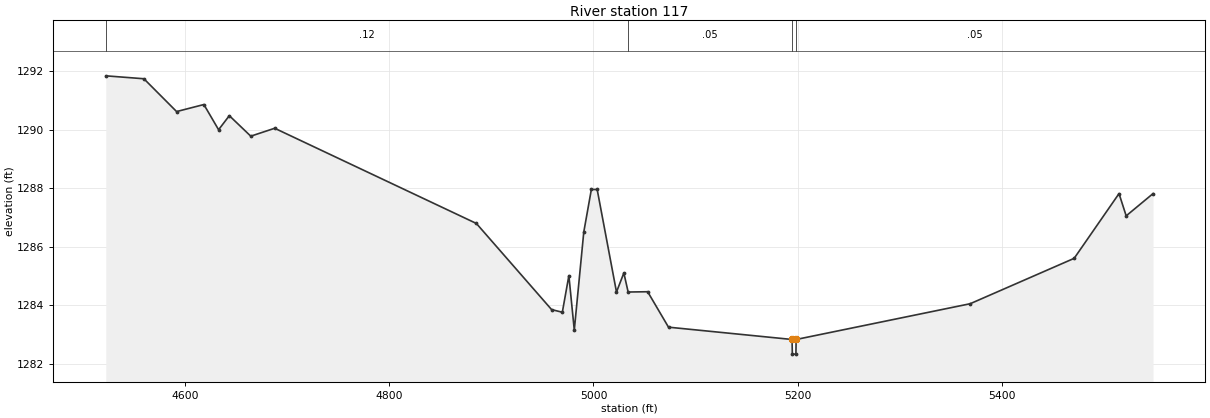
Type RM Length L Ch R = 1,117,0,0,0
BEGIN DESCRIPTION:
SANFERNANDO093 1.0
END DESCRIPTION:
XS GIS Cut Line= 3
      2819080.69     10206278.08      2818933.62     10206732.16
      2819471.53     10206834.71
#Sta/Elev= 30
  4522.7 1291.84  4560.0 1291.74  4592.0 1290.62  4618.7 1290.86  4633.1 1290.00
  4643.6 1290.48  4664.6 1289.78  4688.0 1290.05  4885.4 1286.80  4959.0 1283.86
  4969.5 1283.77  4975.9 1285.02  4981.2 1283.16  4990.5 1286.51  4997.9 1287.96
  5003.6 1287.96  5022.5 1284.46  5029.7 1285.11  5033.9 1284.46  5053.0 1284.47
  5073.4 1283.26  5194.3 1282.84  5194.6 1282.34  5198.1 1282.34  5198.3 1282.84
  5368.6 1284.06  5470.4 1285.61  5514.3 1287.82  5521.3 1287.06  5547.6 1287.82
#Mann=4,-1,0
  4522.7    0.12       0  5033.9    0.05       0  5194.3    0.07       0
  5198.3    0.05       0
Bank Sta=5194.3,5198.3
Exp/Cntr=0.3,0.1

Chan Stop Cuts=-1