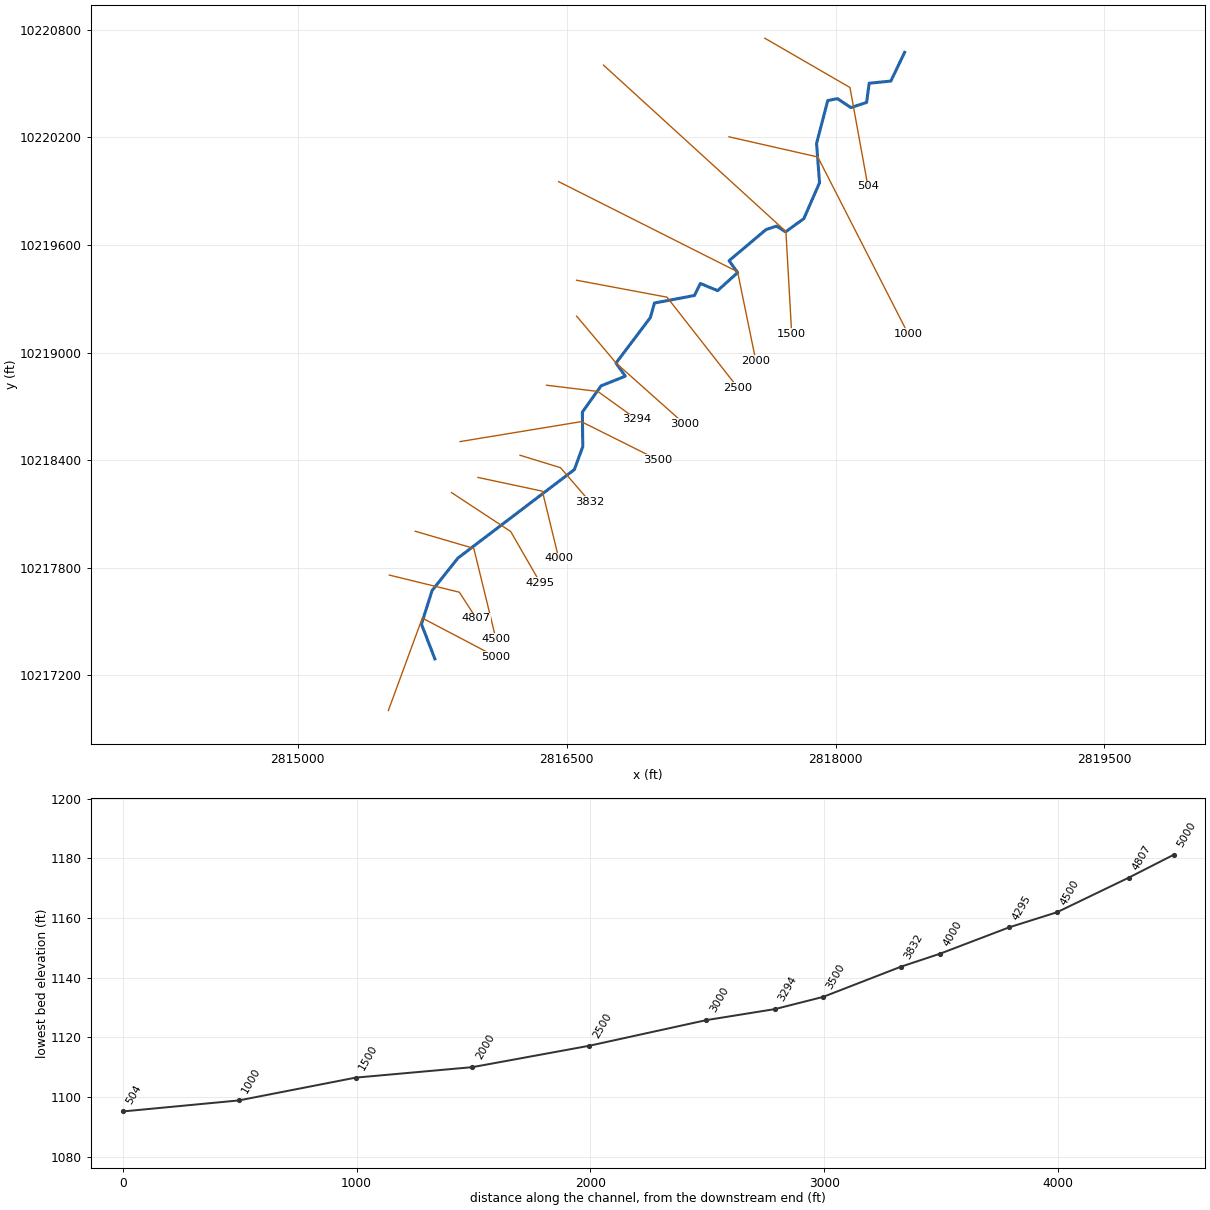
--- SANFERNANDO096.prj (project) ---

Proj Title=SANFERNANDO096 Base Level Engineering
Current Plan=p01
Default Exp/Contr=0.3,0.1
English Units
Geom File=g01
Flow File=f01
Plan File=p01
BEGIN DESCRIPTION:
SANFERNANDO096
END DESCRIPTION:

--- SANFERNANDO096.p01 (plan) ---

Plan Title=Multiple Run
Short Identifier=Multiple
Geom File=g01
Flow File=f01
Subcritical Flow
K Sum by GR= 0
Std Step Tol= 0.01
Critical Tol= 0.01
Num of Std Step Trials= 20
Max Error Tol= 0.3
Flow Tol Ratio= 0.001
Split Flow NTrial= 30
Split Flow Tol= 0.02
Split Flow Ratio= 0.02
Log Output Level= 0
Friction Slope Method= 1
Unsteady Friction Slope Method= 2
Unsteady Bridges Friction Slope Method= 1
Parabolic Critical Depth
Global Vel Dist=  1 , 1 , 1
Global Log Level= 0
CheckData=True
Encroach Param= -1, 0, 0, 0
BEGIN DESCRIPTION:
Multiple Run
END DESCRIPTION:

--- SANFERNANDO096.f01 (steady flow) ---

Flow Title=Multiple
Number of Profiles=7
Profile Names=10-year,25-year,50-year,1pct_min,100-year,1pct_plu,500-year
River Rch & RM= SANFERNANDO096,Reach-1,5000
     196     301     439     297     578    1124     813
Boundary for River Rch & Prof#=SANFERNANDO096,Reach-1,1
Up Type=0
Dn Type=3
Dn Slope=0.005
Boundary for River Rch & Prof#=SANFERNANDO096,Reach-1,2
Up Type=0
Dn Type=3
Dn Slope=0.005
Boundary for River Rch & Prof#=SANFERNANDO096,Reach-1,3
Up Type=0
Dn Type=3
Dn Slope=0.005
Boundary for River Rch & Prof#=SANFERNANDO096,Reach-1,4
Up Type=0
Dn Type=3
Dn Slope=0.005
Boundary for River Rch & Prof#=SANFERNANDO096,Reach-1,5
Up Type=0
Dn Type=3
Dn Slope=0.005
Boundary for River Rch & Prof#=SANFERNANDO096,Reach-1,6
Up Type=0
Dn Type=3
Dn Slope=0.005
Boundary for River Rch & Prof#=SANFERNANDO096,Reach-1,7
Up Type=0
Dn Type=3
Dn Slope=0.005

--- SANFERNANDO096.g01 (geometry) ---

Geom Title=Existing Conditions

River Reach=SANFERNANDO096,Reach-1
Reach XY= 30
      2815765.25     10217291.00      2815690.25     10217485.00
      2815749.50     10217672.00      2815893.25     10217853.00
      2816543.25     10218347.00      2816590.25     10218475.00
      2816588.00     10218668.00      2816692.25     10218814.00
      2816827.50     10218868.00      2816775.50     10218941.00
      2816967.25     10219195.00      2816990.00     10219276.00
      2817213.00     10219318.00      2817246.25     10219385.00
      2817342.25     10219345.00      2817454.25     10219446.00
      2817406.25     10219512.00      2817612.75     10219686.00
      2817671.25     10219705.00      2817721.50     10219673.00
      2817823.50     10219747.00      2817911.00     10219947.00
      2817894.25     10220166.00      2817956.75     10220405.00
      2818011.00     10220416.00      2818086.00     10220366.00
      2818173.50     10220395.00      2818187.75     10220502.00
      2818308.75     10220514.00      2818385.50     10220674.00

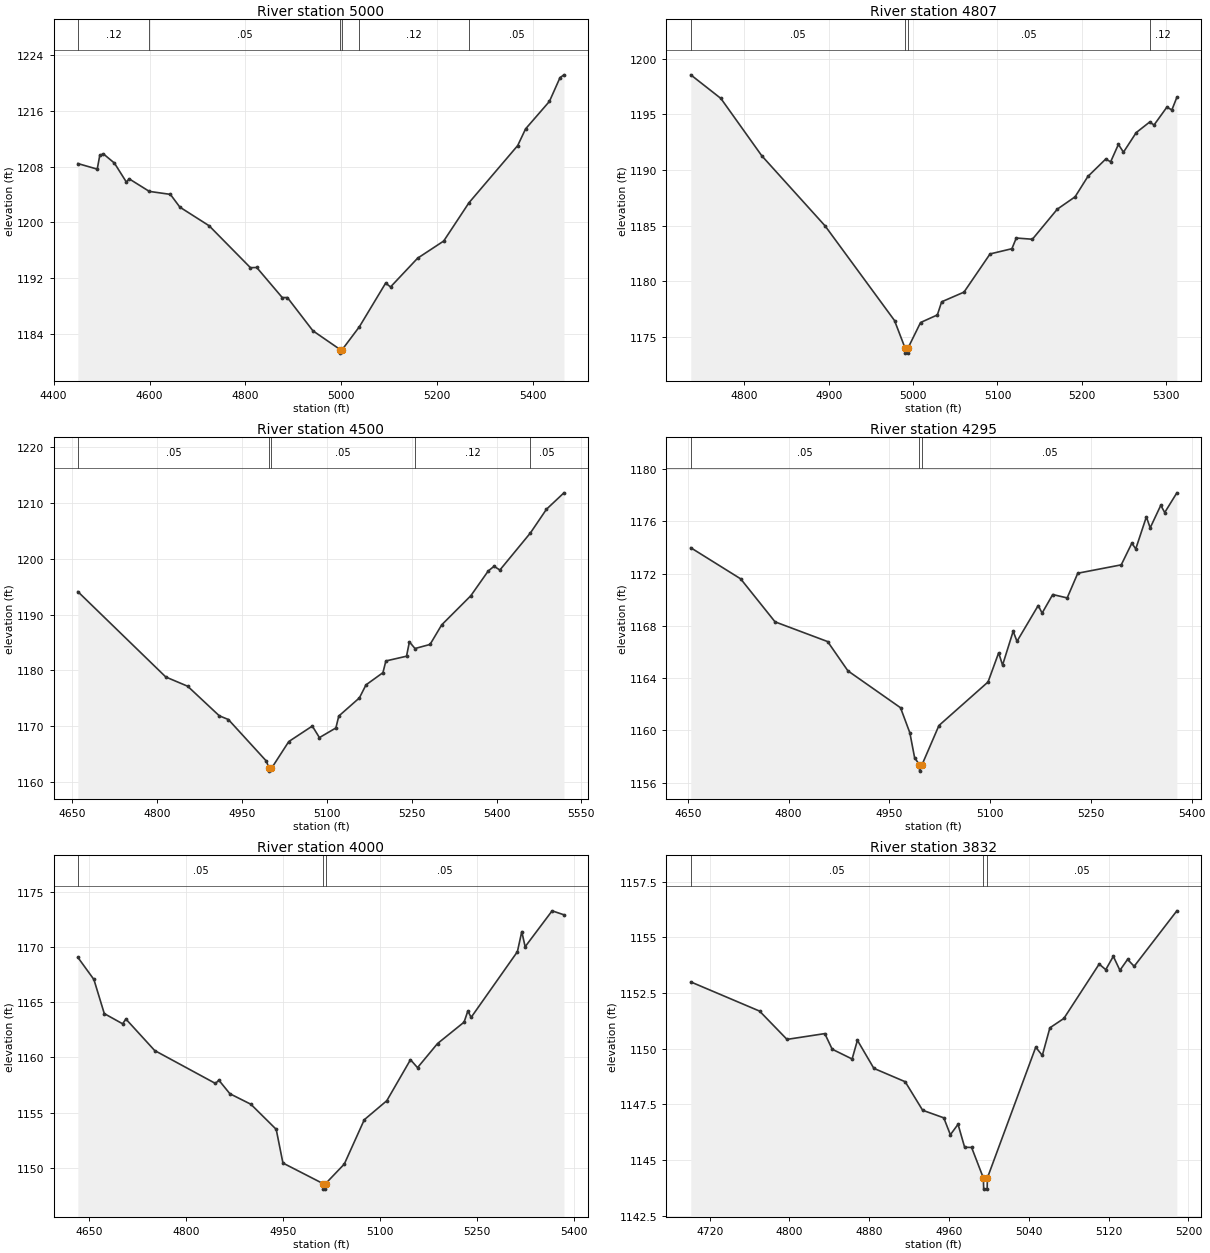
Type RM Length L Ch R = 1,5000,193,193,193
BEGIN DESCRIPTION:
SANFERNANDO096 10.0
END DESCRIPTION:
XS GIS Cut Line= 3
      2815505.67     10217003.09      2815695.08     10217518.91
      2816105.72     10217303.09
#Sta/Elev= 30
  4450.5 1208.43  4490.9 1207.63  4496.3 1209.63  4503.8 1209.81  4526.7 1208.50
  4551.9 1205.75  4557.2 1206.25  4599.4 1204.44  4643.4 1204.01  4663.2 1202.18
  4724.2 1199.51  4810.3 1193.50  4823.4 1193.53  4876.6 1189.22  4887.3 1189.22
  4940.6 1184.45  4997.6 1181.75  4997.8 1181.25  5001.6 1181.75  5037.6 1185.05
  5092.2 1191.29  5102.4 1190.74  5158.8 1194.86  5213.2 1197.32  5265.9 1202.81
  5367.5 1211.01  5383.9 1213.40  5433.6 1217.34  5455.7 1220.75  5463.9 1221.15
#Mann=6,-1,0
  4450.5    0.12       0  4599.4    0.05       0  4997.6    0.03       0
  5001.6    0.05       0  5037.6    0.12       0  5265.9    0.05       0
Bank Sta=4997.6,5001.6
Exp/Cntr=0.3,0.1

Type RM Length L Ch R = 1,4807,307,307,307
BEGIN DESCRIPTION:
Mapping XS ac8c05d9
END DESCRIPTION:
XS GIS Cut Line= 3
      2815510.97     10217758.60      2815901.63     10217663.10
      2815996.29     10217516.81
#Sta/Elev= 30
  4736.3 1198.55  4772.0 1196.43  4820.5 1191.28  4895.6 1184.98  4977.9 1176.48
  4990.2 1174.05  4990.4 1173.55  4993.9 1173.55  4994.2 1174.05  5008.8 1176.30
  5028.7 1176.98  5033.8 1178.16  5060.3 1179.03  5091.2 1182.46  5117.1 1182.93
  5122.3 1183.89  5141.4 1183.78  5170.9 1186.48  5192.0 1187.59  5207.2 1189.42
  5228.3 1190.98  5234.2 1190.74  5243.4 1192.30  5249.4 1191.60  5264.5 1193.36
  5280.3 1194.30  5285.7 1194.05  5300.8 1195.64  5306.8 1195.40  5312.7 1196.53
#Mann=4,-1,0
  4736.3    0.05       0  4990.2    0.03       0  4994.2    0.05       0
  5280.3    0.12       0
Bank Sta=4990.2,4994.2
Exp/Cntr=0.3,0.1

Type RM Length L Ch R = 1,4500,205,205,205
BEGIN DESCRIPTION:
SANFERNANDO096 9.0
END DESCRIPTION:
XS GIS Cut Line= 3
      2815655.70     10218003.11      2815982.37     10217907.42
      2816105.69     10217403.08
#Sta/Elev= 30
  4659.6 1194.14  4815.2 1178.83  4853.8 1177.18  4909.7 1171.88  4925.8 1171.21
  4992.7 1163.79  4998.0 1162.46  4998.2 1161.96  5002.0 1162.46  5032.6 1167.26
  5074.2 1170.04  5086.8 1167.97  5115.9 1169.70  5121.0 1171.83  5157.5 1175.09
  5169.1 1177.42  5199.1 1179.61  5204.3 1181.71  5240.8 1182.56  5245.9 1185.13
  5255.8 1183.94  5282.4 1184.67  5303.0 1188.18  5354.5 1193.40  5385.3 1197.84
  5395.6 1198.68  5405.9 1198.01  5459.9 1204.66  5488.3 1208.91  5519.2 1211.85
#Mann=5,-1,0
  4659.6    0.05       0  4998.0    0.03       0  5002.0    0.05       0
  5255.8    0.12       0  5459.9    0.05       0
Bank Sta=4998,5002
Exp/Cntr=0.3,0.1

Type RM Length L Ch R = 1,4295,295,295,295
BEGIN DESCRIPTION:
Mapping XS d7a7552d
END DESCRIPTION:
XS GIS Cut Line= 3
      2815858.21     10218218.67      2816188.09     10218001.64
      2816352.17     10217716.67
#Sta/Elev= 30
  4654.3 1173.98  4728.6 1171.60  4779.8 1168.31  4858.1 1166.80  4888.3 1164.56
  4966.6 1161.74  4980.5 1159.82  4987.6 1157.91  4994.7 1157.39  4995.0 1156.89
  4998.7 1157.39  5023.8 1160.38  5096.9 1163.71  5112.7 1165.94  5118.5 1165.00
  5134.3 1167.59  5140.0 1166.82  5171.6 1169.56  5177.4 1168.98  5193.2 1170.40
  5214.7 1170.14  5230.5 1172.03  5295.2 1172.67  5311.0 1174.33  5316.8 1173.89
  5332.6 1176.34  5338.3 1175.50  5354.1 1177.23  5359.9 1176.67  5378.0 1178.18
#Mann=3,-1,0
  4654.3    0.05       0  4994.7    0.03       0  4998.7    0.05       0
Bank Sta=4994.7,4998.7
Exp/Cntr=0.3,0.1

Type RM Length L Ch R = 1,4000,168,168,168
BEGIN DESCRIPTION:
SANFERNANDO096 8.0
END DESCRIPTION:
XS GIS Cut Line= 3
      2816005.69     10218303.11      2816364.84     10218226.64
      2816455.68     10217853.13
#Sta/Elev= 30
  4632.8 1169.05  4657.6 1167.05  4673.7 1163.96  4702.0 1163.04  4707.1 1163.47
  4751.6 1160.62  4845.6 1157.64  4850.8 1157.94  4867.9 1156.71  4900.3 1155.76
  4939.5 1153.49  4949.9 1150.44  5011.9 1148.58  5012.2 1148.08  5015.7 1148.08
  5015.9 1148.58  5044.8 1150.35  5075.7 1154.36  5110.5 1156.08  5147.1 1159.79
  5158.0 1159.07  5188.9 1161.25  5230.0 1163.19  5235.8 1164.20  5240.9 1163.62
  5312.4 1169.56  5319.2 1171.38  5324.4 1170.01  5366.1 1173.26  5384.4 1172.90
#Mann=3,-1,0
  4632.8    0.05       0  5011.9    0.03       0  5015.9    0.05       0
Bank Sta=5011.9,5015.9
Exp/Cntr=0.3,0.1

Type RM Length L Ch R = 1,3832,332,332,332
BEGIN DESCRIPTION:
Mapping XS 4e36e554
END DESCRIPTION:
XS GIS Cut Line= 3
      2816240.17     10218426.99      2816465.87     10218357.55
      2816630.09     10218167.39
#Sta/Elev= 30
  4701.0 1153.00  4770.0 1151.69  4797.5 1150.42  4835.4 1150.68  4842.8 1149.98
  4862.8 1149.54  4868.1 1150.38  4884.6 1149.12  4916.0 1148.52  4933.5 1147.24
  4954.7 1146.90  4961.3 1146.14  4969.0 1146.61  4975.6 1145.58  4982.6 1145.57
  4994.4 1144.20  4994.7 1143.70  4998.2 1143.70  4998.4 1144.20  5046.9 1150.07
  5053.5 1149.70  5061.1 1150.94  5075.1 1151.36  5110.5 1153.80  5117.1 1153.55
  5124.7 1154.15  5131.3 1153.52  5139.0 1154.01  5145.6 1153.70  5188.4 1156.19
#Mann=3,-1,0
  4701.0    0.05       0  4994.4    0.05       0  4998.4    0.05       0
Bank Sta=4994.4,4998.4
Exp/Cntr=0.3,0.1

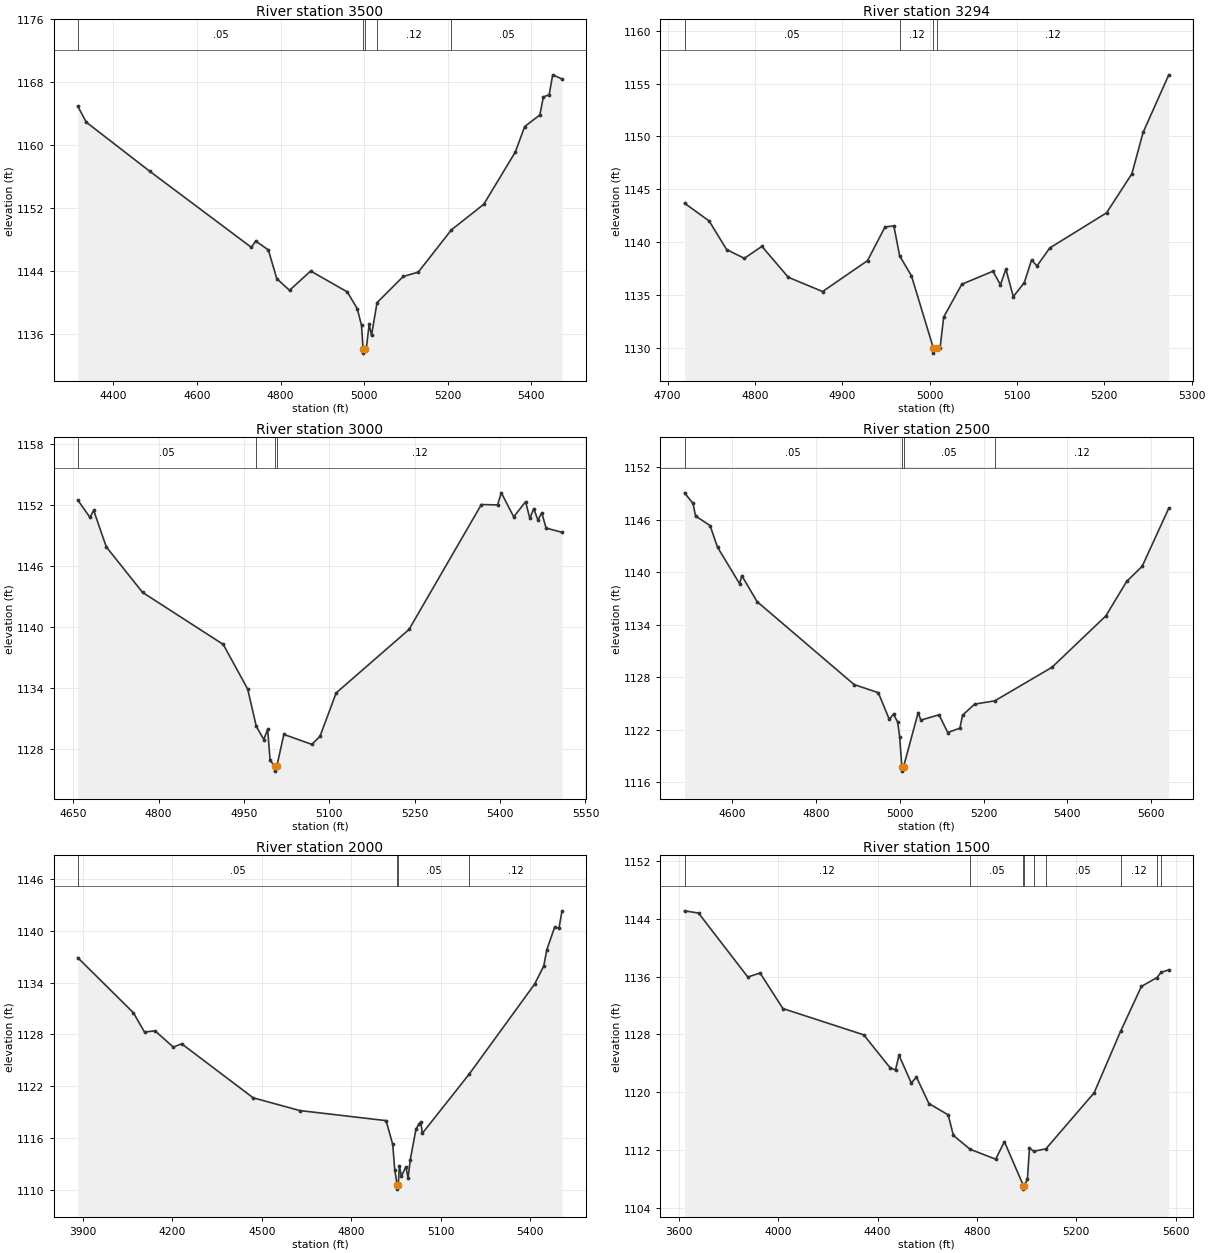
Type RM Length L Ch R = 1,3500,206,206,206
BEGIN DESCRIPTION:
SANFERNANDO096 7.0
END DESCRIPTION:
XS GIS Cut Line= 3
      2815905.65     10218503.11      2816581.95     10218614.47
      2817005.66     10218403.12
#Sta/Elev= 30
  4314.6 1164.98  4334.9 1162.95  4486.9 1156.71  4730.2 1147.04  4740.3 1147.85
  4770.7 1146.72  4791.0 1143.06  4821.4 1141.59  4872.0 1144.04  4959.5 1141.39
  4983.5 1139.26  4993.7 1137.12  4997.4 1134.11  4997.6 1133.61  5001.4 1134.11
  5004.9 1134.11  5012.0 1137.28  5017.6 1135.86  5030.8 1140.02  5093.6 1143.35
  5129.5 1143.90  5208.8 1149.27  5286.1 1152.51  5361.8 1159.16  5384.1 1162.39
  5420.4 1163.86  5428.8 1166.14  5442.8 1166.45  5451.2 1168.96  5473.5 1168.43
#Mann=5,-1,0
  4314.6    0.05       0  4997.4    0.05       0  5001.4    0.05       0
  5030.8    0.12       0  5208.8    0.05       0
Bank Sta=4997.4,5001.4
Exp/Cntr=0.3,0.1

Type RM Length L Ch R = 1,3294,294,294,294
BEGIN DESCRIPTION:
Mapping XS 4347daf3
END DESCRIPTION:
XS GIS Cut Line= 3
      2816387.73     10218817.62      2816674.20     10218782.89
      2816889.93     10218627.57
#Sta/Elev= 30
  4719.4 1143.69  4747.6 1142.01  4767.7 1139.30  4787.9 1138.48  4808.0 1139.61
  4838.2 1136.69  4877.5 1135.34  4928.9 1138.26  4949.0 1141.45  4959.1 1141.54
  4965.7 1138.71  4979.2 1136.83  5004.2 1130.02  5004.4 1129.52  5008.2 1130.02
  5012.0 1130.02  5016.1 1132.93  5036.9 1136.03  5072.5 1137.26  5081.1 1135.98
  5087.3 1137.46  5095.8 1134.86  5108.4 1136.18  5116.7 1138.33  5122.9 1137.76
  5137.6 1139.46  5202.6 1142.78  5231.6 1146.48  5244.4 1150.38  5273.8 1155.82
#Mann=4,-1,0
  4719.4    0.05       0  4965.7    0.12       0  5004.2    0.07       0
  5008.2    0.12       0
Bank Sta=5004.2,5008.2
Exp/Cntr=0.3,0.1

Type RM Length L Ch R = 1,3000,500,500,500
BEGIN DESCRIPTION:
SANFERNANDO096 6.0
END DESCRIPTION:
XS GIS Cut Line= 3
      2816555.65     10219203.15      2816775.83     10218941.58
      2817155.70     10218603.09
#Sta/Elev= 30
  4658.1 1152.48  4679.6 1150.77  4686.1 1151.46  4708.2 1147.88  4771.9 1143.40
  4913.7 1138.28  4956.6 1133.89  4971.7 1130.23  4984.9 1128.93  4991.7 1129.94
  4996.0 1126.88  5003.9 1126.32  5004.1 1125.82  5007.9 1126.32  5020.1 1129.43
  5069.4 1128.45  5083.6 1129.24  5112.0 1133.51  5240.0 1139.75  5367.1 1152.04
  5395.5 1152.00  5402.2 1153.19  5423.9 1150.83  5444.8 1152.31  5452.3 1150.67
  5459.0 1151.64  5466.5 1150.51  5473.2 1151.23  5480.8 1149.72  5508.8 1149.31
#Mann=4,-1,0
  4658.1    0.05       0  4971.7    0.12       0  5003.9    0.07       0
  5007.9    0.12       0
Bank Sta=5003.9,5007.9
Exp/Cntr=0.3,0.1

Type RM Length L Ch R = 1,2500,500,500,500
BEGIN DESCRIPTION:
SANFERNANDO096 5.0
END DESCRIPTION:
XS GIS Cut Line= 3
      2816555.68     10219403.11      2817060.21     10219308.62
      2817455.67     10218803.13
#Sta/Elev= 30
  4486.7 1149.10  4507.1 1147.88  4513.0 1146.45  4547.7 1145.35  4565.6 1142.86
  4618.2 1138.69  4623.3 1139.63  4659.7 1136.65  4891.3 1127.15  4949.0 1126.22
  4975.1 1123.17  4985.2 1123.76  4995.2 1122.86  5000.0 1121.12  5005.1 1117.74
  5005.3 1117.24  5009.1 1117.74  5044.1 1123.95  5050.4 1123.08  5093.8 1123.69
  5114.6 1121.66  5143.6 1122.16  5149.9 1123.65  5178.8 1124.91  5226.9 1125.29
  5363.3 1129.13  5491.7 1135.01  5541.5 1138.97  5578.3 1140.68  5641.8 1147.34
#Mann=4,-1,0
  4486.7    0.05       0  5005.1    0.05       0  5009.1    0.05       0
  5226.9    0.12       0
Bank Sta=5005.1,5009.1
Exp/Cntr=0.3,0.1

Type RM Length L Ch R = 1,2000,500,500,500
BEGIN DESCRIPTION:
SANFERNANDO096 4.0
END DESCRIPTION:
XS GIS Cut Line= 3
      2816455.65     10219953.13      2817453.77     10219450.34
      2817555.69     10218953.08
#Sta/Elev= 30
  3882.4 1136.90  4069.3 1130.51  4106.4 1128.28  4141.8 1128.42  4203.2 1126.53
  4231.1 1126.92  4470.9 1120.66  4627.1 1119.18  4917.1 1118.01  4939.4 1115.26
  4946.2 1112.34  4954.1 1110.57  4954.4 1110.07  4958.1 1110.57  4961.7 1112.74
  4968.6 1111.59  4984.0 1112.66  4990.9 1111.33  4998.3 1113.48  5017.6 1117.05
  5027.8 1117.63  5033.7 1117.86  5038.8 1116.54  5196.2 1123.41  5415.7 1133.84
  5446.3 1135.94  5456.5 1137.81  5482.4 1140.40  5497.4 1140.33  5507.6 1142.33
#Mann=4,-1,0
  3882.4    0.05       0  4954.1    0.05       0  4958.1    0.05       0
  5196.2    0.12       0
Bank Sta=4954.1,4958.1
Exp/Cntr=0.3,0.1

Type RM Length L Ch R = 1,1500,500,500,500
BEGIN DESCRIPTION:
SANFERNANDO096 3.0
END DESCRIPTION:
XS GIS Cut Line= 3
      2816705.70     10220603.09      2817723.30     10219674.80
      2817755.68     10219103.12
#Sta/Elev= 30
  3622.6 1145.14  3679.0 1144.83  3877.6 1135.96  3926.9 1136.52  4018.8 1131.59
  4344.5 1127.94  4450.6 1123.37  4472.2 1123.08  4486.3 1125.12  4535.7 1121.27
  4556.6 1122.09  4606.6 1118.42  4684.3 1116.85  4705.4 1113.99  4772.6 1112.08
  4875.5 1110.70  4910.7 1113.13  4987.0 1107.05  4987.3 1106.55  4991.0 1107.05
  5003.3 1107.92  5011.7 1112.24  5029.2 1111.80  5077.9 1112.14  5272.1 1119.91
  5378.3 1128.41  5462.4 1134.66  5524.6 1135.88  5541.5 1136.59  5572.6 1136.96
#Mann=9,-1,0
  3622.6    0.12       0  4772.6    0.05       0  4987.0    0.05       0
  4991.0    0.05       0  5029.2    0.12       0  5077.9    0.05       0
  5378.3    0.12       0  5524.6    0.05       0  5541.5    0.12       0
Bank Sta=4987,4991
Exp/Cntr=0.3,0.1

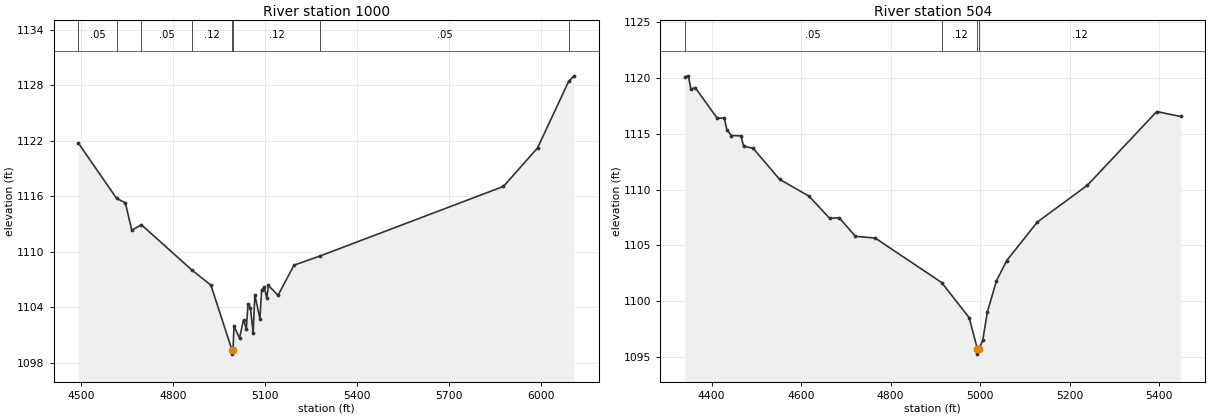
Type RM Length L Ch R = 1,1000,496,496,496
BEGIN DESCRIPTION:
SANFERNANDO096 2.0
END DESCRIPTION:
XS GIS Cut Line= 3
      2817405.71     10220203.11      2817901.00     10220090.61
      2818405.69     10219103.11
#Sta/Elev= 30
  4492.1 1121.74  4617.0 1115.75  4645.4 1115.28  4666.4 1112.31  4697.8 1112.90
  4862.7 1108.00  4924.4 1106.37  4992.6 1099.41  4992.8 1098.91  4996.6 1099.41
  4999.8 1101.94  5017.7 1100.65  5030.9 1102.62  5039.9 1101.63  5045.5 1104.35
  5053.3 1103.92  5062.1 1101.20  5067.7 1105.32  5084.3 1102.74  5089.9 1105.86
  5098.3 1106.16  5106.5 1104.99  5112.1 1106.34  5143.2 1105.27  5195.4 1108.53
  5281.7 1109.54  5878.5 1117.05  5989.6 1121.21  6091.0 1128.40  6109.0 1129.01
#Mann=8,-1,0
  4492.1    0.05       0  4617.0    0.12       0  4697.8    0.05       0
  4862.7    0.12       0  4992.6    0.07       0  4996.6    0.12       0
  5281.7    0.05       0  6091.0    0.12       0
Bank Sta=4992.6,4996.6
Exp/Cntr=0.3,0.1

Type RM Length L Ch R = 1,504,0,0,0
BEGIN DESCRIPTION:
SANFERNANDO096 1.0
END DESCRIPTION:
XS GIS Cut Line= 3
      2817605.66     10220753.13      2818080.68     10220478.11
      2818180.68     10219928.12
#Sta/Elev= 30
  4340.0 1120.13  4347.9 1120.21  4353.7 1119.00  4363.1 1119.16  4412.5 1116.40
  4428.3 1116.43  4434.0 1115.36  4444.0 1114.85  4465.6 1114.82  4471.3 1113.91
  4492.9 1113.69  4551.7 1110.92  4617.3 1109.41  4663.6 1107.42  4685.1 1107.46
  4721.3 1105.80  4765.5 1105.64  4913.9 1101.65  4975.3 1098.50  4993.6 1095.72
  4993.9 1095.22  4997.6 1095.72  5005.8 1096.46  5015.9 1098.98  5036.3 1101.79
  5059.1 1103.61  5127.7 1107.08  5239.5 1110.38  5394.5 1117.00  5447.9 1116.56
#Mann=4,-1,0
  4340.0    0.05       0  4913.9    0.12       0  4993.6    0.07       0
  4997.6    0.12       0
Bank Sta=4993.6,4997.6
Exp/Cntr=0.3,0.1

Chan Stop Cuts=-1