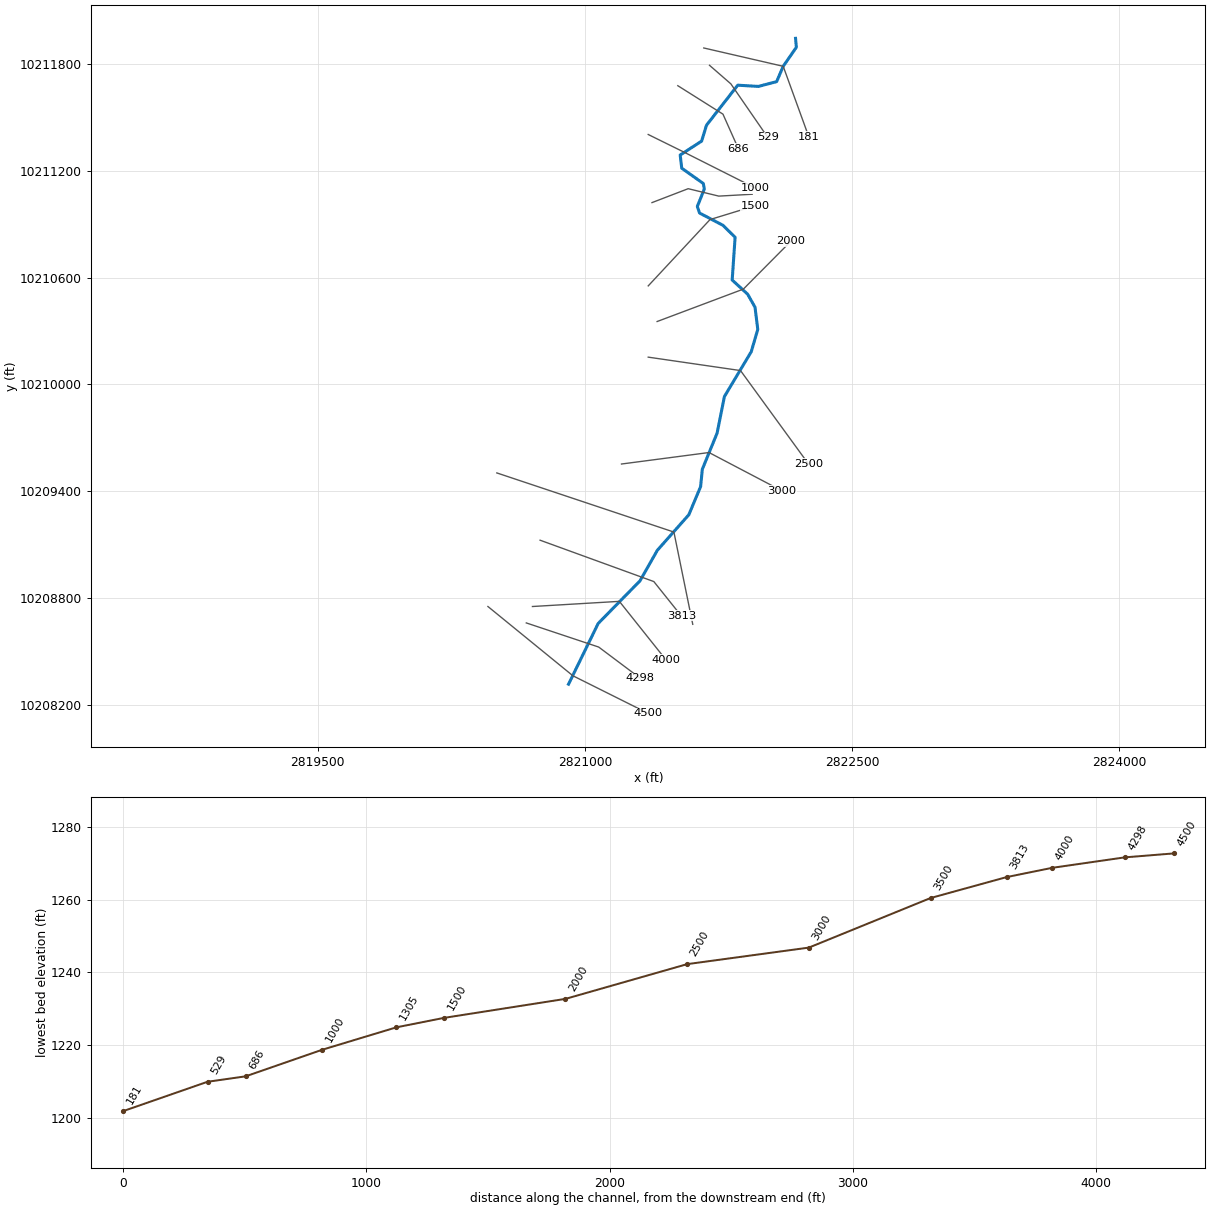
--- SANFERNANDO097.prj (project) ---

Proj Title=SANFERNANDO097 Base Level Engineering
Current Plan=p01
Default Exp/Contr=0.3,0.1
English Units
Geom File=g01
Flow File=f01
Plan File=p01
Y Axis Title=Elevation
X Axis Title(PF)=Main Channel Distance
X Axis Title(XS)=Station
BEGIN DESCRIPTION:
SANFERNANDO097
END DESCRIPTION:
DSS Export Rating Curves= 0
DSS Export Rating Curve Sorted= 0
DSS Export Volume Flow Curves= 0
DXF OffsetX= 0
DXF OffsetY= 0
DXF ScaleX= 1
DXF ScaleY= 10

--- SANFERNANDO097.p01 (plan) ---

Plan Title=Multiple Run
Short Identifier=Multiple
Geom File=g01
Flow File=f01
Subcritical Flow
K Sum by GR= 0
Std Step Tol= 0.01
Critical Tol= 0.01
Num of Std Step Trials= 20
Max Error Tol= 0.3
Flow Tol Ratio= 0.001
Split Flow NTrial= 30
Split Flow Tol= 0.02
Split Flow Ratio= 0.02
Log Output Level= 0
Friction Slope Method= 1
Unsteady Friction Slope Method= 2
Unsteady Bridges Friction Slope Method= 1
Parabolic Critical Depth
Global Vel Dist=  1 , 1 , 1
Global Log Level= 0
CheckData=True
Encroach Param= -1, 0, 0, 0
BEGIN DESCRIPTION:
Multiple Run
END DESCRIPTION:

--- SANFERNANDO097.f01 (steady flow) ---

Flow Title=Multiple
Program Version=4.10
Number of Profiles= 7
Profile Names=10-year,25-year,50-year,1pct_min,100-year,1pct_plu,500-year
River Rch & RM=SANFERNANDO097,Reach-1         ,4500
     202     311     402     275     523     995     727
River Rch & RM=SANFERNANDO097,Reach-1         ,181
     891    1521    3331    2075    4835   11265    7082
Boundary for River Rch & Prof#=SANFERNANDO097,Reach-1         , 1
Up Type= 0
Dn Type= 3
Dn Slope=0.003
Boundary for River Rch & Prof#=SANFERNANDO097,Reach-1         , 2
Up Type= 0
Dn Type= 3
Dn Slope=0.003
Boundary for River Rch & Prof#=SANFERNANDO097,Reach-1         , 3
Up Type= 0
Dn Type= 3
Dn Slope=0.003
Boundary for River Rch & Prof#=SANFERNANDO097,Reach-1         , 4
Up Type= 0
Dn Type= 3
Dn Slope=0.003
Boundary for River Rch & Prof#=SANFERNANDO097,Reach-1         , 5
Up Type= 0
Dn Type= 3
Dn Slope=0.003
Boundary for River Rch & Prof#=SANFERNANDO097,Reach-1         , 6
Up Type= 0
Dn Type= 3
Dn Slope=0.003
Boundary for River Rch & Prof#=SANFERNANDO097,Reach-1         , 7
Up Type= 0
Dn Type= 3
Dn Slope=0.003
DSS Import GetInterval= 0
DSS Import GetPeak= 0
DSS Import FillOption= 0

--- SANFERNANDO097.g01 (geometry) ---

Geom Title=Existing Conditions
Program Version=4.10

River Reach=SANFERNANDO097  ,Reach-1
Reach XY= 30
      2820908.25       10208317.      2821074.75       10208658.
      2821309.25       10208897.        2821407.       10209069.
       2821583.5       10209268.      2821649.75       10209426.
       2821659.5       10209524.       2821742.5       10209727.
       2821783.5       10209932.      2821934.25       10210184.
      2821970.75       10210309.        2821955.       10210434.
       2821913.5       10210507.        2821827.       10210586.
       2821843.5       10210826.      2821775.75       10210893.
        2821644.       10210962.      2821631.25       10210999.
      2821670.75       10211097.        2821665.       10211128.
      2821543.75       10211214.      2821535.25       10211288.
       2821655.5       10211366.      2821682.75       10211455.
      2821858.25       10211680.      2821974.25       10211673.
      2822076.75       10211700.       2822113.5       10211786.
       2822187.5       10211893.      2822182.75       10211943.

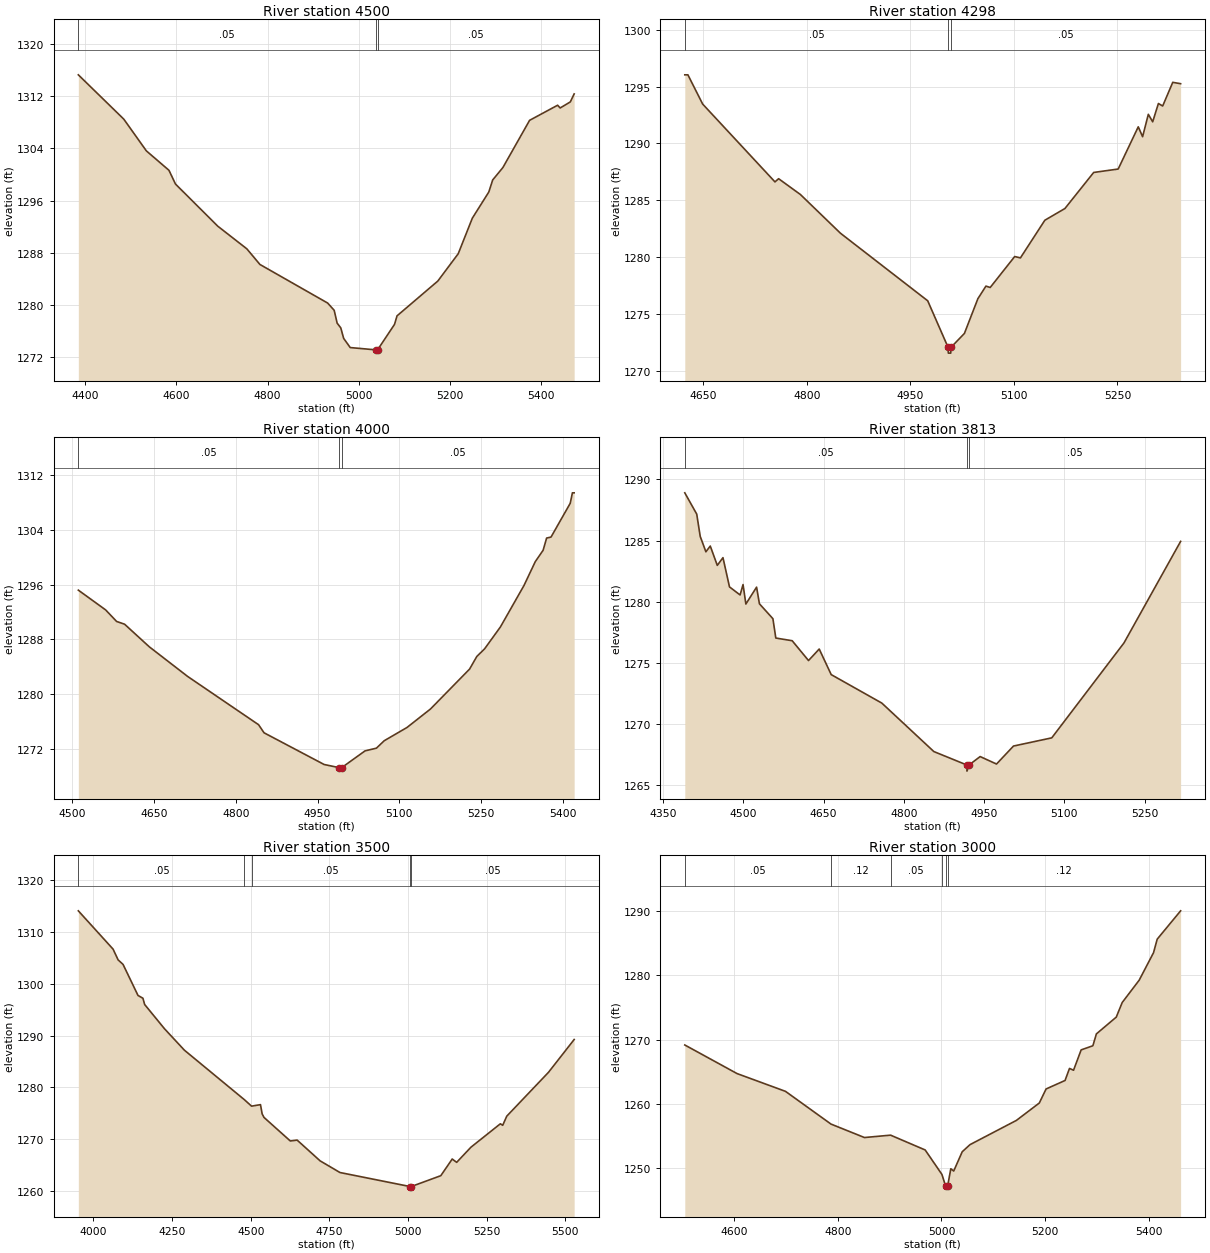
Type RM Length L Ch R = 1 ,4500    ,202,202,202
BEGIN DESCRIPTION:
SANFERNANDO097 9.0
END DESCRIPTION:
XS GIS Cut Line= 3
      2820455.72     10208753.09      2820932.73     10208364.28
      2821355.65     10208153.13
#Sta/Elev= 30
  4384.6 1315.22  4484.4 1308.44  4533.9 1303.59  4583.5 1300.62  4597.8 1298.52
  4690.5 1292.08  4754.4 1288.61  4783.1 1286.22  4931.7 1280.32  4946.1 1279.21
  4952.6 1277.24  4960.5 1276.53  4966.9 1274.91  4981.3 1273.51  5037.3 1273.16
  5037.6 1272.66  5041.3 1273.16  5078.5 1277.06    5084 1278.36  5173.5 1283.68
  5218.3 1287.86  5249.2 1293.29  5285.4  1297.3  5293.9 1299.14  5316.3 1301.04
  5374.9 1308.26  5436.4 1310.57    5442 1310.15  5464.3 1311.08  5472.7  1312.3
#Mann= 3 ,-1 , 0
  4384.6     .05       0  5037.3     .03       0  5041.3     .05       0
Bank Sta=5037.3,5041.3
XS Rating Curve= 0 ,0
Exp/Cntr=0.3,0.1

Type RM Length L Ch R = 1 ,4298    ,298,298,298
BEGIN DESCRIPTION:
Mapping XS 4070c7e2
END DESCRIPTION:
XS GIS Cut Line= 3
      2820671.16     10208660.95      2821077.58     10208525.48
      2821309.81      10208351.3
#Sta/Elev= 30
  4622.9 1296.03  4627.4 1296.03  4648.8 1293.46  4753.6 1286.62  4758.9  1286.9
  4790.5 1285.51  4848.5 1282.11    4975 1276.17  5004.6 1272.07  5004.9 1271.57
  5008.4 1271.57  5008.6 1272.07  5028.2  1273.3  5047.7 1276.35  5059.4 1277.46
  5065.6 1277.34  5101.1 1280.06  5109.4 1279.94  5144.8 1283.25  5173.9 1284.28
  5215.6 1287.45  5251.1 1287.75  5280.2 1291.46  5286.5 1290.59  5294.8 1292.56
  5301.1  1291.9  5309.4 1293.51  5315.6 1293.29  5330.2 1295.37  5341.6 1295.25
#Mann= 3 ,-1 , 0
  4622.9     .05       0  5004.6     .05       0  5008.6     .05       0
Bank Sta=5004.6,5008.6
XS Rating Curve= 0 ,0
Exp/Cntr=0.3,0.1

Type RM Length L Ch R = 1 ,4000    ,187,187,187
BEGIN DESCRIPTION:
SANFERNANDO097 8.0
END DESCRIPTION:
XS GIS Cut Line= 3
      2820705.64     10208753.11      2821193.59     10208782.05
      2821455.69     10208453.11
#Sta/Elev= 30
  4511.2 1295.18  4561.3 1292.29  4581.4  1290.6    4596  1290.2  4641.5 1286.88
  4711.6 1282.56  4841.8 1275.49  4851.8 1274.31    4962 1269.67  4990.1  1269.2
  4990.3  1268.7  4993.8  1268.7  4994.1  1269.2    5037 1271.66  5057.9 1272.06
  5072.3 1273.15  5113.9 1275.08  5157.1 1277.79  5228.8 1283.63    5242 1285.47
  5256.4  1286.6  5285.3 1289.79  5328.5 1295.85  5349.3 1299.35  5363.7 1301.02
  5370.1  1302.8  5378.2 1302.95  5413.4 1307.89  5417.4 1309.42  5420.6 1309.42
#Mann= 3 ,-1 , 0
  4511.2     .05       0  4990.1     .03       0  4994.1     .05       0
Bank Sta=4990.1,4994.1
XS Rating Curve= 0 ,0
Exp/Cntr=0.3,0.1

Type RM Length L Ch R = 1 ,3813    ,313,313,313
BEGIN DESCRIPTION:
Mapping XS 655fb12a
END DESCRIPTION:
XS GIS Cut Line= 3
      2820748.65     10209125.36       2821387.2     10208893.16
      2821541.34     10208700.49
#Sta/Elev= 30
  4390.9 1288.91  4413.2 1287.17  4419.7 1285.35  4430.3 1284.09  4438.5 1284.56
  4451.6 1282.98  4462.2 1283.61  4474.4 1281.22  4494.2 1280.56  4499.7 1281.41
    4505 1279.82    4525  1281.2  4530.3 1279.84  4555.5 1278.62  4560.9 1277.04
  4591.5 1276.82    4622  1275.2    4642 1276.14  4664.4 1274.05    4759 1271.72
  4856.1 1267.76  4917.8 1266.66    4918 1266.16  4921.8 1266.66  4942.6 1267.35
  4973.2 1266.74  5004.9 1268.21  5076.4 1268.88  5211.3 1276.64  5317.1 1284.94
#Mann= 3 ,-1 , 0
  4390.9     .05       0  4917.8     .05       0  4921.8     .05       0
Bank Sta=4917.8,4921.8
XS Rating Curve= 0 ,0
Exp/Cntr=0.3,0.1

Type RM Length L Ch R = 1 ,3500    ,500,500,500
BEGIN DESCRIPTION:
SANFERNANDO097 7.0
END DESCRIPTION:
XS GIS Cut Line= 3
      2820505.68     10209503.11      2821499.89     10209171.06
      2821605.68     10208653.15
#Sta/Elev= 30
  3951.8 1314.03  4062.4 1306.64  4078.3 1304.58    4094 1303.71  4141.6 1297.72
  4157.2 1297.19  4162.7 1295.98  4225.9  1291.3  4289.2 1287.17  4479.8 1277.64
  4502.7 1276.39  4531.1 1276.68  4536.4  1274.9  4542.2 1274.22  4625.9 1269.68
  4647.6 1269.85  4720.7 1265.85  4783.9  1263.6  5006.6  1260.9  5006.8  1260.4
  5010.6  1260.9  5104.5 1262.99  5140.8  1266.2    5155 1265.56  5200.4 1268.48
  5293.9 1272.99  5301.4  1272.7  5314.3 1274.46    5447 1282.91  5528.6 1289.23
#Mann= 5 ,-1 , 0
  3951.8     .05       0  4479.8     .12       0  4502.7     .05       0
  5006.6     .05       0  5010.6     .05       0
Bank Sta=5006.6,5010.6
XS Rating Curve= 0 ,0
Exp/Cntr=0.3,0.1

Type RM Length L Ch R = 1 ,3000    ,500,500,500
BEGIN DESCRIPTION:
SANFERNANDO097 6.0
END DESCRIPTION:
XS GIS Cut Line= 3
      2821205.64     10209553.11      2821696.82     10209617.61
      2822105.67     10209403.12
#Sta/Elev= 30
  4504.6 1269.17  4605.5 1264.73    4699 1261.97  4786.8 1256.89  4851.4  1254.8
  4901.8 1255.17  4968.6 1252.87  5000.9 1249.08    5008 1247.29  5008.3 1246.79
    5012 1247.29  5018.1 1249.95  5023.7  1249.6  5040.1 1252.59  5055.2  1253.7
  5144.7 1257.46  5188.9 1260.16    5202 1262.34  5238.6 1263.66  5247.2 1265.53
    5255 1265.25  5269.7 1268.41  5292.3 1269.05  5299.1 1270.89  5337.5  1273.5
  5348.9 1275.76  5381.7 1279.23  5409.4  1283.5  5416.5  1285.6  5461.7    1290
#Mann= 6 ,-1 , 0
  4504.6     .05       0  4786.8     .12       0  4901.8     .05       0
  5000.9     .12       0    5008     .05       0    5012     .12       0
Bank Sta=5008,5012
XS Rating Curve= 0 ,0
Exp/Cntr=0.3,0.1

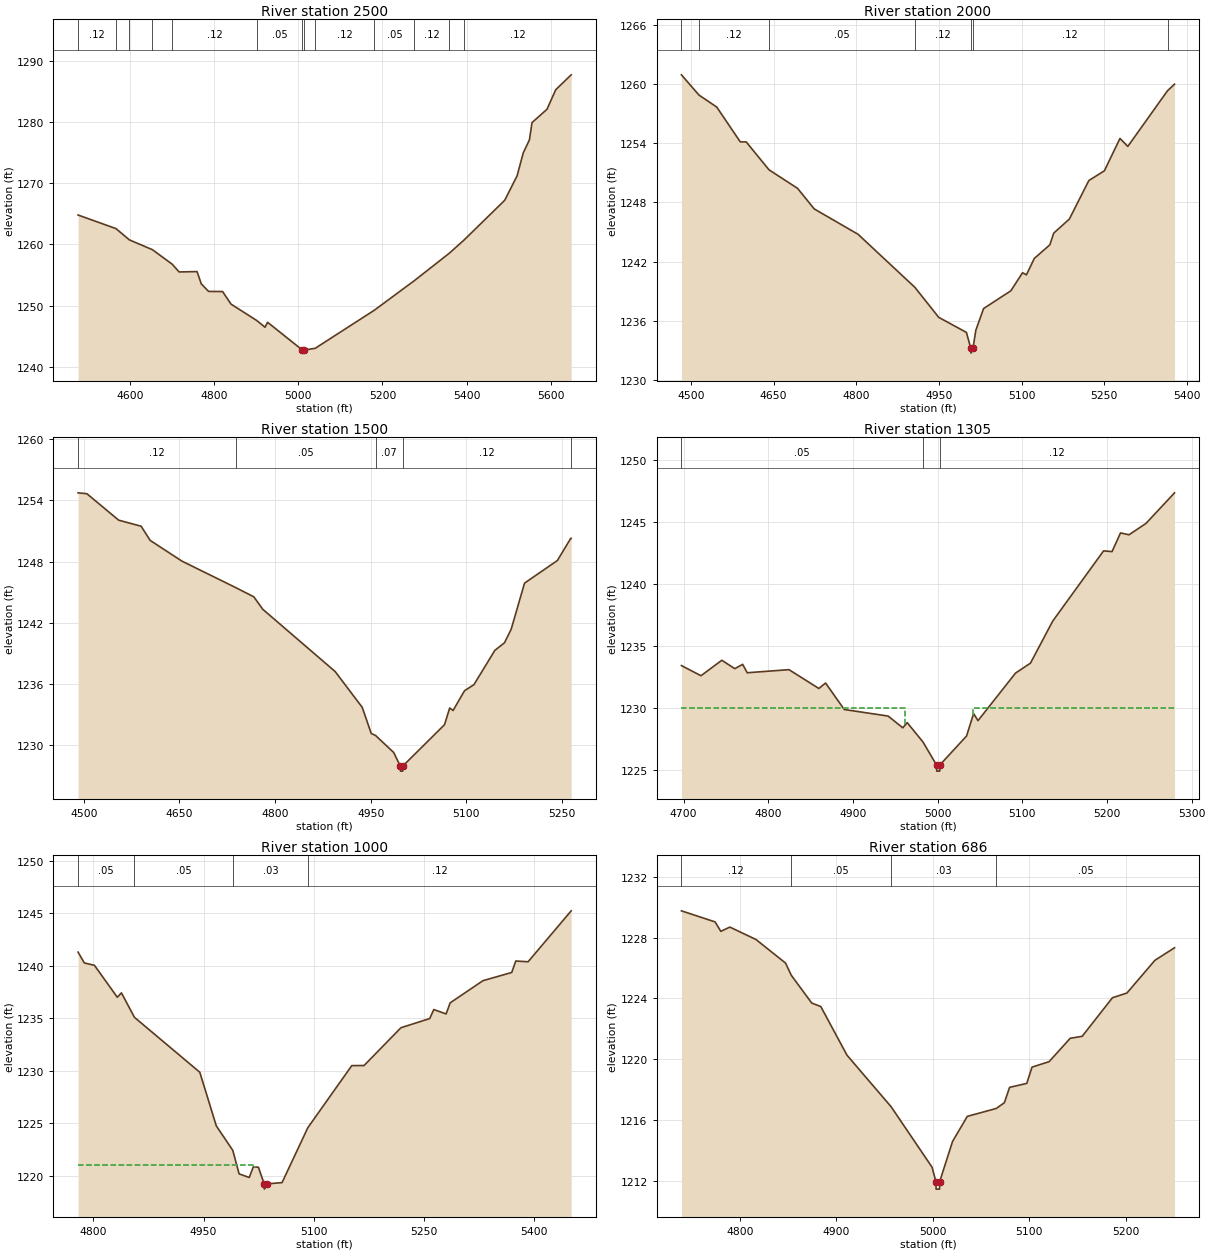
Type RM Length L Ch R = 1 ,2500    ,500,500,500
BEGIN DESCRIPTION:
SANFERNANDO097 5.0
END DESCRIPTION:
XS GIS Cut Line= 3
       2821355.7     10210153.11      2821873.85     10210077.74
       2822255.7     10209553.09
#Sta/Elev= 30
  4476.4 1264.81  4566.6 1262.59  4598.4 1260.75  4653.1 1259.15  4700.2 1256.78
  4716.7 1255.51  4759.3 1255.57  4769.4 1253.56  4786.8 1252.33    4820 1252.31
  4840.2 1250.25    4901 1247.59    4921 1246.48    4927 1247.29  5009.8 1242.75
    5010 1242.25  5013.8 1242.75  5040.3 1243.04  5180.9 1249.26    5276 1254.09
  5359.3 1258.58  5393.9 1260.71  5490.9 1267.22  5520.2  1271.2  5534.9 1274.95
  5549.6 1277.09  5555.8 1279.91  5591.3 1282.08  5612.2 1285.28  5648.9 1287.71
#Mann= 13 ,-1 , 0
  4476.4     .12       0  4566.6     .05       0  4598.4     .12       0
  4653.1     .05       0  4700.2     .12       0    4901     .05       0
  5009.8     .05       0  5013.8     .05       0  5040.3     .12       0
  5180.9     .05       0    5276     .12       0  5359.3     .05       0
  5393.9     .12       0
Bank Sta=5009.8,5013.8
XS Rating Curve= 0 ,0
Exp/Cntr=0.3,0.1

Type RM Length L Ch R = 1 ,2000    ,500,500,500
BEGIN DESCRIPTION:
SANFERNANDO097 4.0
END DESCRIPTION:
XS GIS Cut Line= 3
      2821405.71     10210353.12      2821889.75     10210535.05
      2822155.69     10210803.11
#Sta/Elev= 30
  4482.9 1260.93  4514.7 1258.88    4547 1257.66  4589.7 1254.13  4600.4 1254.13
  4641.8  1251.3  4693.6 1249.42  4723.9 1247.33  4803.4 1244.76  4906.5 1239.38
  4949.7 1236.34    5000 1234.81  5007.9 1233.21  5008.2 1232.71  5011.9 1233.21
    5017 1235.02  5031.1 1237.23  5080.6 1239.03  5101.8 1240.86  5108.9 1240.65
  5123.1 1242.31  5151.3 1243.69  5158.4 1244.88  5186.7  1246.3  5222.1 1250.21
  5250.3  1251.2  5278.6 1254.48  5292.8 1253.67  5364.9 1259.32  5377.6 1259.98
#Mann= 7 ,-1 , 0
  4482.9     .05       0  4514.7     .12       0  4641.8     .05       0
  4906.5     .12       0  5007.9     .07       0  5011.9     .12       0
  5364.9     .05       0
Bank Sta=5007.9,5011.9
XS Rating Curve= 0 ,0
Exp/Cntr=0.3,0.1

Type RM Length L Ch R = 1 ,1500    ,195,195,195
BEGIN DESCRIPTION:
SANFERNANDO097 3.0
END DESCRIPTION:
XS GIS Cut Line= 3
      2821355.72     10210553.14       2821702.7     10210925.55
      2821955.67     10211003.11
#Sta/Elev= 30
    4491 1254.75  4504.9 1254.66  4554.7 1252.07  4589.9 1251.48  4604.1 1250.09
  4653.9 1248.06  4738.1 1245.47  4766.7 1244.56  4780.9 1243.33  4894.3 1237.24
  4936.8 1233.73  4950.9 1231.17  4957.8 1230.97  4986.1 1229.31  4996.5 1227.98
  4996.8 1227.48  5000.3 1227.48  5000.5 1227.98  5065.9 1232.03    5074 1233.67
  5079.3 1233.42  5097.3 1235.36    5112 1235.95  5144.8 1239.31    5160 1240.06
  5170.5 1241.39  5191.4  1245.9    5243 1248.12  5263.9 1250.29  5264.6 1250.29
#Mann= 5 ,-1 , 0
    4491     .12       0  4738.1     .05       0  4957.8     .07       0
  5000.5     .12       0  5263.9     .12       0
Bank Sta=4996.5,5000.5
XS Rating Curve= 0 ,0
Exp/Cntr=0.3,0.1

Type RM Length L Ch R = 1 ,1305    ,305,305,305
BEGIN DESCRIPTION:
Mapping XS 4668342e
END DESCRIPTION:
XS GIS Cut Line= 4
      2821376.84     10211020.72      2821580.02     10211098.87
      2821751.89      10211057.2      2821939.37     10211067.62
#Sta/Elev= 30
  4697.5 1233.42  4720.6  1232.6  4745.2 1233.85  4760.5 1233.17  4769.8 1233.52
  4775.2 1232.84  4824.5 1233.09  4859.8 1231.57  4867.7 1232.01  4889.8 1229.87
  4941.6 1229.34  4958.9 1228.39  4964.1 1228.81  4982.8 1227.24  4998.7 1225.39
    4999 1224.89  5002.5 1224.89  5002.7 1225.39  5034.2 1227.73  5042.5 1229.54
  5047.7 1228.97    5092 1232.81  5109.7 1233.62  5135.9 1237.01    5196 1242.69
    5206 1242.63    5216 1244.14    5226 1243.99  5246.1 1244.91  5279.8 1247.38
#Mann= 3 ,-1 , 0
  4697.5     .05       0  4982.8     .07       0  5002.7     .12       0
#XS Ineff= 2 , 0
         4960.97 1229.96 5042.16         1230.02
Permanent Ineff=
       F       F
Bank Sta=4998.7,5002.7
XS Rating Curve= 0 ,0
Exp/Cntr=0.3,0.1

Type RM Length L Ch R = 1 ,1000    ,314,314,314
BEGIN DESCRIPTION:
SANFERNANDO097 2.0
END DESCRIPTION:
XS GIS Cut Line= 3
      2821355.65     10211403.13      2821553.59     10211305.49
      2821955.72     10211103.09
#Sta/Elev= 30
  4779.3  1241.3  4787.8 1240.27  4801.6 1240.04  4832.7    1237  4838.3 1237.42
    4856 1235.09  4944.9 1229.86  4967.4 1224.75  4989.8 1222.42  4998.4 1220.18
  5012.2 1219.84  5017.8 1220.86  5024.7 1220.81  5032.5 1219.23  5032.8 1218.73
  5036.5 1219.23  5056.8 1219.35  5091.9 1224.58  5151.7 1230.49  5168.4  1230.5
  5218.6  1234.1  5257.7 1234.97  5263.3 1235.83    5280 1235.41  5285.6 1236.47
  5330.2 1238.58  5369.3 1239.36  5374.8 1240.45  5391.6 1240.38  5450.2 1245.23
#Mann= 4 ,-1 , 0
  4779.3     .05       0    4856     .05       0  4989.8     .03       0
  5091.9     .12       0
#XS Ineff= 2 , 0
         5019.75 1221.06
Permanent Ineff=
       F       F
Bank Sta=5032.5,5036.5
XS Rating Curve= 0 ,0
Exp/Cntr=0.5,0.3

Type RM Length L Ch R = 1 ,686     ,157,157,157
BEGIN DESCRIPTION:
Mapping XS e75d9594
END DESCRIPTION:
XS GIS Cut Line= 3
      2821521.76     10211677.09      2821775.27     10211517.34
      2821861.39     10211324.44
#Sta/Elev= 30
  4739.5 1229.76  4774.4 1229.03  4780.3 1228.41  4789.7 1228.69  4816.8 1227.87
  4847.4 1226.32  4853.3 1225.52  4874.5 1223.69  4883.9 1223.46    4911 1220.26
  4956.8 1216.86  4999.2 1212.88  5003.1 1211.94  5003.4 1211.44  5006.9 1211.44
  5007.1 1211.94  5020.4 1214.58  5035.7 1216.23  5065.7 1216.75  5074.1 1217.13
  5079.5 1218.14  5097.3  1218.4  5102.7 1219.47  5120.4 1219.83  5142.3 1221.37
  5154.7  1221.5  5186.1 1224.04  5201.1 1224.35    5230  1226.5  5250.4 1227.33
#Mann= 4 ,-1 , 0
  4739.5     .12       0  4853.3     .05       0  4956.8     .03       0
  5065.7     .05       0
Bank Sta=5003.1,5007.1
XS Rating Curve= 0 ,0
Exp/Cntr=0.3,0.1

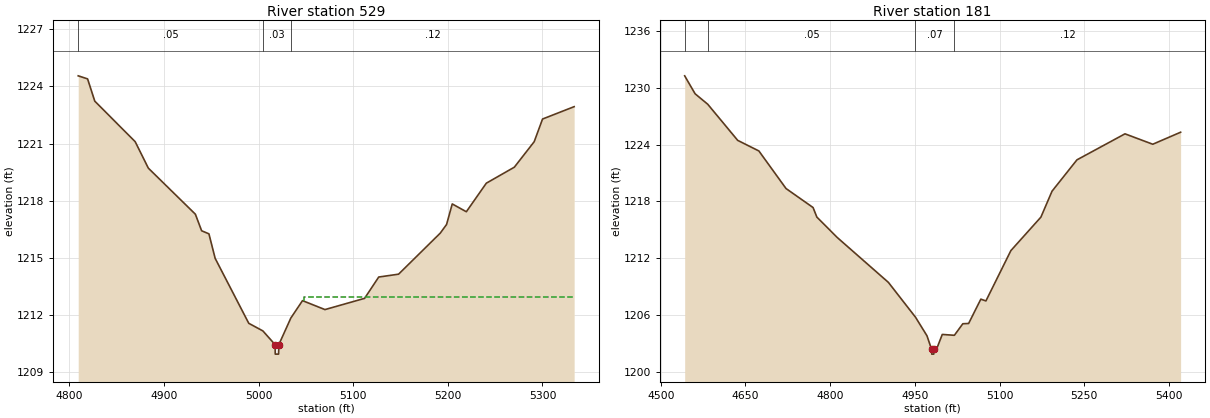
Type RM Length L Ch R = 1 ,529     ,348,348,348
BEGIN DESCRIPTION:
Mapping XS 8c44f116
END DESCRIPTION:
XS GIS Cut Line= 3
       2821699.8     10211791.58       2821819.6     10211687.41
      2822026.96     10211386.73
#Sta/Elev= 30
  4809.5 1224.56  4819.4  1224.4    4827 1223.23  4869.7  1221.1  4883.6 1219.71
  4933.3 1217.29  4939.9 1216.42  4947.6 1216.26  4954.2 1214.97  4989.7 1211.56
  5004.6 1211.16  5017.5 1210.44  5017.7 1209.94  5021.2 1209.94  5021.5 1210.44
  5034.2 1211.84  5046.5 1212.75  5070.2 1212.28  5112.1 1212.87    5127 1213.99
    5148 1214.14  5192.1  1216.3  5198.7 1216.75  5204.7 1217.83  5219.6 1217.42
  5240.7 1218.92  5270.3 1219.76  5291.3  1221.1  5300.1 1222.29  5333.5 1222.94
#Mann= 3 ,-1 , 0
  4809.5     .05       0  5004.6     .03       0  5034.2     .12       0
#XS Ineff= 2 , 0
                         5048.28         1212.94
Permanent Ineff=
       F       F
Bank Sta=5017.5,5021.5
XS Rating Curve= 0 ,0
Exp/Cntr=0.3,0.1

Type RM Length L Ch R = 1 ,181     ,0,0,0
BEGIN DESCRIPTION:
SANFERNANDO097 1.0
END DESCRIPTION:
XS GIS Cut Line= 3
      2821667.61     10211888.87       2822113.5       10211786.
      2822257.09     10211390.56
#Sta/Elev= 30
  4542.4 1231.26  4560.9 1229.36  4583.2 1228.26  4636.3 1224.44  4673.8 1223.32
  4721.9 1219.35  4769.8 1217.34  4776.5 1216.33  4812.5 1214.18  4903.2 1209.43
  4951.1 1205.76  4971.5 1203.79  4979.7 1202.35    4980 1201.85  4983.5 1201.85
  4983.7 1202.35  4988.7 1202.41  4998.6 1203.93    5020 1203.84    5035 1205.06
  5045.3 1205.09  5066.9 1207.66  5075.9 1207.47  5120.1 1212.79  5173.3 1216.33
    5193 1219.07  5237.1 1222.38  5322.2 1225.13  5371.4 1224.03  5420.7  1225.3
#Mann= 4 ,-1 , 0
  4542.4     .12       0  4583.2     .05       0  4951.1     .07       0
    5020     .12       0
Bank Sta=4979.7,4983.7
XS Rating Curve= 0 ,0
Exp/Cntr=0.3,0.1

Chan Stop Cuts=-1
Use User Specified Reach Order=0
Composite Channel Slope=5