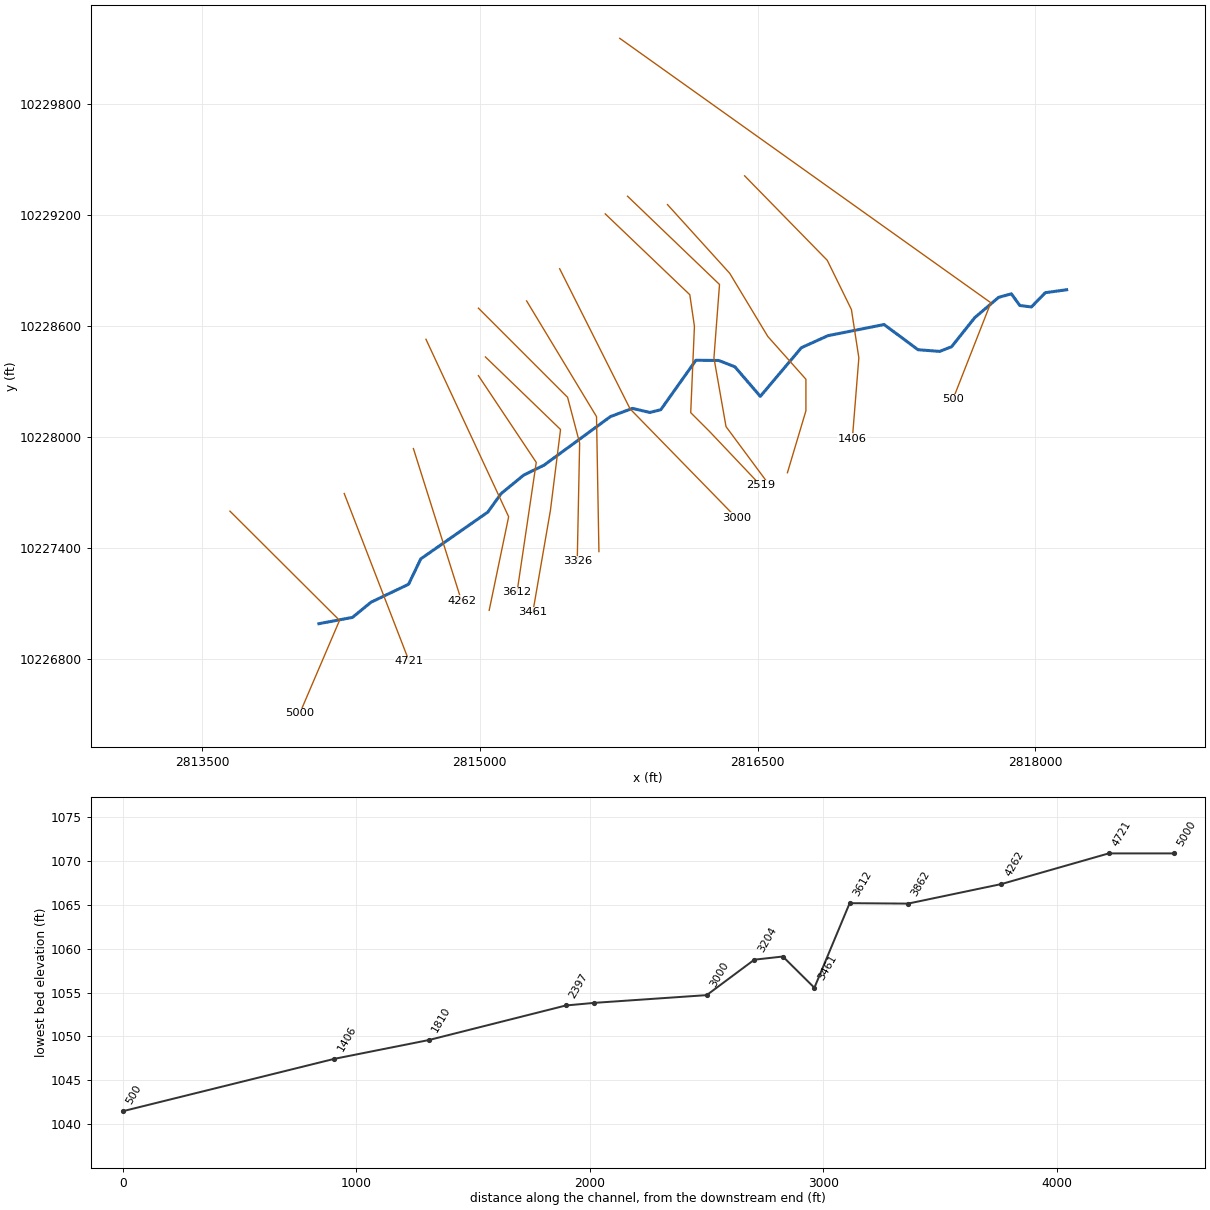
--- SANFERNANDO099.prj (project) ---

Proj Title=SANFERNANDO099 Base Level Engineering
Current Plan=p01
Default Exp/Contr=0.3,0.1
English Units
Geom File=g01
Flow File=f01
Plan File=p01
BEGIN DESCRIPTION:
SANFERNANDO099
END DESCRIPTION:

--- SANFERNANDO099.p01 (plan) ---

Plan Title=Multiple Run
Short Identifier=Multiple
Geom File=g01
Flow File=f01
Subcritical Flow
K Sum by GR= 0
Std Step Tol= 0.01
Critical Tol= 0.01
Num of Std Step Trials= 20
Max Error Tol= 0.3
Flow Tol Ratio= 0.001
Split Flow NTrial= 30
Split Flow Tol= 0.02
Split Flow Ratio= 0.02
Log Output Level= 0
Friction Slope Method= 1
Unsteady Friction Slope Method= 2
Unsteady Bridges Friction Slope Method= 1
Parabolic Critical Depth
Global Vel Dist=  1 , 1 , 1
Global Log Level= 0
CheckData=True
Encroach Param= -1, 0, 0, 0
BEGIN DESCRIPTION:
Multiple Run
END DESCRIPTION:

--- SANFERNANDO099.f01 (steady flow) ---

Flow Title=Multiple
Number of Profiles=7
Profile Names=10-year,25-year,50-year,1pct_min,100-year,1pct_plu,500-year
River Rch & RM= SANFERNANDO099,Reach-1,5000
     374     599     777     524    1027    2013    1410
Boundary for River Rch & Prof#=SANFERNANDO099,Reach-1,1
Up Type=0
Dn Type=3
Dn Slope=0.005
Boundary for River Rch & Prof#=SANFERNANDO099,Reach-1,2
Up Type=0
Dn Type=3
Dn Slope=0.005
Boundary for River Rch & Prof#=SANFERNANDO099,Reach-1,3
Up Type=0
Dn Type=3
Dn Slope=0.005
Boundary for River Rch & Prof#=SANFERNANDO099,Reach-1,4
Up Type=0
Dn Type=3
Dn Slope=0.005
Boundary for River Rch & Prof#=SANFERNANDO099,Reach-1,5
Up Type=0
Dn Type=3
Dn Slope=0.005
Boundary for River Rch & Prof#=SANFERNANDO099,Reach-1,6
Up Type=0
Dn Type=3
Dn Slope=0.005
Boundary for River Rch & Prof#=SANFERNANDO099,Reach-1,7
Up Type=0
Dn Type=3
Dn Slope=0.005

--- SANFERNANDO099.g01 (geometry) ---

Geom Title=Existing Conditions

River Reach=SANFERNANDO099,Reach-1
Reach XY= 30
      2814130.75     10226991.00      2814312.00     10227025.00
      2814412.00     10227107.00      2814615.00     10227204.00
      2814680.75     10227341.00      2815043.25     10227594.00
      2815115.00     10227694.00      2815237.25     10227794.00
      2815346.25     10227847.00      2815705.75     10228110.00
      2815824.50     10228154.00      2815918.25     10228132.00
      2815977.50     10228147.00      2816167.00     10228414.00
      2816290.00     10228413.00      2816377.50     10228379.00
      2816515.00     10228219.00      2816737.00     10228482.00
      2816880.75     10228547.00      2817183.75     10228607.00
      2817367.00     10228471.00      2817483.75     10228462.00
      2817548.25     10228487.00      2817673.25     10228644.00
      2817802.50     10228754.00      2817871.25     10228773.00
      2817917.00     10228710.00      2817979.50     10228702.00
      2818054.50     10228779.00      2818169.75     10228795.00

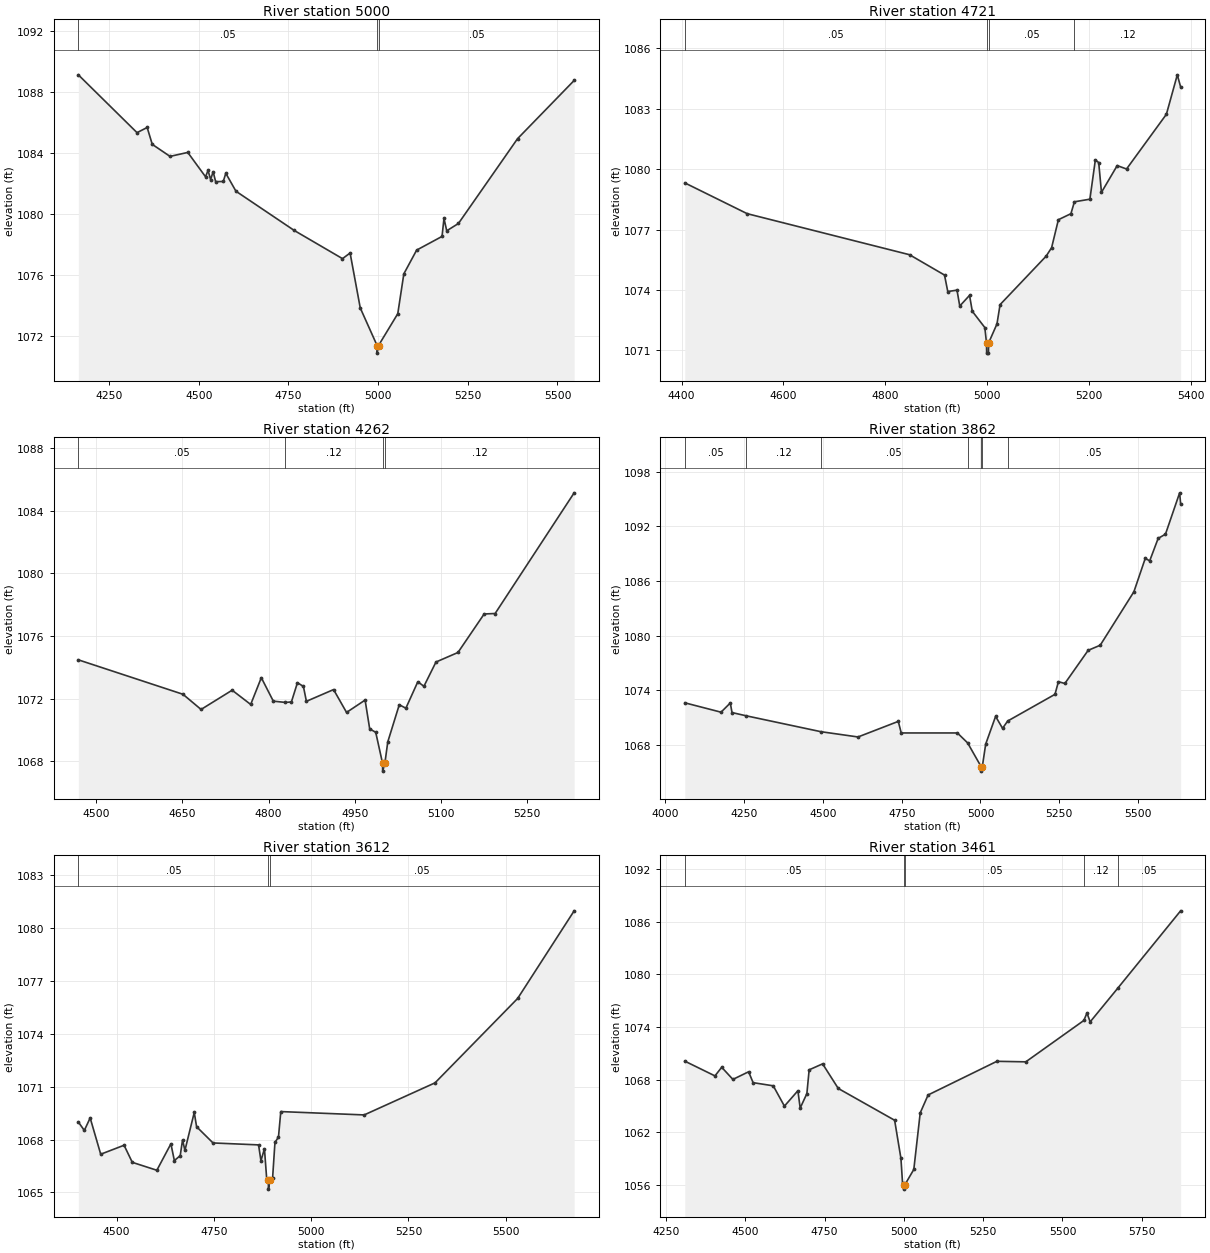
Type RM Length L Ch R = 1,5000,279,279,279
BEGIN DESCRIPTION:
SANFERNANDO099 10.0
END DESCRIPTION:
XS GIS Cut Line= 3
      2813650.08     10227598.93      2814242.00     10227008.99
      2814027.08     10226506.52
#Sta/Elev= 30
  4164.3 1089.15  4327.9 1085.35  4356.2 1085.69  4370.4 1084.58  4419.9 1083.79
  4469.4 1084.05  4518.9 1082.45  4525.9 1082.87  4533.0 1082.27  4540.1 1082.78
  4547.1 1082.13  4568.3 1082.14  4575.4 1082.68  4603.7 1081.50  4766.3 1078.92
  4900.7 1077.07  4921.9 1077.44  4950.2 1073.83  4997.1 1071.36  4997.3 1070.86
  5001.1 1071.36  5054.8 1073.45  5071.7 1076.07  5107.4 1077.63  5178.2 1078.53
  5183.6 1079.71  5191.3 1078.90  5223.9 1079.38  5388.6 1084.95  5546.5 1088.78
#Mann=3,-1,0
  4164.3    0.05       0  4997.1    0.05       0  5001.1    0.05       0
Bank Sta=4997.1,5001.1
Exp/Cntr=0.3,0.1

Type RM Length L Ch R = 1,4721,459,459,459
BEGIN DESCRIPTION:
Mapping XS d3c6d700
END DESCRIPTION:
XS GIS Cut Line= 2
      2814267.31     10227694.28      2814618.17     10226787.07
#Sta/Elev= 30
  4406.4 1079.32  4528.8 1077.79  4847.3 1075.75  4915.9 1074.74  4922.3 1073.92
  4940.4 1073.99  4945.8 1073.20  4965.0 1073.73  4970.4 1072.94  4995.0 1072.13
  4998.3 1071.36  4998.6 1070.86  5002.1 1070.86  5002.3 1071.36  5018.8 1072.31
  5024.9 1073.27  5115.3 1075.68  5126.0 1076.10  5139.3 1077.49  5163.9 1077.79
  5170.7 1078.38  5201.1 1078.51  5211.8 1080.46  5218.4 1080.33  5223.8 1078.85
  5254.7 1080.18  5273.0 1080.01  5351.2 1082.73  5372.6 1084.69  5379.1 1084.09
#Mann=4,-1,0
  4406.4    0.05       0  4998.3    0.05       0  5002.3    0.05       0
  5170.7    0.12       0
Bank Sta=4998.3,5002.3
Exp/Cntr=0.3,0.1

Type RM Length L Ch R = 1,4262,400,400,400
BEGIN DESCRIPTION:
Mapping XS 38be9c50
END DESCRIPTION:
XS GIS Cut Line= 2
      2814641.14     10227936.90      2814901.11     10227113.67
#Sta/Elev= 30
  4468.8 1074.48  4651.0 1072.28  4682.5 1071.31  4736.6 1072.54  4768.9 1071.63
  4787.4 1073.34  4808.3 1071.84  4829.4 1071.76  4839.8 1071.79  4850.3 1073.02
  4860.7 1072.78  4865.9 1071.83  4913.2 1072.58  4935.8 1071.12  4968.1 1071.91
  4976.1 1070.07  4986.6 1069.85  4998.5 1067.87  4998.7 1067.37  5002.5 1067.87
  5007.6 1069.24  5027.6 1071.61  5039.1 1071.39  5059.9 1073.08  5070.5 1072.79
  5091.5 1074.34  5129.8 1074.95  5175.4 1077.41  5194.5 1077.44  5332.1 1085.15
#Mann=4,-1,0
  4468.8    0.05       0  4829.4    0.12       0  4998.5    0.07       0
  5002.5    0.12       0
Bank Sta=4998.5,5002.5
Exp/Cntr=0.3,0.1

Type RM Length L Ch R = 1,3862,250,250,250
BEGIN DESCRIPTION:
Mapping XS 950e6a84
END DESCRIPTION:
XS GIS Cut Line= 3
      2814708.91     10228527.34      2815155.53     10227568.85
      2815050.41     10227063.30
#Sta/Elev= 30
  4061.5 1072.64  4176.5 1071.61  4205.9 1072.62  4211.4 1071.57  4255.5 1071.22
  4493.4 1069.47  4611.3 1068.89  4739.1 1070.60  4748.5 1069.33  4926.7 1069.33
  4959.2 1068.24  5001.9 1065.64  5002.2 1065.14  5005.9 1065.64  5016.6 1068.11
  5048.0 1071.15  5070.1 1069.84  5086.4 1070.64  5236.5 1073.57  5247.4 1074.96
  5267.8 1074.76  5341.8 1078.40  5380.1 1078.96  5487.0 1084.83  5523.1 1088.50
  5537.1 1088.22  5564.0 1090.69  5587.2 1091.15  5632.2 1095.69  5635.3 1094.49
#Mann=7,-1,0
  4061.5    0.05       0  4255.5    0.12       0  4493.4    0.05       0
  4959.2    0.12       0  5001.9    0.07       0  5005.9    0.12       0
  5086.4    0.05       0
Bank Sta=5001.9,5005.9
Exp/Cntr=0.3,0.1

Type RM Length L Ch R = 1,3612,151,151,151
BEGIN DESCRIPTION:
Mapping XS dacbd346
END DESCRIPTION:
XS GIS Cut Line= 3
      2814992.21     10228330.97      2815304.71     10227862.23
      2815200.61     10227159.55
#Sta/Elev= 30
  4401.9 1069.00  4417.3 1068.52  4432.3 1069.23  4459.4 1067.17  4519.4 1067.68
  4540.5 1066.71  4603.6 1066.26  4639.7 1067.76  4648.6 1066.81  4663.6 1067.09
  4669.6 1067.98  4675.7 1067.39  4699.7 1069.54  4705.7 1068.73  4747.9 1067.81
  4864.9 1067.70  4871.0 1066.80  4880.0 1067.48  4886.0 1065.71  4890.1 1065.69
  4890.3 1065.19  4894.1 1065.69  4901.0 1065.84  4907.0 1067.84  4916.0 1068.14
  4922.0 1069.59  5136.2 1069.40  5318.2 1071.22  5530.5 1076.01  5675.6 1080.98
#Mann=3,-1,0
  4401.9    0.05       0  4890.1    0.03       0  4894.1    0.05       0
Bank Sta=4890.1,4894.1
Exp/Cntr=0.3,0.1

Type RM Length L Ch R = 1,3461,135,135,135
BEGIN DESCRIPTION:
Mapping XS a9ed13e7
END DESCRIPTION:
XS GIS Cut Line= 4
      2815030.07     10228431.99      2815435.86     10228040.03
      2815381.35     10227603.98      2815286.00     10227051.97
#Sta/Elev= 30
  4308.9 1070.12  4404.0 1068.44  4425.3 1069.42  4460.6 1068.04  4510.2 1068.91
  4524.3 1067.67  4587.9 1067.31  4623.1 1065.00  4665.6 1066.75  4672.8 1064.78
  4693.9 1066.42  4701.1 1069.13  4743.5 1069.81  4792.9 1067.01  4970.7 1063.39
  4990.6 1059.04  4995.7 1056.20  4999.0 1056.05  4999.2 1055.55  5003.0 1056.05
  5031.2 1057.79  5051.4 1064.23  5076.3 1066.27  5293.2 1070.10  5384.4 1070.04
  5567.5 1074.75  5577.3 1075.60  5587.4 1074.59  5674.4 1078.42  5872.7 1087.23
#Mann=5,-1,0
  4308.9    0.05       0  4999.0    0.05       0  5003.0    0.05       0
  5567.5    0.12       0  5674.4    0.05       0
Bank Sta=4999,5003
Exp/Cntr=0.3,0.1

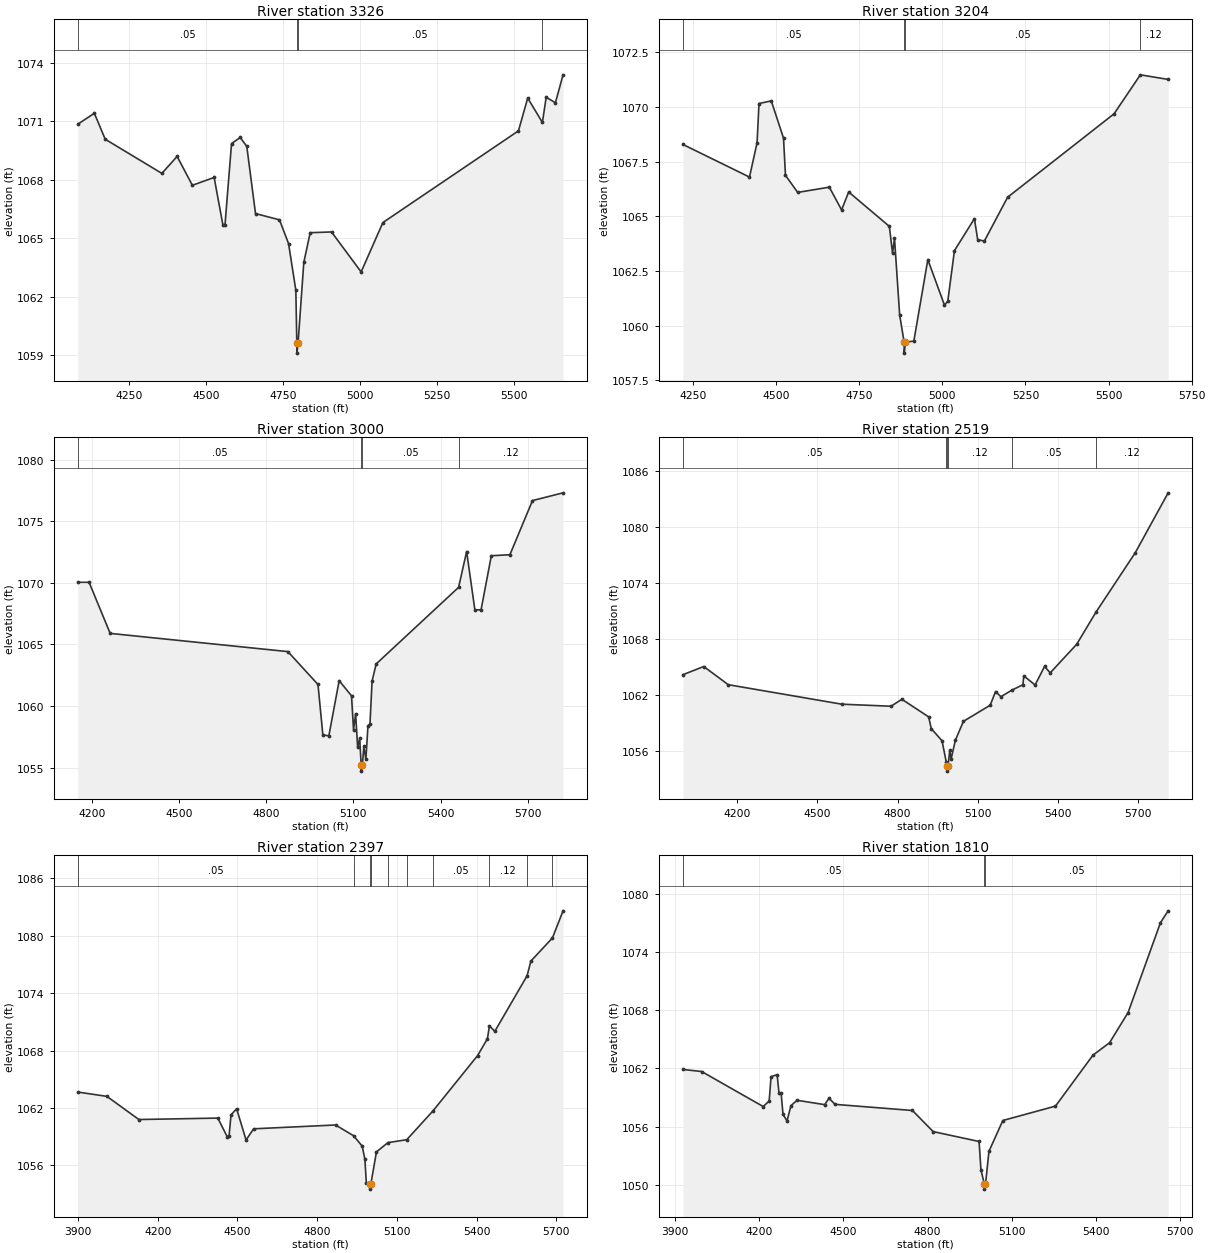
Type RM Length L Ch R = 1,3326,122,122,122
BEGIN DESCRIPTION:
Mapping XS 25539a7b
END DESCRIPTION:
XS GIS Cut Line= 4
      2814992.23     10228695.54      2815473.98     10228213.79
      2815539.08     10227966.39      2815526.06     10227328.34
#Sta/Elev= 30
  4083.7 1070.84  4137.4 1071.40  4172.7 1070.07  4356.6 1068.32  4406.1 1069.19
  4455.6 1067.71  4526.3 1068.11  4554.6 1065.69  4561.6 1065.69  4582.8 1069.85
  4611.1 1070.16  4632.3 1069.70  4660.6 1066.26  4738.4 1065.94  4767.9 1064.72
  4791.5 1062.33  4794.7 1059.61  4795.0 1059.11  4798.7 1059.61  4817.4 1063.76
  4838.1 1065.28  4907.3 1065.32  5003.5 1063.27  5074.1 1065.80  5514.2 1070.50
  5544.2 1072.18  5591.9 1070.93  5604.2 1072.22  5634.2 1071.94  5659.0 1073.37
#Mann=4,-1,0
  4083.7    0.05       0  4794.7    0.05       0  4798.7    0.05       0
  5591.9    0.12       0
Bank Sta=4794.7,4798.7
Exp/Cntr=0.3,0.1

Type RM Length L Ch R = 1,3204,204,204,204
BEGIN DESCRIPTION:
Mapping XS 4015a177
END DESCRIPTION:
XS GIS Cut Line= 3
      2815252.64     10228734.59      2815630.23     10228109.62
      2815643.25     10227380.41
#Sta/Elev= 30
  4219.8 1068.28  4420.1 1066.79  4442.9 1068.36  4448.7 1070.15  4485.6 1070.27
  4522.4 1068.57  4528.3 1066.87  4565.1 1066.09  4660.2 1066.33  4697.1 1065.29
  4718.4 1066.11  4840.7 1064.54  4850.4 1063.31  4856.2 1064.00  4871.7 1060.50
  4885.2 1059.25  4885.5 1058.75  4889.2 1059.25  4914.4 1059.30  4956.5 1063.02
  5006.5 1060.94  5016.5 1061.12  5036.5 1063.43  5096.5 1064.89  5106.5 1063.93
  5126.5 1063.87  5196.5 1065.87  5516.6 1069.68  5595.7 1071.46  5679.3 1071.25
#Mann=4,-1,0
  4219.8    0.05       0  4885.2    0.05       0  4889.2    0.05       0
  5595.7    0.12       0
Bank Sta=4885.2,4889.2
Exp/Cntr=0.3,0.1

Type RM Length L Ch R = 1,3000,481,481,481
BEGIN DESCRIPTION:
SANFERNANDO099 6.0
END DESCRIPTION:
XS GIS Cut Line= 3
      2815431.11     10228908.45      2815811.81     10228151.16
      2816385.02     10227563.81
#Sta/Elev= 30
  4152.4 1070.05  4191.2 1070.05  4263.7 1065.90  4874.7 1064.42  4978.1 1061.75
  4994.9 1057.65  5015.5 1057.58  5050.9 1062.06  5093.4 1060.83  5100.3 1058.07
  5107.5 1059.38  5114.5 1056.64  5121.6 1057.37  5126.6 1055.21  5126.9 1054.71
  5130.6 1055.21  5135.8 1056.72  5142.8 1055.66  5149.9 1058.37  5156.9 1058.55
  5164.1 1062.03  5178.2 1063.42  5461.5 1069.64  5489.2 1072.55  5517.5 1067.81
  5538.8 1067.82  5574.1 1072.21  5637.9 1072.29  5715.6 1076.69  5820.7 1077.32
#Mann=4,-1,0
  4152.4    0.05       0  5126.6    0.05       0  5130.6    0.05       0
  5461.5    0.12       0
Bank Sta=5126.6,5130.6
Exp/Cntr=0.3,0.1

Type RM Length L Ch R = 1,2519,122,122,122
BEGIN DESCRIPTION:
Mapping XS 19418526
END DESCRIPTION:
XS GIS Cut Line= 6
      2815677.43     10229204.80      2816134.09     10228768.22
      2816159.18     10228597.60      2816139.11     10228130.90
      2816244.49     10228025.52      2816515.46     10227739.49
#Sta/Elev= 30
  3997.4 1064.17  4075.3 1065.05  4167.1 1063.10  4591.4 1061.01  4775.8 1060.79
  4816.1 1061.54  4916.2 1059.65  4926.2 1058.38  4966.3 1057.09  4982.4 1054.76
  4984.3 1054.33  4984.5 1053.83  4988.3 1054.33  4995.3 1056.07  5000.3 1055.14
  5016.3 1057.15  5046.3 1059.17  5146.4 1060.90  5166.5 1062.37  5186.5 1061.81
  5226.3 1062.50  5268.8 1063.10  5271.9 1064.05  5314.3 1063.07  5349.6 1065.06
  5370.8 1064.37  5469.9 1067.44  5541.4 1070.86  5689.1 1077.27  5811.8 1083.68
#Mann=6,-1,0
  3997.4    0.05       0  4982.4    0.12       0  4984.3    0.07       0
  4988.3    0.12       0  5226.3    0.05       0  5541.4    0.12       0
Bank Sta=4984.3,4988.3
Exp/Cntr=0.3,0.1

Type RM Length L Ch R = 1,2397,587,587,587
BEGIN DESCRIPTION:
Mapping XS 7a667490
END DESCRIPTION:
XS GIS Cut Line= 5
      2815797.88     10229300.14      2816294.67     10228823.42
      2816264.56     10228426.98      2816329.80     10228055.62
      2816545.60     10227764.54
#Sta/Elev= 30
  3899.7 1063.67  4009.1 1063.22  4129.5 1060.80  4426.4 1060.95  4461.9 1059.00
  4468.9 1059.12  4476.1 1061.29  4497.2 1061.92  4532.7 1058.66  4561.0 1059.83
  4869.3 1060.23  4937.4 1059.10  4969.6 1058.02  4979.7 1056.64  4985.2 1054.16
  4997.9 1054.03  4998.1 1053.53  5001.9 1054.03  5023.2 1057.42  5066.5 1058.39
  5137.1 1058.69  5236.1 1061.71  5403.7 1067.48  5440.7 1069.24  5448.2 1070.59
  5468.4 1070.01  5589.9 1075.82  5604.1 1077.35  5685.3 1079.77  5725.2 1082.60
#Mann=10,-1,0
  3899.7    0.05       0  4937.4    0.12       0  4997.9    0.07       0
  5001.9    0.12       0  5066.5    0.05       0  5137.1    0.12       0
  5236.1    0.05       0  5448.2    0.12       0  5589.9    0.05       0
  5685.3    0.12       0
Bank Sta=4997.9,5001.9
Exp/Cntr=0.3,0.1

Type RM Length L Ch R = 1,1810,404,404,404
BEGIN DESCRIPTION:
Mapping XS cc8b5b94
END DESCRIPTION:
XS GIS Cut Line= 6
      2816013.64     10229255.00      2816349.87     10228883.64
      2816555.62     10228542.39      2816761.37     10228311.56
      2816761.37     10228140.94      2816661.51     10227806.40
#Sta/Elev= 30
  3928.7 1061.90  3995.4 1061.69  4214.5 1058.09  4236.0 1058.65  4242.7 1061.16
  4264.4 1061.36  4271.1 1059.45  4278.6 1059.46  4285.3 1057.28  4299.5 1056.61
  4313.7 1058.18  4335.3 1058.73  4433.7 1058.28  4449.2 1058.94  4470.6 1058.31
  4746.3 1057.68  4820.0 1055.51  4983.6 1054.49  4990.3 1051.57  5002.5 1050.09
  5002.8 1049.59  5006.5 1050.09  5018.8 1053.48  5068.3 1056.65  5255.8 1058.13
  5389.2 1063.37  5448.4 1064.65  5514.4 1067.76  5629.7 1077.00  5657.1 1078.22
#Mann=3,-1,0
  3928.7    0.05       0  5002.5    0.05       0  5006.5    0.05       0
Bank Sta=5002.5,5006.5
Exp/Cntr=0.3,0.1

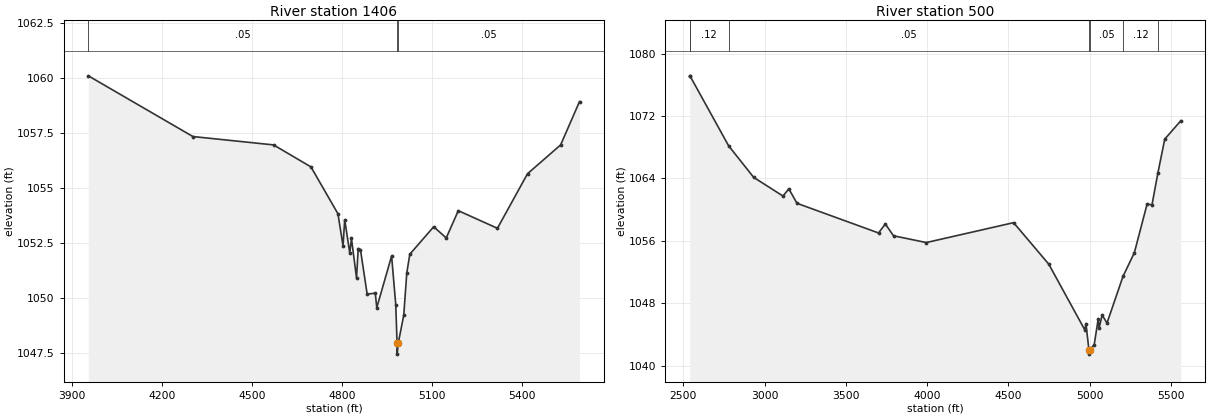
Type RM Length L Ch R = 1,1406,906,906,906
BEGIN DESCRIPTION:
Mapping XS 30cb77ef
END DESCRIPTION:
XS GIS Cut Line= 5
      2816430.17     10229410.55      2816876.79     10228953.89
      2817007.26     10228687.92      2817047.41     10228426.98
      2817012.28     10227990.40
#Sta/Elev= 30
  3955.6 1060.10  4304.1 1057.34  4572.9 1056.96  4697.5 1055.96  4787.5 1053.83
  4804.4 1052.37  4810.0 1053.56  4826.9 1052.05  4832.5 1052.71  4849.4 1050.91
  4855.0 1052.25  4862.5 1052.20  4884.8 1050.18  4911.9 1050.22  4916.9 1049.56
  4966.3 1051.91  4980.2 1049.69  4984.5 1047.95  4984.8 1047.45  4988.5 1047.95
  5006.8 1049.22  5016.9 1051.14  5027.0 1051.99  5106.6 1053.24  5148.4 1052.73
  5188.6 1053.97  5319.0 1053.17  5419.3 1055.65  5529.7 1056.96  5592.6 1058.93
#Mann=3,-1,0
  3955.6    0.05       0  4984.5    0.05       0  4988.5    0.05       0
Bank Sta=4984.5,4988.5
Exp/Cntr=0.3,0.1

Type RM Length L Ch R = 1,500,0,0,0
BEGIN DESCRIPTION:
SANFERNANDO099 1.0
END DESCRIPTION:
XS GIS Cut Line= 3
      2815755.69     10230153.11      2817760.27     10228724.78
      2817555.67     10228203.07
#Sta/Elev= 30
  2538.6 1077.15  2540.1 1077.15  2777.9 1068.19  2932.0 1064.14  3112.7 1061.74
  3148.4 1062.67  3198.8 1060.81  3700.4 1057.01  3742.2 1058.16  3792.6 1056.65
  3994.2 1055.78  4531.4 1058.33  4747.8 1053.01  4969.8 1044.57  4976.5 1045.38
  4995.1 1041.98  4995.4 1041.48  4999.1 1041.98  5027.4 1042.71  5051.9 1045.98
  5057.3 1044.83  5076.3 1046.48  5106.1 1045.46  5204.5 1051.45  5274.2 1054.47
  5352.9 1060.73  5382.7 1060.60  5419.2 1064.71  5461.4 1069.04  5560.4 1071.40
#Mann=7,-1,0
  2538.6    0.05       0  2540.1    0.12       0  2777.9    0.05       0
  4995.1    0.03       0  4999.1    0.05       0  5204.5    0.12       0
  5419.2    0.05       0
Bank Sta=4995.1,4999.1
Exp/Cntr=0.3,0.1

Chan Stop Cuts=-1