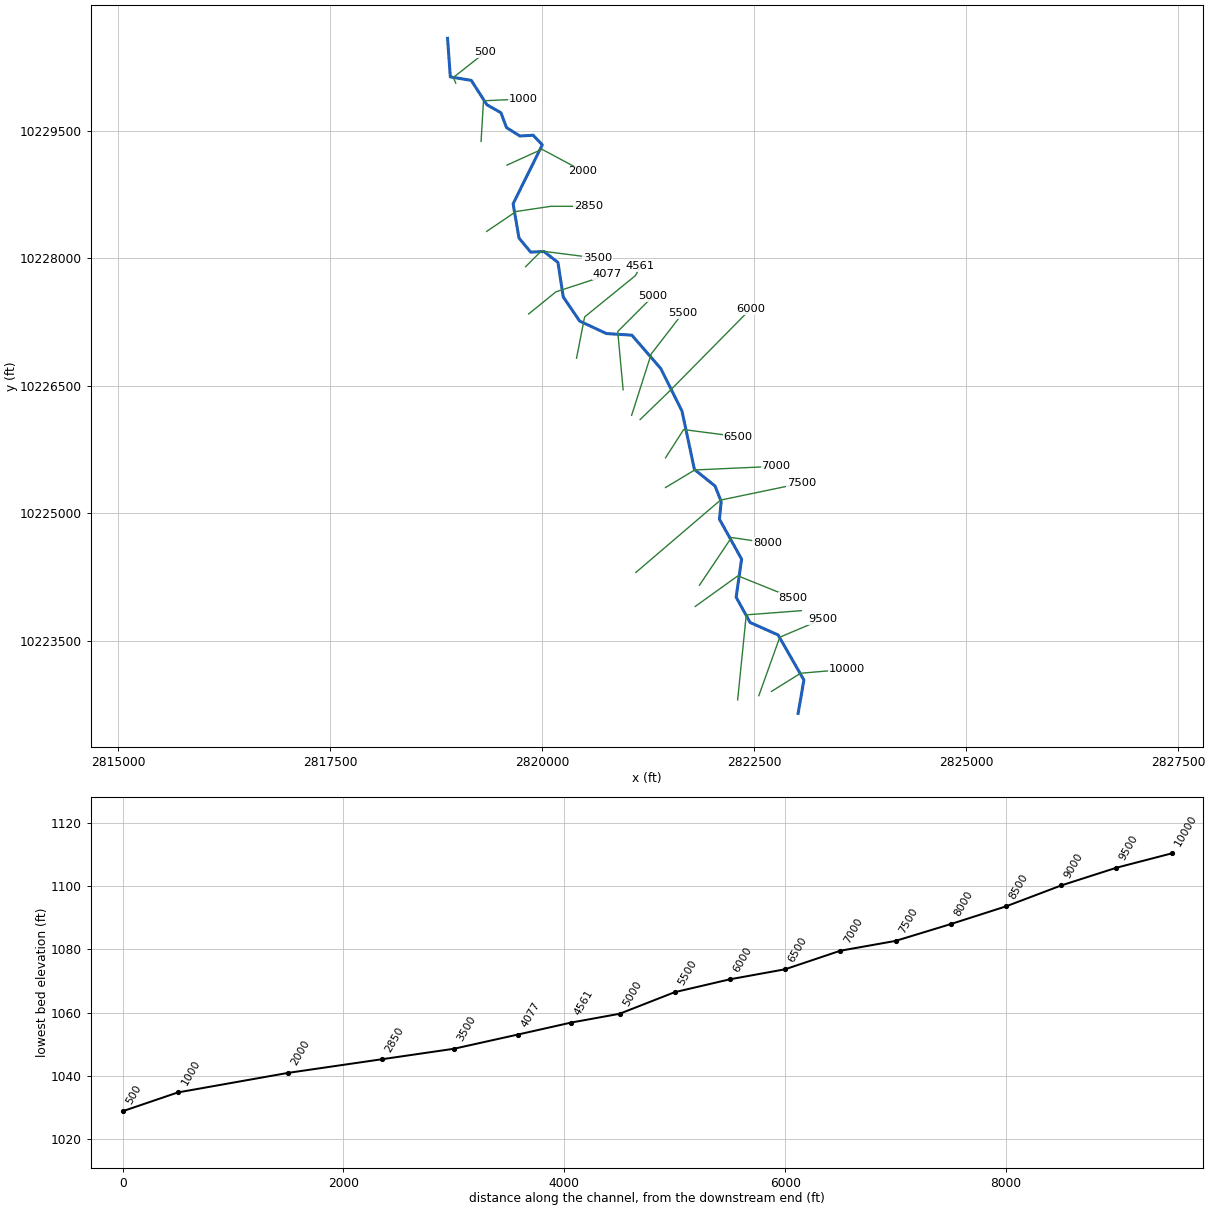
--- SANFERNANDO100.prj (project) ---

Proj Title=SANFERNANDO100 Base Level Engineering
Current Plan=p01
Default Exp/Contr=0.3,0.1
English Units
Geom File=g01
Flow File=f01
Plan File=p01
BEGIN DESCRIPTION:
SANFERNANDO100
END DESCRIPTION:

--- SANFERNANDO100.p01 (plan) ---

Plan Title=Multiple Run
Short Identifier=Multiple
Geom File=g01
Flow File=f01
Subcritical Flow
K Sum by GR= 0
Std Step Tol= 0.01
Critical Tol= 0.01
Num of Std Step Trials= 20
Max Error Tol= 0.3
Flow Tol Ratio= 0.001
Split Flow NTrial= 30
Split Flow Tol= 0.02
Split Flow Ratio= 0.02
Log Output Level= 0
Friction Slope Method= 1
Unsteady Friction Slope Method= 2
Unsteady Bridges Friction Slope Method= 1
Parabolic Critical Depth
Global Vel Dist=  1 , 1 , 1
Global Log Level= 0
CheckData=True
Encroach Param= -1, 0, 0, 0
BEGIN DESCRIPTION:
Multiple Run
END DESCRIPTION:

--- SANFERNANDO100.f01 (steady flow) ---

Flow Title=Multiple
Number of Profiles=7
Profile Names=10-year,25-year,50-year,1pct_min,100-year,1pct_plu,500-year
River Rch & RM= SANFERNANDO100,Reach-1,10000
     335     538     554     351     714    1451     965
River Rch & RM= SANFERNANDO100,Reach-1,500
     422     682     769     475    1003    2121    1352
Boundary for River Rch & Prof#=SANFERNANDO100,Reach-1,1
Up Type=0
Dn Type=3
Dn Slope=0.005
Boundary for River Rch & Prof#=SANFERNANDO100,Reach-1,2
Up Type=0
Dn Type=3
Dn Slope=0.005
Boundary for River Rch & Prof#=SANFERNANDO100,Reach-1,3
Up Type=0
Dn Type=3
Dn Slope=0.005
Boundary for River Rch & Prof#=SANFERNANDO100,Reach-1,4
Up Type=0
Dn Type=3
Dn Slope=0.005
Boundary for River Rch & Prof#=SANFERNANDO100,Reach-1,5
Up Type=0
Dn Type=3
Dn Slope=0.005
Boundary for River Rch & Prof#=SANFERNANDO100,Reach-1,6
Up Type=0
Dn Type=3
Dn Slope=0.005
Boundary for River Rch & Prof#=SANFERNANDO100,Reach-1,7
Up Type=0
Dn Type=3
Dn Slope=0.005

--- SANFERNANDO100.g01 (geometry) ---

Geom Title=Existing Conditions

River Reach=SANFERNANDO100,Reach-1
Reach XY= 30
      2823018.75     10222644.00      2823087.00     10223037.00
      2822783.25     10223567.00      2822452.75     10223714.00
      2822288.25     10224012.00      2822352.50     10224460.00
      2822091.25     10224931.00      2822111.75     10225139.00
      2822039.25     10225321.00      2821796.25     10225516.00
      2821649.50     10226204.00      2821399.50     10226704.00
      2821058.75     10227097.00      2820758.75     10227116.00
      2820443.25     10227263.00      2820249.50     10227547.00
      2820187.00     10227954.00      2820021.25     10228082.00
      2819865.00     10228075.00      2819727.50     10228241.00
      2819658.75     10228644.00      2820002.50     10229338.00
      2819894.50     10229451.00      2819738.25     10229442.00
      2819580.75     10229541.00      2819515.00     10229716.00
      2819349.50     10229810.00      2819165.00     10230097.00
      2818918.25     10230138.00      2818885.50     10230592.00

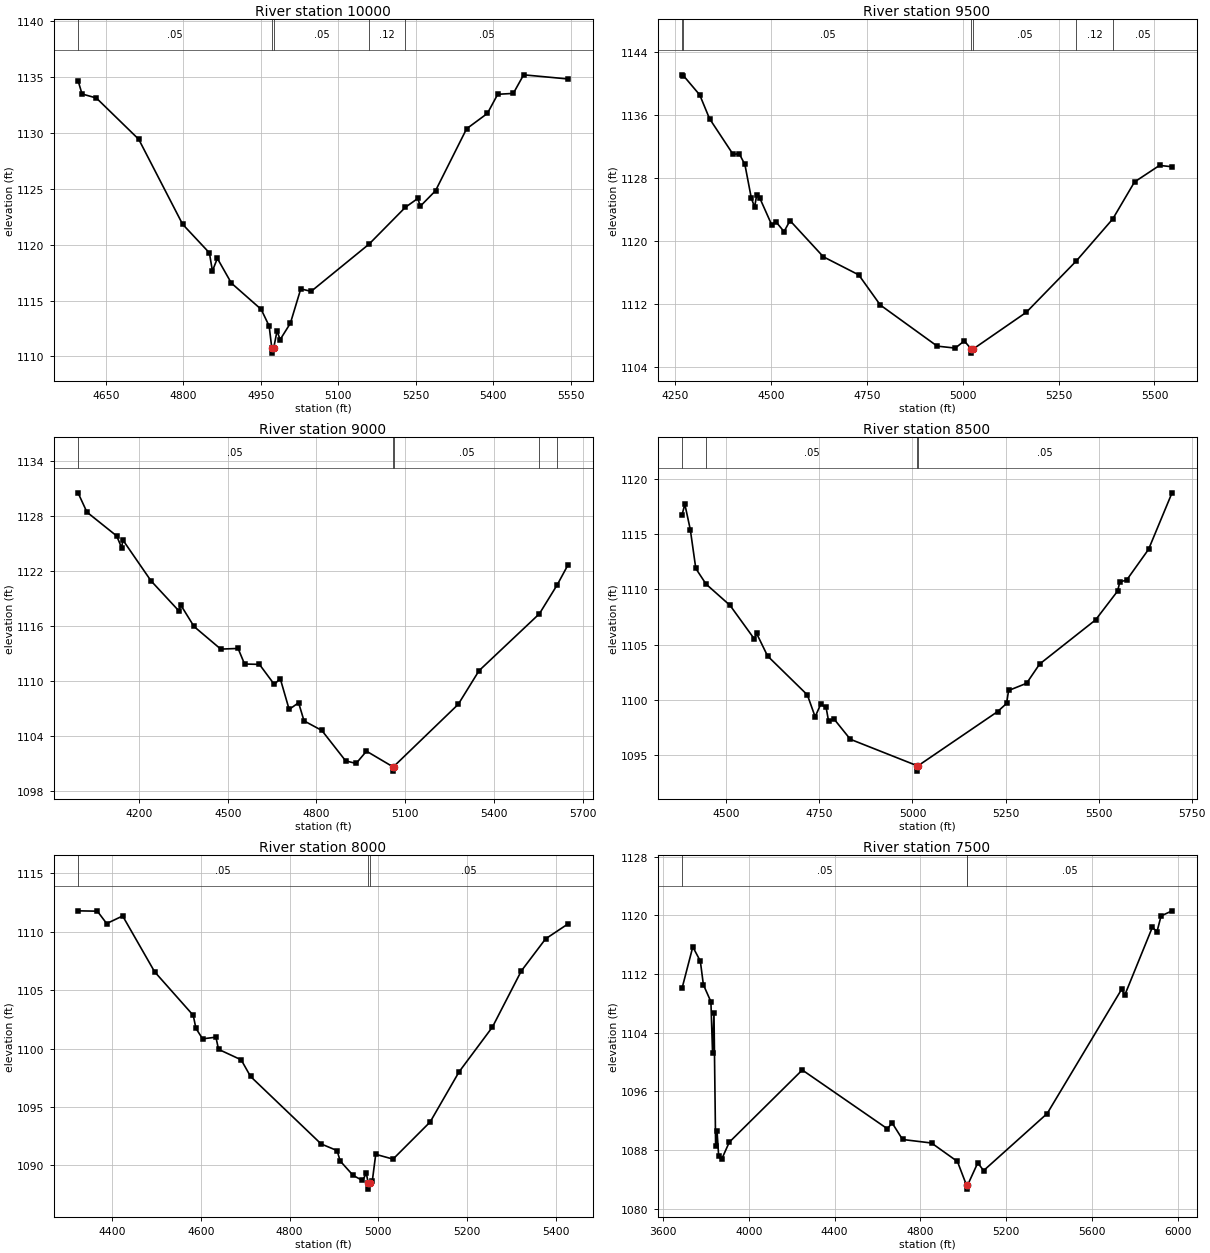
Type RM Length L Ch R = 1,10000,500,500,500
BEGIN DESCRIPTION:
SANFERNANDO100 20.0
END DESCRIPTION:
XS GIS Cut Line= 3
      2822705.66     10222903.10      2823048.40     10223116.61
      2823591.25     10223162.62
#Sta/Elev= 30
  4596.2 1134.66  4603.9 1133.46  4631.6 1133.10  4713.7 1129.41  4798.6 1121.82
  4850.5 1119.26  4856.4 1117.64  4865.9 1118.77  4893.0 1116.56  4950.8 1114.21
  4966.2 1112.72  4971.2 1110.80  4971.5 1110.30  4975.2 1110.80  4981.5 1112.29
  4987.4 1111.50  5007.3 1112.97  5027.4 1116.04  5047.5 1115.82  5159.6 1120.04
  5229.9 1123.33  5253.9 1124.12  5258.9 1123.43  5288.3 1124.81  5348.5 1130.35
  5388.7 1131.72  5408.7 1133.43  5438.9 1133.51  5458.9 1135.17  5544.8 1134.80
#Mann=5,-1,0
  4596.2    0.05       0  4971.2    0.03       0  4975.2    0.05       0
  5159.6    0.12       0  5229.9    0.05       0
Bank Sta=4971.2,4975.2
Exp/Cntr=0.3,0.1

Type RM Length L Ch R = 1,9500,500,500,500
BEGIN DESCRIPTION:
SANFERNANDO100 19.0
END DESCRIPTION:
XS GIS Cut Line= 3
      2822555.68     10222853.10      2822802.83     10223541.16
      2823305.69     10223753.11
#Sta/Elev= 30
  4268.9 1141.16  4272.2 1141.07  4315.0 1138.60  4340.4 1135.59  4401.9 1131.04
  4417.7 1131.14  4432.6 1129.76  4449.5 1125.45  4458.0 1124.34  4463.3 1125.86
  4470.8 1125.56  4502.7 1122.06  4513.3 1122.49  4534.6 1121.22  4550.2 1122.62
  4637.1 1118.02  4729.3 1115.72  4785.4 1111.89  4933.7 1106.66  4980.8 1106.41
  5004.3 1107.32  5022.8 1106.27  5023.0 1105.77  5026.8 1106.27  5165.9 1110.96
  5296.4 1117.50  5391.2 1122.83  5448.0 1127.54  5513.1 1129.64  5545.7 1129.47
#Mann=6,-1,0
  4268.9    0.12       0  4272.2    0.05       0  5022.8    0.05       0
  5026.8    0.05       0  5296.4    0.12       0  5391.2    0.05       0
Bank Sta=5022.8,5026.8
Exp/Cntr=0.3,0.1

Type RM Length L Ch R = 1,9000,500,500,500
BEGIN DESCRIPTION:
SANFERNANDO100 18.0
END DESCRIPTION:
XS GIS Cut Line= 3
      2822305.69     10222803.14      2822407.33     10223803.99
      2823055.67     10223853.11
#Sta/Elev= 30
  3994.0 1130.57  4024.1 1128.46  4124.6 1125.86  4141.1 1124.59  4146.1 1125.39
  4240.8 1120.95  4335.5 1117.65  4340.6 1118.35  4386.0 1115.97  4476.4 1113.50
  4535.0 1113.57  4556.9 1111.87  4607.1 1111.83  4657.4 1109.64  4677.5 1110.28
  4707.6 1106.91  4739.5 1107.64  4757.9 1105.66  4818.2 1104.61  4898.6 1101.29
  4934.0 1101.01  4969.0 1102.35  5057.0 1100.67  5057.3 1100.17  5061.0 1100.67
  5279.2 1107.47  5349.4 1111.14  5553.5 1117.36  5614.3 1120.55  5650.2 1122.70
#Mann=5,-1,0
  3994.0    0.05       0  5057.0    0.05       0  5061.0    0.05       0
  5553.5    0.12       0  5614.3    0.05       0
Bank Sta=5057,5061
Exp/Cntr=0.3,0.1

Type RM Length L Ch R = 1,8500,500,500,500
BEGIN DESCRIPTION:
SANFERNANDO100 17.0
END DESCRIPTION:
XS GIS Cut Line= 3
      2821805.67     10223903.10      2822308.86     10224263.62
      2822955.67     10224003.12
#Sta/Elev= 30
  4381.0 1116.74  4388.4 1117.69  4403.1 1115.40  4417.9 1111.88  4445.4 1110.47
  4510.0 1108.54  4575.1 1105.51  4581.2 1106.01  4610.7 1103.97  4717.6 1100.45
  4738.5 1098.47  4753.2 1099.59  4767.9 1099.33  4774.7 1098.06  4788.8 1098.29
  4833.0 1096.44  5011.7 1094.06  5012.0 1093.56  5015.7 1094.06  5228.6 1098.94
  5252.8 1099.68  5258.2 1100.85  5306.5 1101.50  5341.6 1103.24  5491.8 1107.23
  5550.9 1109.83  5557.2 1110.68  5575.1 1110.82  5634.2 1113.61  5697.3 1118.72
#Mann=4,-1,0
  4381.0    0.12       0  4445.4    0.05       0  5011.7    0.03       0
  5015.7    0.05       0
Bank Sta=5011.7,5015.7
Exp/Cntr=0.3,0.1

Type RM Length L Ch R = 1,8000,500,500,500
BEGIN DESCRIPTION:
SANFERNANDO100 16.0
END DESCRIPTION:
XS GIS Cut Line= 3
      2821855.68     10224153.11      2822233.05     10224714.57
      2822655.70     10224653.11
#Sta/Elev= 30
  4323.5 1111.80  4367.0 1111.77  4388.0 1110.71  4424.0 1111.36  4496.0 1106.58
  4583.0 1102.85  4589.0 1101.74  4604.0 1100.84  4634.0 1100.98  4640.0 1099.94
  4691.0 1099.04  4712.0 1097.62  4871.0 1091.84  4907.0 1091.27  4913.9 1090.38
  4943.0 1089.15  4964.0 1088.71  4973.0 1089.32  4977.0 1088.47  4977.3 1087.97
  4981.0 1088.47  4986.2 1088.63  4994.0 1090.95  5033.0 1090.54  5116.6 1093.72
  5181.7 1098.01  5256.9 1101.85  5321.9 1106.65  5376.6 1109.40  5427.1 1110.68
#Mann=3,-1,0
  4323.5    0.05       0  4977.0    0.05       0  4981.0    0.05       0
Bank Sta=4977,4981
Exp/Cntr=0.3,0.1

Type RM Length L Ch R = 1,7500,500,500,500
BEGIN DESCRIPTION:
SANFERNANDO100 15.0
END DESCRIPTION:
XS GIS Cut Line= 3
      2821105.67     10224303.10      2822102.54     10225154.70
      2823055.71     10225353.12
#Sta/Elev= 30
  3688.9 1110.06  3738.9 1115.69  3774.0 1113.76  3788.3 1110.53  3823.4 1108.21
  3831.1 1101.16  3837.7 1106.61  3845.4 1088.53  3852.0 1090.58  3859.6 1087.11
  3873.1 1086.70  3909.0 1089.05  4249.4 1098.90  4646.8 1090.87  4667.7 1091.71
  4717.1 1089.42  4852.1 1088.94  4972.9 1086.42  5015.6 1083.15  5015.9 1082.65
  5019.6 1083.15  5067.7 1086.23  5095.1 1085.18  5391.4 1092.96  5738.6 1109.91
  5753.4 1109.13  5881.6 1118.35  5903.6 1117.79  5922.5 1119.91  5973.6 1120.61
#Mann=3,-1,0
  3688.9    0.05       0  5015.6    0.03       0  5019.6    0.05       0
Bank Sta=5015.6,5019.6
Exp/Cntr=0.3,0.1

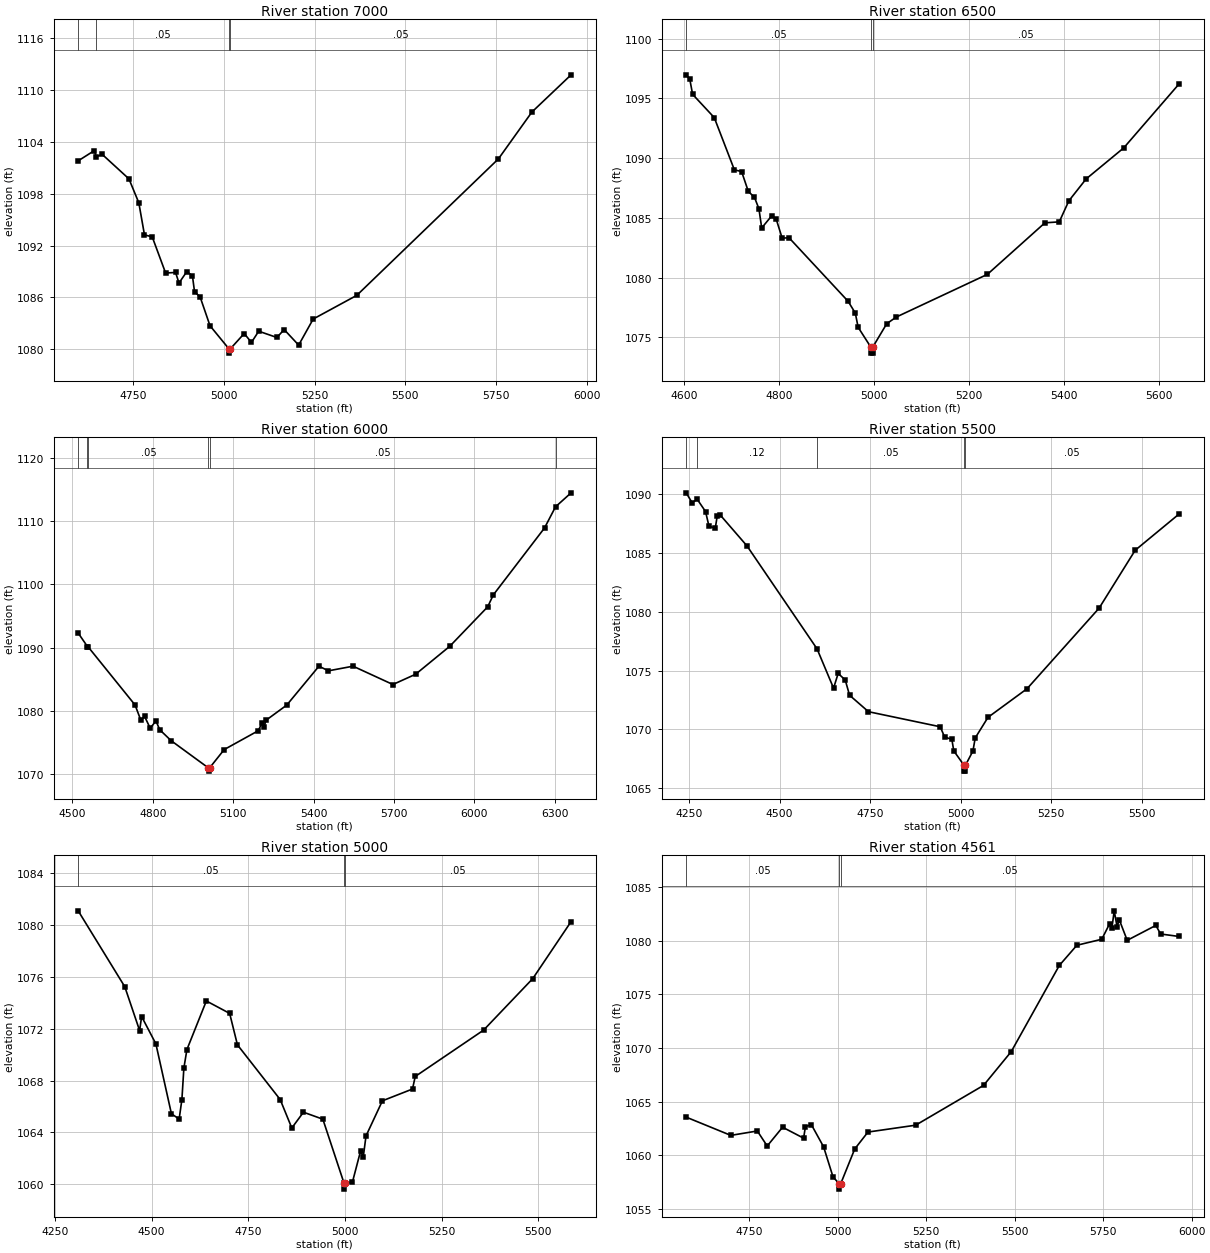
Type RM Length L Ch R = 1,7000,500,500,500
BEGIN DESCRIPTION:
SANFERNANDO100 14.0
END DESCRIPTION:
XS GIS Cut Line= 3
      2821455.66     10225303.09      2821799.68     10225509.91
      2822755.70     10225553.11
#Sta/Elev= 30
  4598.6 1101.82  4643.3 1103.01  4648.1 1102.28  4664.7 1102.57  4738.5 1099.73
  4765.7 1096.96  4781.3 1093.24  4802.6 1093.02  4839.5 1088.83  4867.0 1088.89
  4876.4 1087.67  4897.8 1088.98  4913.4 1088.52  4919.2 1086.67  4934.7 1086.05
  4961.9 1082.72  5014.0 1080.05  5014.3 1079.55  5018.0 1080.05  5056.1 1081.82
  5076.1 1080.79  5096.1 1082.09  5146.2 1081.36  5166.2 1082.28  5206.2 1080.48
  5246.3 1083.50  5366.4 1086.24  5756.8 1102.05  5849.0 1107.47  5957.0 1111.78
#Mann=4,-1,0
  4598.6    0.12       0  4648.1    0.05       0  5014.0    0.05       0
  5018.0    0.05       0
Bank Sta=5014,5018
Exp/Cntr=0.3,0.1

Type RM Length L Ch R = 1,6500,500,500,500
BEGIN DESCRIPTION:
SANFERNANDO100 13.0
END DESCRIPTION:
XS GIS Cut Line= 3
      2821455.70     10225653.13      2821668.86     10225985.55
      2822305.65     10225903.12
#Sta/Elev= 30
  4605.1 1096.97  4612.7 1096.60  4618.6 1095.34  4664.2 1093.39  4706.5 1089.02
  4721.7 1088.88  4735.8 1087.22  4748.8 1086.72  4758.1 1085.77  4764.0 1084.16
  4785.1 1085.18  4794.4 1084.91  4807.0 1083.31  4821.5 1083.34  4945.7 1078.03
  4960.9 1077.04  4966.9 1075.85  4993.6 1074.19  4993.8 1073.69  4997.3 1073.69
  4997.6 1074.19  5027.0 1076.15  5047.2 1076.71  5238.8 1080.28  5359.8 1084.59
  5390.0 1084.67  5410.2 1086.43  5446.5 1088.26  5525.7 1090.86  5642.1 1096.21
#Mann=3,-1,0
  4605.1    0.05       0  4993.6    0.03       0  4997.6    0.05       0
Bank Sta=4993.6,4997.6
Exp/Cntr=0.3,0.1

Type RM Length L Ch R = 1,6000,500,500,500
BEGIN DESCRIPTION:
SANFERNANDO100 12.0
END DESCRIPTION:
XS GIS Cut Line= 3
      2821155.69     10226103.12      2821499.53     10226435.17
      2822455.71     10227403.14
#Sta/Elev= 30
  4522.0 1092.31  4556.6 1090.18  4559.7 1090.10  4734.1 1080.96  4755.4 1078.59
  4769.6 1079.16  4790.7 1077.29  4812.0 1078.45  4826.2 1077.05  4868.6 1075.33
  5008.0 1071.02  5008.3 1070.52  5012.0 1071.02  5066.6 1073.92  5193.9 1076.90
  5207.9 1078.17  5215.0 1077.42  5222.1 1078.53  5299.9 1080.94  5420.1 1087.08
  5455.5 1086.35  5547.3 1087.08  5695.9 1084.19  5780.7 1085.81  5908.0 1090.22
  6049.5 1096.45  6070.6 1098.34  6261.6 1108.90  6302.5 1112.23  6360.6 1114.44
#Mann=6,-1,0
  4522.0    0.05       0  4556.6    0.12       0  4559.7    0.05       0
  5008.0    0.03       0  5012.0    0.05       0  6302.5    0.12       0
Bank Sta=5008,5012
Exp/Cntr=0.3,0.1

Type RM Length L Ch R = 1,5500,500,500,500
BEGIN DESCRIPTION:
SANFERNANDO100 11.0
END DESCRIPTION:
XS GIS Cut Line= 3
      2821055.69     10226153.13      2821286.71     10226875.38
      2821655.66     10227353.09
#Sta/Elev= 30
  4241.7 1090.10  4257.8 1089.27  4272.4 1089.54  4295.2 1088.51  4304.7 1087.26
  4322.1 1087.10  4327.3 1088.10  4336.2 1088.20  4409.7 1085.59  4603.3 1076.84
  4648.9 1073.50  4661.6 1074.75  4681.1 1074.20  4693.1 1072.90  4745.4 1071.50
  4943.6 1070.22  4955.6 1069.36  4975.8 1069.14  4981.1 1068.17  5009.3 1066.95
  5009.5 1066.45  5013.0 1066.45  5013.3 1066.95  5034.0 1068.16  5040.3 1069.27
  5075.6 1071.02  5183.4 1073.45  5382.6 1080.30  5482.3 1085.22  5603.6 1088.30
#Mann=5,-1,0
  4241.7    0.05       0  4272.4    0.12       0  4603.3    0.05       0
  5009.3    0.05       0  5013.3    0.05       0
Bank Sta=5009.3,5013.3
Exp/Cntr=0.3,0.1

Type RM Length L Ch R = 1,5000,439,439,439
BEGIN DESCRIPTION:
SANFERNANDO100 10.0
END DESCRIPTION:
XS GIS Cut Line= 3
      2820955.69     10226453.09      2820891.87     10227140.13
      2821305.66     10227553.09
#Sta/Elev= 30
  4310.0 1081.11  4430.5 1075.25  4468.9 1071.86  4474.0 1072.95  4510.9 1070.84
  4551.1 1065.44  4571.1 1065.03  4578.2 1066.54  4583.3 1068.97  4591.2 1070.40
  4641.4 1074.15  4701.7 1073.19  4721.8 1070.76  4832.3 1066.54  4862.4 1064.34
  4892.5 1065.56  4942.7 1065.02  4997.0 1060.12  4997.2 1059.62  5001.0 1060.12
  5019.0 1060.14  5040.2 1062.56  5047.2 1062.11  5054.3 1063.73  5096.7 1066.44
  5174.5 1067.35  5181.6 1068.32  5358.4 1071.90  5485.6 1075.88  5584.6 1080.28
#Mann=3,-1,0
  4310.0    0.05       0  4997.0    0.03       0  5001.0    0.05       0
Bank Sta=4997,5001
Exp/Cntr=0.3,0.1

Type RM Length L Ch R = 1,4561,484,484,484
BEGIN DESCRIPTION:
Mapping XS 08d1268a
END DESCRIPTION:
XS GIS Cut Line= 4
      2820406.09     10226825.87      2820501.57     10227311.98
      2821100.53     10227798.09      2821160.22     10227908.94
#Sta/Elev= 30
  4571.9 1063.55  4698.0 1061.85  4772.9 1062.26  4800.8 1060.86  4844.3 1062.61
  4903.7 1061.59  4908.8 1062.67  4925.8 1062.84  4960.2 1060.78  4986.9 1057.97
  5004.5 1057.34  5004.8 1056.84  5008.5 1057.34  5048.1 1060.58  5085.5 1062.16
  5220.3 1062.80  5412.1 1066.51  5490.4 1069.66  5626.2 1077.69  5675.8 1079.57
  5746.1 1080.13  5768.1 1081.56  5774.9 1081.21  5781.3 1082.78  5789.3 1081.31
  5795.7 1081.94  5818.0 1080.03  5898.9 1081.42  5912.5 1080.62  5964.6 1080.39
#Mann=3,-1,0
  4571.9    0.05       0  5004.5    0.05       0  5008.5    0.05       0
Bank Sta=5004.5,5008.5
Exp/Cntr=0.3,0.1

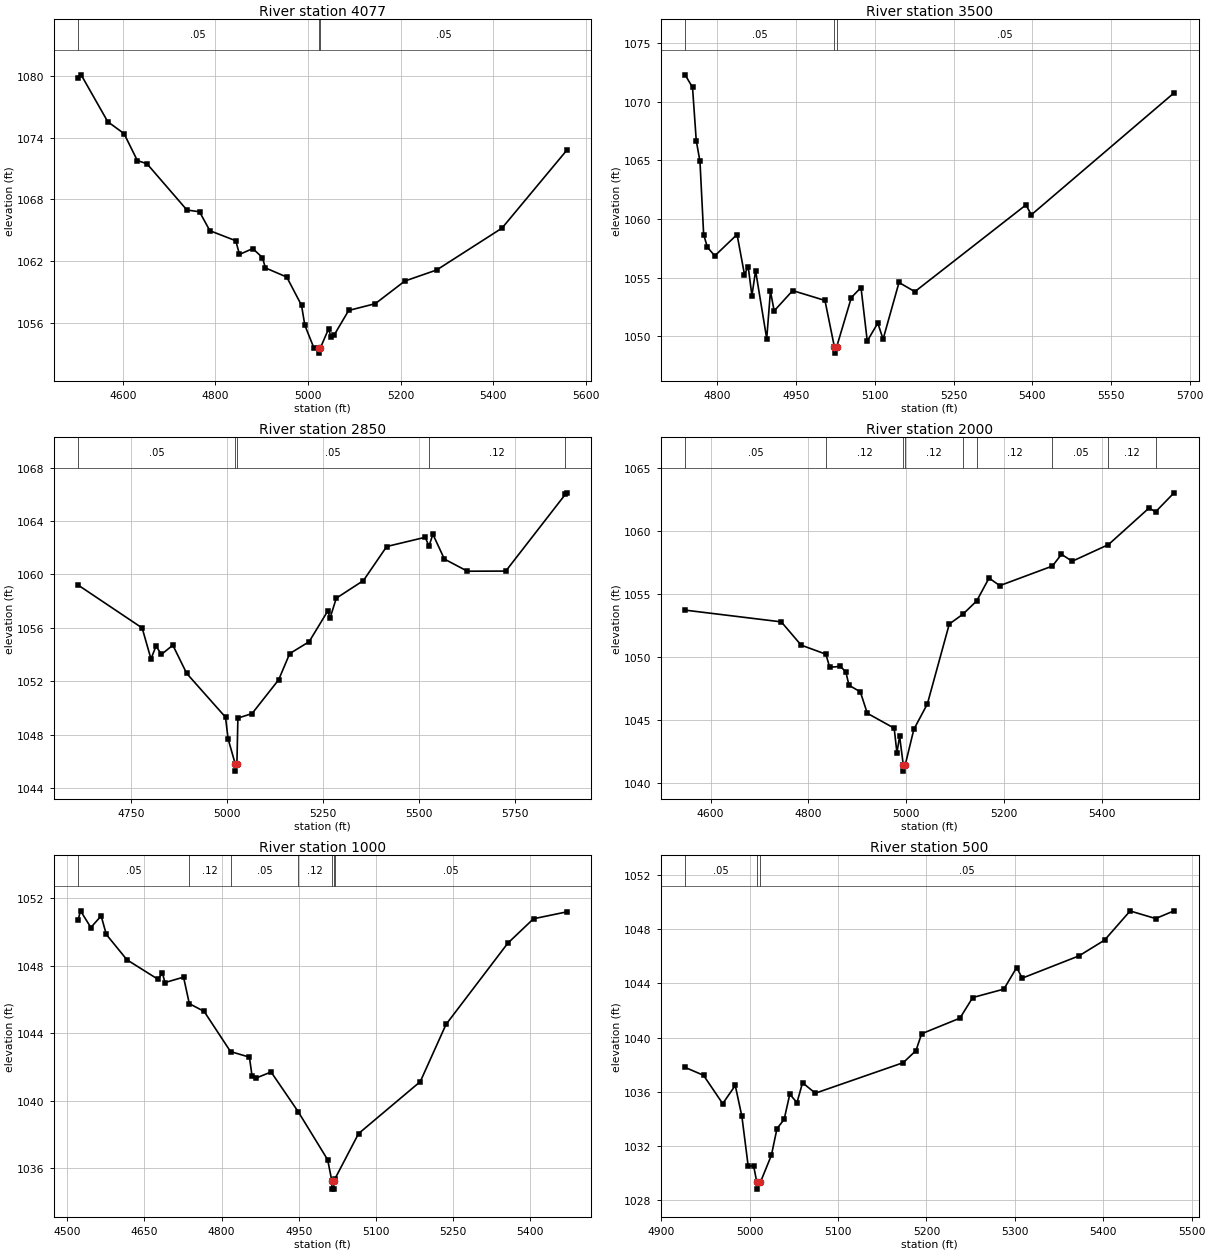
Type RM Length L Ch R = 1,4077,577,577,577
BEGIN DESCRIPTION:
Mapping XS fe11c9dd
END DESCRIPTION:
XS GIS Cut Line= 4
      2819841.89     10227346.73      2820163.03     10227607.12
      2820640.46     10227763.37      2820770.64     10227815.44
#Sta/Elev= 30
  4503.1 1079.81  4509.9 1080.11  4567.4 1075.55  4602.6 1074.39  4631.3 1071.77
  4652.1 1071.46  4738.4 1066.96  4765.6 1066.79  4787.9 1064.95  4843.9 1063.97
  4851.9 1062.64  4880.6 1063.21  4901.4 1062.34  4907.9 1061.33  4954.0 1060.44
  4985.9 1057.69  4993.0 1055.76  5012.5 1053.56  5022.6 1053.54  5022.8 1053.04
  5026.6 1053.54  5044.3 1055.40  5049.6 1054.58  5056.1 1054.78  5087.7 1057.19
  5145.2 1057.85  5208.9 1060.05  5277.9 1061.13  5418.9 1065.20  5559.1 1072.79
#Mann=3,-1,0
  4503.1    0.05       0  5022.6    0.05       0  5026.6    0.05       0
Bank Sta=5022.6,5026.6
Exp/Cntr=0.3,0.1

Type RM Length L Ch R = 1,3500,650,650,650
BEGIN DESCRIPTION:
SANFERNANDO100 7.0
END DESCRIPTION:
XS GIS Cut Line= 3
      2819805.70     10227903.13      2819990.80     10228087.85
      2820655.72     10228003.11
#Sta/Elev= 30
  4738.5 1072.29  4752.6 1071.22  4759.7 1066.69  4766.8 1064.91  4773.8 1058.68
  4780.9 1057.60  4795.0 1056.86  4837.5 1058.68  4851.6 1055.27  4858.7 1055.94
  4865.8 1053.47  4872.8 1055.60  4894.0 1049.80  4901.1 1053.85  4908.2 1052.17
  4943.5 1053.90  5005.0 1053.06  5023.1 1049.07  5023.3 1048.57  5027.1 1049.07
  5055.3 1053.31  5073.7 1054.16  5085.6 1049.60  5105.7 1051.13  5115.8 1049.76
  5146.1 1054.59  5176.3 1053.81  5388.0 1061.20  5398.3 1060.36  5670.3 1070.75
#Mann=3,-1,0
  4738.5    0.05       0  5023.1    0.05       0  5027.1    0.05       0
Bank Sta=5023.1,5027.1
Exp/Cntr=0.3,0.1

Type RM Length L Ch R = 1,2850,850,850,850
BEGIN DESCRIPTION:
Mapping XS 96765b79
END DESCRIPTION:
XS GIS Cut Line= 4
      2819347.09     10228318.95      2819694.28     10228553.30
      2820102.27     10228614.06      2820545.00     10228614.06
#Sta/Elev= 30
  4610.9 1059.21  4778.1 1055.99  4801.1 1053.67  4814.3 1054.64  4828.2 1054.01
  4858.1 1054.70  4894.1 1052.59  4995.3 1049.31  5002.0 1047.70  5021.0 1045.77
  5021.2 1045.27  5025.0 1045.77  5027.6 1049.24  5064.5 1049.58  5133.8 1052.11
  5162.6 1054.07  5213.2 1054.96  5262.4 1057.29  5267.4 1056.70  5284.0 1058.22
  5354.7 1059.54  5415.4 1062.09  5515.7 1062.78  5525.6 1062.12  5535.7 1063.01
  5565.7 1061.15  5625.7 1060.24  5725.7 1060.25  5881.0 1066.00  5885.0 1066.11
#Mann=5,-1,0
  4610.9    0.05       0  5021.0    0.05       0  5025.0    0.05       0
  5525.6    0.12       0  5881.0    0.05       0
Bank Sta=5021,5025
Exp/Cntr=0.3,0.1

Type RM Length L Ch R = 1,2000,1000,1000,1000
BEGIN DESCRIPTION:
SANFERNANDO100 4.0
END DESCRIPTION:
XS GIS Cut Line= 3
      2819586.68     10229099.44      2819998.27     10229286.02
      2820480.66     10229028.12
#Sta/Elev= 30
  4548.1 1053.71  4744.6 1052.78  4785.1 1050.94  4835.7 1050.22  4843.4 1049.19
  4865.4 1049.25  4876.4 1048.82  4882.9 1047.76  4906.0 1047.24  4920.3 1045.54
  4975.2 1044.36  4980.8 1042.42  4986.3 1043.71  4993.8 1041.46  4994.1 1040.96
  4997.8 1041.46  5015.4 1044.27  5043.0 1046.28  5087.8 1052.61  5115.7 1053.39
  5143.8 1054.44  5169.0 1056.25  5191.0 1055.65  5298.4 1057.20  5317.0 1058.13
  5338.9 1057.58  5413.0 1058.90  5496.0 1061.80  5509.1 1061.49  5547.0 1063.00
#Mann=9,-1,0
  4548.1    0.05       0  4835.7    0.12       0  4993.8    0.07       0
  4997.8    0.12       0  5115.7    0.05       0  5143.8    0.12       0
  5298.4    0.05       0  5413.0    0.12       0  5509.1    0.05       0
Bank Sta=4993.8,4997.8
Exp/Cntr=0.3,0.1

Type RM Length L Ch R = 1,1000,500,500,500
BEGIN DESCRIPTION:
SANFERNANDO100 2.0
END DESCRIPTION:
XS GIS Cut Line= 3
      2819280.68     10229378.12      2819309.16     10229856.58
      2819780.67     10229878.11
#Sta/Elev= 30
  4520.7 1050.70  4525.7 1051.26  4545.7 1050.27  4565.8 1050.96  4575.8 1049.86
  4615.9 1048.36  4676.0 1047.21  4685.0 1047.56  4690.0 1047.01  4726.1 1047.33
  4737.3 1045.76  4766.1 1045.30  4817.5 1042.92  4854.3 1042.59  4859.3 1041.48
  4866.3 1041.34  4896.4 1041.71  4949.1 1039.36  5006.5 1036.51  5014.5 1035.27
  5014.8 1034.77  5018.3 1034.77  5018.5 1035.27  5020.3 1035.36  5066.6 1038.06
  5186.7 1041.14  5236.8 1044.53  5356.9 1049.34  5407.0 1050.79  5472.0 1051.20
#Mann=7,-1,0
  4520.7    0.05       0  4737.3    0.12       0  4817.5    0.05       0
  4949.1    0.12       0  5014.5    0.07       0  5018.5    0.12       0
  5020.3    0.05       0
Bank Sta=5014.5,5018.5
Exp/Cntr=0.3,0.1

Type RM Length L Ch R = 1,500,0,0,0
BEGIN DESCRIPTION:
SANFERNANDO100 1.0
END DESCRIPTION:
XS GIS Cut Line= 3
      2818982.05     10230064.02      2818953.52     10230131.10
      2819330.71     10230428.13
#Sta/Elev= 30
  4927.1 1037.80  4947.9 1037.22  4969.6 1035.13  4983.8 1036.47  4991.3 1034.19
  4998.4 1030.54  5004.6 1030.54  5008.2 1029.33  5008.5 1028.83  5012.2 1029.33
  5024.7 1031.33  5031.0 1033.29  5039.1 1033.97  5045.5 1035.83  5053.6 1035.20
  5059.9 1036.67  5074.4 1035.90  5173.8 1038.15  5188.2 1039.04  5194.6 1040.28
  5237.9 1041.43  5252.4 1042.95  5287.6 1043.57  5302.1 1045.16  5308.4 1044.38
  5372.6 1046.02  5401.5 1047.18  5430.4 1049.33  5459.3 1048.77  5480.1 1049.34
#Mann=3,-1,0
  4927.1    0.05       0  5008.2    0.05       0  5012.2    0.05       0
Bank Sta=5008.2,5012.2
Exp/Cntr=0.3,0.1

Chan Stop Cuts=-1