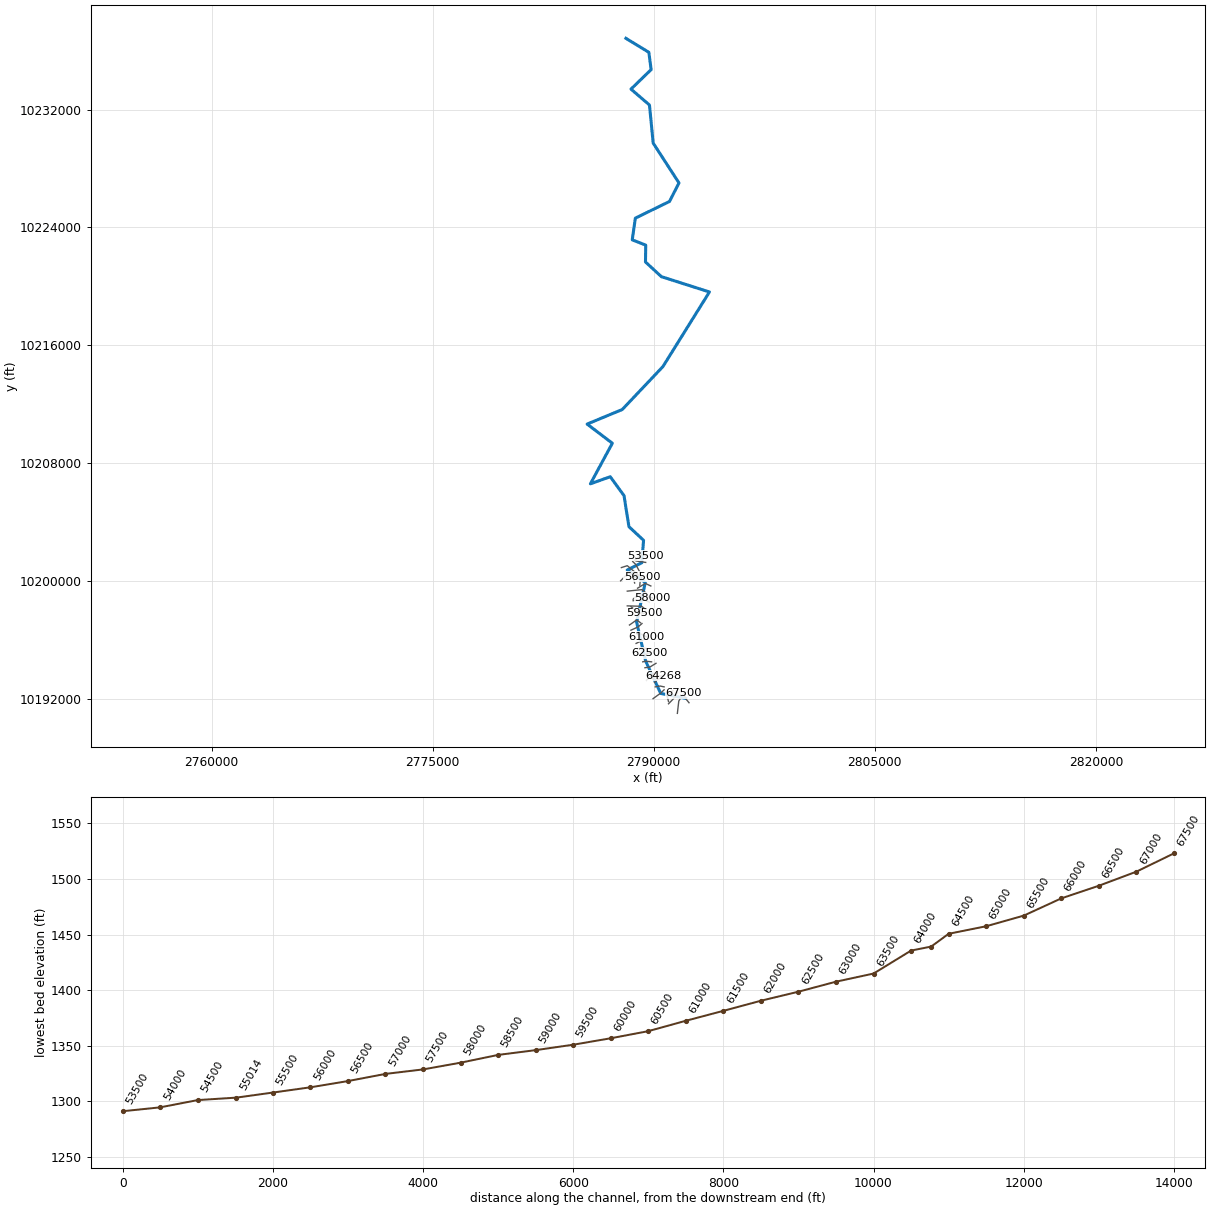
--- SIXMILE CREEK.prj (project) ---

Proj Title=SIXMILE CREEK Base Level Engineering
Current Plan=p01
Default Exp/Contr=0.3,0.1
English Units
Geom File=g01
Flow File=f01
Plan File=p01
Y Axis Title=Elevation
X Axis Title(PF)=Main Channel Distance
X Axis Title(XS)=Station
BEGIN DESCRIPTION:
SIXMILE CREEK
END DESCRIPTION:
DSS Export Rating Curves= 0
DSS Export Rating Curve Sorted= 0
DSS Export Volume Flow Curves= 0
DXF OffsetX= 0
DXF OffsetY= 0
DXF ScaleX= 1
DXF ScaleY= 10

--- SIXMILE CREEK.p01 (plan) ---

Plan Title=Multiple Run
Short Identifier=Multiple
Geom File=g01
Flow File=f01
Subcritical Flow
K Sum by GR= 0
Std Step Tol= 0.01
Critical Tol= 0.01
Num of Std Step Trials= 20
Max Error Tol= 0.3
Flow Tol Ratio= 0.001
Split Flow NTrial= 30
Split Flow Tol= 0.02
Split Flow Ratio= 0.02
Log Output Level= 0
Friction Slope Method= 1
Unsteady Friction Slope Method= 2
Unsteady Bridges Friction Slope Method= 1
Parabolic Critical Depth
Global Vel Dist=  1 , 1 , 1
Global Log Level= 0
CheckData=True
Encroach Param= -1, 0, 0, 0
BEGIN DESCRIPTION:
Multiple Run
END DESCRIPTION:

--- SIXMILE CREEK.f01 (steady flow) ---

Flow Title=Multiple
Program Version=4.10
Number of Profiles= 7
Profile Names=10-year,25-year,50-year,1pct_min,100-year,1pct_plu,500-year
River Rch & RM=SIXMILE CREEK,Reach-1         ,67500
     201     308     500     347     664    1274     936
River Rch & RM=SIXMILE CREEK,Reach-1         ,62500
     460     739    1348     972    1853    3532    2608
River Rch & RM=SIXMILE CREEK,Reach-1         ,59000
     830    1401    2342    1808    3266    5900    4580
River Rch & RM=SIXMILE CREEK,Reach-1         ,50000
    1649    2897    5127    3718    7305   14349   10134
River Rch & RM=SIXMILE CREEK,Reach-1         ,42000
    1784    3149    5589    4331    7980   14705   11055
River Rch & RM=SIXMILE CREEK,Reach-1         ,40402
    1806    3190    5650    4380    8071   14873   11182
River Rch & RM=SIXMILE CREEK,Reach-1         ,40000
    2442    4439    7653    6258   11000   19333   15106
River Rch & RM=SIXMILE CREEK,Reach-1         ,34000
    2755    5064    8450    6525   12155   22642   16627
River Rch & RM=SIXMILE CREEK,Reach-1         ,28500
    2788    5132    8511    6472   12243   23157   16743
River Rch & RM=SIXMILE CREEK,Reach-1         ,27500
    3160    5872    9750    7216   14050   27356   19118
River Rch & RM=SIXMILE CREEK,Reach-1         ,26000
    3508    6571   10877    8991   15732   27528   21431
River Rch & RM=SIXMILE CREEK,Reach-1         ,18882
    3540    6638   10950    8502   15841   29517   21586
River Rch & RM=SIXMILE CREEK,Reach-1         ,17500
    4549    8614   14233   11413   20601   37187   27803
River Rch & RM=SIXMILE CREEK,Reach-1         ,13500
    4905    9313   15315   11546   22170   42568   29856
River Rch & RM=SIXMILE CREEK,Reach-1         ,9386
    5035    9575   15645   13101   22650   39157   30473
River Rch & RM=SIXMILE CREEK,Reach-1         ,6000
    5159    9834   15974   12299   23150   43573   31160
Boundary for River Rch & Prof#=SIXMILE CREEK,Reach-1         , 1
Up Type= 0
Dn Type= 3
Dn Slope=0.001
Boundary for River Rch & Prof#=SIXMILE CREEK,Reach-1         , 2
Up Type= 0
Dn Type= 3
Dn Slope=0.001
Boundary for River Rch & Prof#=SIXMILE CREEK,Reach-1         , 3
Up Type= 0
Dn Type= 3
Dn Slope=0.001
Boundary for River Rch & Prof#=SIXMILE CREEK,Reach-1         , 4
Up Type= 0
Dn Type= 3
Dn Slope=0.001
Boundary for River Rch & Prof#=SIXMILE CREEK,Reach-1         , 5
Up Type= 0
Dn Type= 3
Dn Slope=0.001
Boundary for River Rch & Prof#=SIXMILE CREEK,Reach-1         , 6
Up Type= 0
Dn Type= 3
Dn Slope=0.001
Boundary for River Rch & Prof#=SIXMILE CREEK,Reach-1         , 7
Up Type= 0
Dn Type= 3
Dn Slope=0.001
DSS Import GetInterval= 0
DSS Import GetPeak= 0
DSS Import FillOption= 0

--- SIXMILE CREEK.g01 (geometry) ---

Geom Title=Existing Conditions
Program Version=4.10

River Reach=SIXMILE CREEK   ,Reach-1
Reach XY= 30
        2792165.       10192024.       2790477.5       10192355.
        2789453.       10194556.        2788840.       10197198.
      2789430.25       10199892.       2788202.5       10200739.
        2789190.       10201230.        2789312.       10202755.
      2788318.25       10203683.        2787986.       10205785.
      2787051.75       10207073.      2785704.75       10206591.
        2787192.       10209346.        2785483.       10210648.
      2787866.25       10211637.      2790625.75       10214553.
        2793782.       10219619.      2790519.25       10220659.
        2789442.       10221655.      2789458.75       10222799.
      2788544.25       10223159.      2788754.75       10224632.
      2791071.25       10225764.        2791715.       10227022.
        2789965.       10229726.      2789712.25       10232314.
      2788458.75       10233393.       2789825.5       10234720.
      2789669.25       10235893.      2788114.25       10236842.

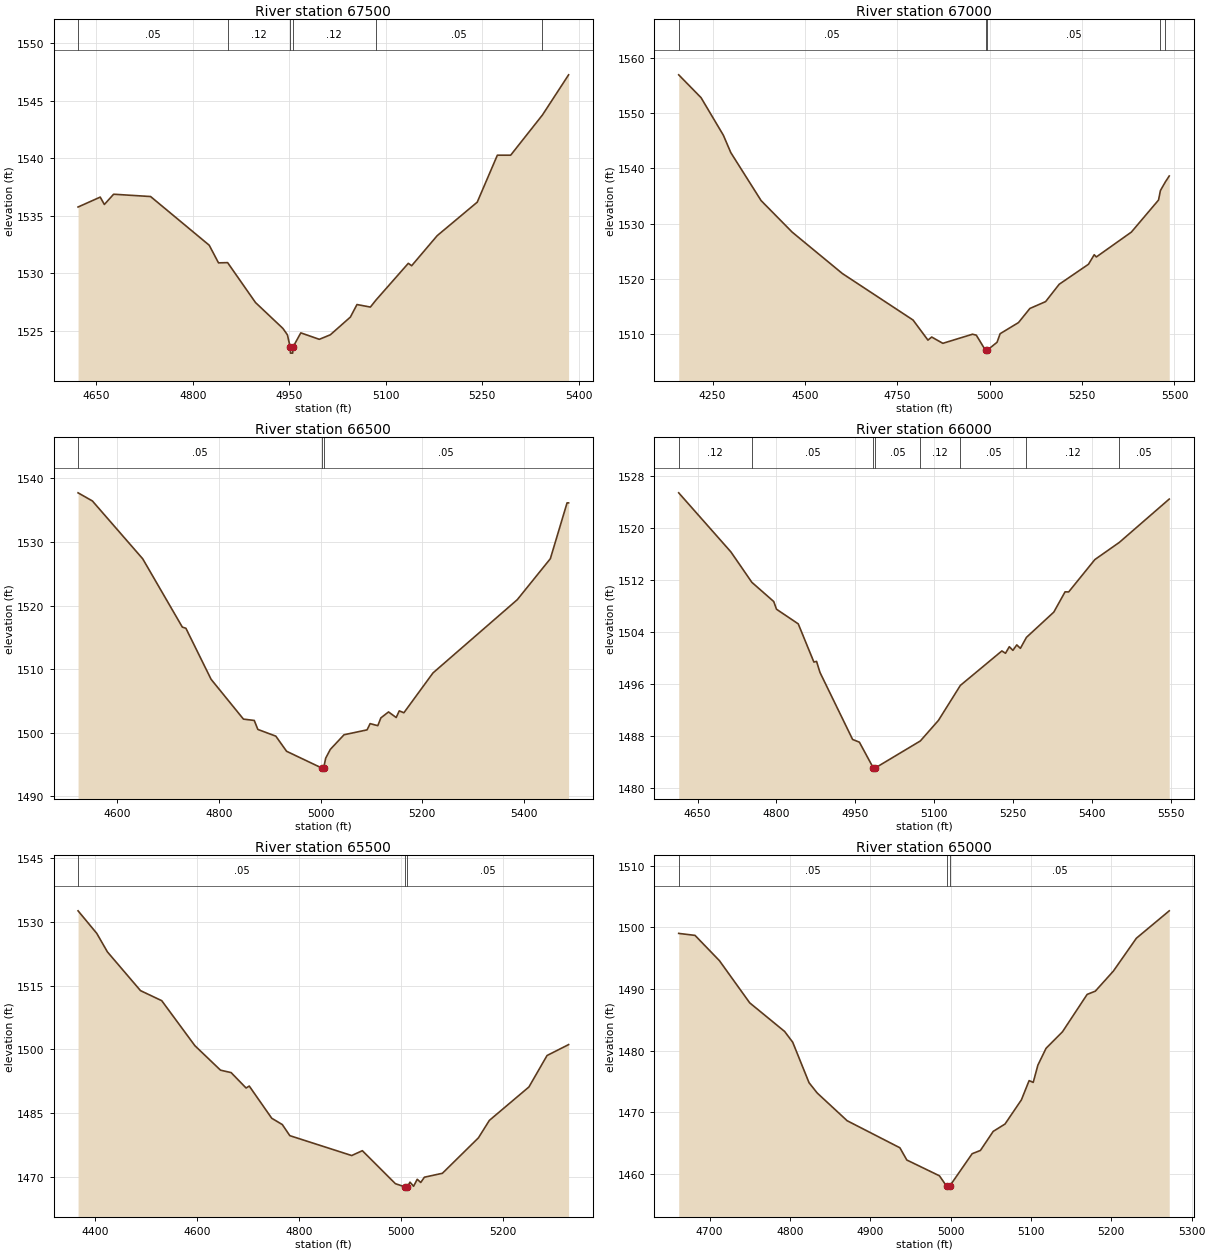
Type RM Length L Ch R = 1 ,67500   ,500,500,500
BEGIN DESCRIPTION:
SIXMILE CREEK 135.0
END DESCRIPTION:
XS GIS Cut Line= 3
      2792395.43     10191725.16      2792157.91     10192019.85
      2792053.44     10192389.78
#Sta/Elev= 30
  4621.5 1535.76    4656 1536.62  4662.4 1535.98  4676.8 1536.87  4734.3 1536.67
  4825.5 1532.44  4839.9 1530.91  4854.1 1530.93  4897.5 1527.46    4940 1525.22
  4947.1 1524.66  4951.5 1523.57  4951.8 1523.07  4955.3 1523.07  4955.5 1523.57
  4967.9 1524.83  4996.7 1524.27  5013.8 1524.66    5045  1526.2  5055.3 1527.29
  5076.1 1527.07  5084.7 1527.67  5135.1 1530.87  5140.3 1530.66    5180 1533.27
  5242.3 1536.18  5273.6 1540.26  5294.3 1540.26  5343.7 1543.75  5384.4 1547.24
#Mann= 6 ,-1 , 0
  4621.5     .05       0  4854.1     .12       0  4951.5     .07       0
  4955.5     .12       0  5084.7     .05       0  5343.7     .12       0
Bank Sta=4951.5,4955.5
XS Rating Curve= 0 ,0
Exp/Cntr=0.3,0.1

Type RM Length L Ch R = 1 ,67000   ,500,500,500
BEGIN DESCRIPTION:
SIXMILE CREEK 134.0
END DESCRIPTION:
XS GIS Cut Line= 3
      2791605.68      10191003.1      2791701.54     10191839.12
       2791955.7     10192253.13
#Sta/Elev= 30
  4158.5 1556.92  4218.9  1552.8  4279.3 1546.01  4299.4 1542.87  4381.5 1534.19
  4465.6 1528.49  4601.4 1521.01  4792.6 1512.61  4832.9 1508.98    4843 1509.54
  4873.2  1508.4  4953.7 1510.05  4963.8 1509.87  4988.7 1507.13    4989 1506.63
  4992.7 1507.13  5019.9 1508.59  5028.2 1510.14  5077.9 1512.15  5108.7  1514.7
  5151.3 1515.94    5188 1519.07  5267.3 1522.69  5282.8 1524.41  5288.6 1524.01
  5383.3  1528.5  5456.8 1534.29  5461.9    1536  5475.3 1537.57  5485.8 1538.64
#Mann= 5 ,-1 , 0
  4158.5     .05       0  4988.7     .05       0  4992.7     .05       0
  5461.9     .12       0  5475.3     .05       0
Bank Sta=4988.7,4992.7
XS Rating Curve= 0 ,0
Exp/Cntr=0.3,0.1

Type RM Length L Ch R = 1 ,66500   ,500,500,500
BEGIN DESCRIPTION:
SIXMILE CREEK 133.0
END DESCRIPTION:
XS GIS Cut Line= 3
      2791005.67      10191653.1      2791338.27     10191995.29
       2791605.7     10192403.13
#Sta/Elev= 30
  4522.8 1537.74    4551 1536.46    4650 1527.36  4727.9 1516.62  4734.9 1516.44
  4784.5 1508.41  4848.1 1502.15  4869.4 1501.94  4876.4 1500.53  4911.8 1499.47
    4933 1497.09  5001.9 1494.47  5002.1 1493.97  5005.9 1494.47  5009.9 1496.01
    5019 1497.39    5046 1499.69  5091.3 1500.46  5097.3 1501.44  5112.4 1501.12
  5118.4 1502.34  5133.5 1503.28  5148.6  1502.4  5154.6 1503.45  5163.7 1503.15
  5220.9 1509.41  5386.7 1520.93  5451.8 1527.38  5484.7 1536.16  5487.7 1536.16
#Mann= 3 ,-1 , 0
  4522.8     .05       0  5001.9     .05       0  5005.9     .05       0
Bank Sta=5001.9,5005.9
XS Rating Curve= 0 ,0
Exp/Cntr=0.3,0.1

Type RM Length L Ch R = 1 ,66000   ,500,500,500
BEGIN DESCRIPTION:
SIXMILE CREEK 132.0
END DESCRIPTION:
XS GIS Cut Line= 3
      2791005.69     10191803.07      2790909.48     10192176.68
      2791305.67      10192553.1
#Sta/Elev= 30
  4614.2 1525.47  4713.4 1516.37  4753.3 1511.68  4794.8 1508.73  4800.1 1507.54
  4841.4 1505.29  4871.1 1499.41  4876.2 1499.51  4882.7 1497.81  4944.7 1487.49
  4957.6 1487.07    4984 1483.11  4984.2 1482.61    4988 1483.11  5073.5 1487.26
  5107.9 1490.43  5149.5 1495.81  5228.4 1501.12  5235.3 1500.76  5242.5 1501.77
  5249.4 1501.21  5256.7 1502.05  5263.6 1501.52  5275.1 1503.21  5327.1  1507.1
  5348.5 1510.22  5355.4 1510.21  5405.1 1515.19  5451.7 1517.84  5546.5 1524.51
#Mann= 8 ,-1 , 0
  4614.2     .12       0  4753.3     .05       0    4984     .05       0
    4988     .05       0  5073.5     .12       0  5149.5     .05       0
  5275.1     .12       0  5451.7     .05       0
Bank Sta=4984,4988
XS Rating Curve= 0 ,0
Exp/Cntr=0.3,0.1

Type RM Length L Ch R = 1 ,65500   ,500,500,500
BEGIN DESCRIPTION:
SIXMILE CREEK 131.0
END DESCRIPTION:
XS GIS Cut Line= 3
      2789955.72     10192003.14      2790468.82      10192375.2
      2790705.68     10192603.11
#Sta/Elev= 30
  4366.2 1532.62  4402.9 1527.31  4423.8 1522.95  4488.7 1513.83  4530.4 1511.46
  4595.4 1500.87  4645.7  1495.1  4666.5 1494.53  4695.9  1490.9  4702.1 1491.36
  4746.2 1483.78    4767 1482.29  4781.7 1479.68  4903.1    1475    4924 1476.14
  4988.9 1468.37  5008.3 1467.59  5008.6 1467.09  5012.3 1467.59  5017.5 1468.74
  5024.5 1467.76  5031.7 1469.41  5038.6 1468.66  5045.8  1469.9  5081.1 1470.82
  5151.8 1479.17  5173.2 1483.27  5250.9 1491.15  5286.4 1498.55  5328.7 1501.12
#Mann= 3 ,-1 , 0
  4366.2     .05       0  5008.3     .05       0  5012.3     .05       0
Bank Sta=5008.3,5012.3
XS Rating Curve= 0 ,0
Exp/Cntr=0.3,0.1

Type RM Length L Ch R = 1 ,65000   ,500,500,500
BEGIN DESCRIPTION:
SIXMILE CREEK 130.0
END DESCRIPTION:
XS GIS Cut Line= 3
      2790105.69     10192803.11      2790439.43     10192859.13
       2790705.7     10192803.11
#Sta/Elev= 30
  4661.6 1499.01  4681.9 1498.69  4712.3 1494.59    4750 1487.75  4793.4 1483.12
  4803.5 1481.37  4823.8 1474.81    4834 1473.14  4871.2 1468.65  4936.9 1464.26
  4945.5 1462.28  4986.1 1459.72  4994.9 1458.06  4995.2 1457.56  4998.9 1458.06
  5026.8  1463.3  5037.1 1463.83    5053 1466.92  5067.7 1468.11  5088.1 1472.03
  5097.7 1475.15  5102.8 1474.86  5108.6 1477.65  5118.8 1480.39  5139.2 1483.06
  5169.9 1489.12  5180.1 1489.65  5202.5 1492.89  5231.2 1498.23  5272.1 1502.67
#Mann= 3 ,-1 , 0
  4661.6     .05       0  4994.9     .05       0  4998.9     .05       0
Bank Sta=4994.9,4998.9
XS Rating Curve= 0 ,0
Exp/Cntr=0.3,0.1

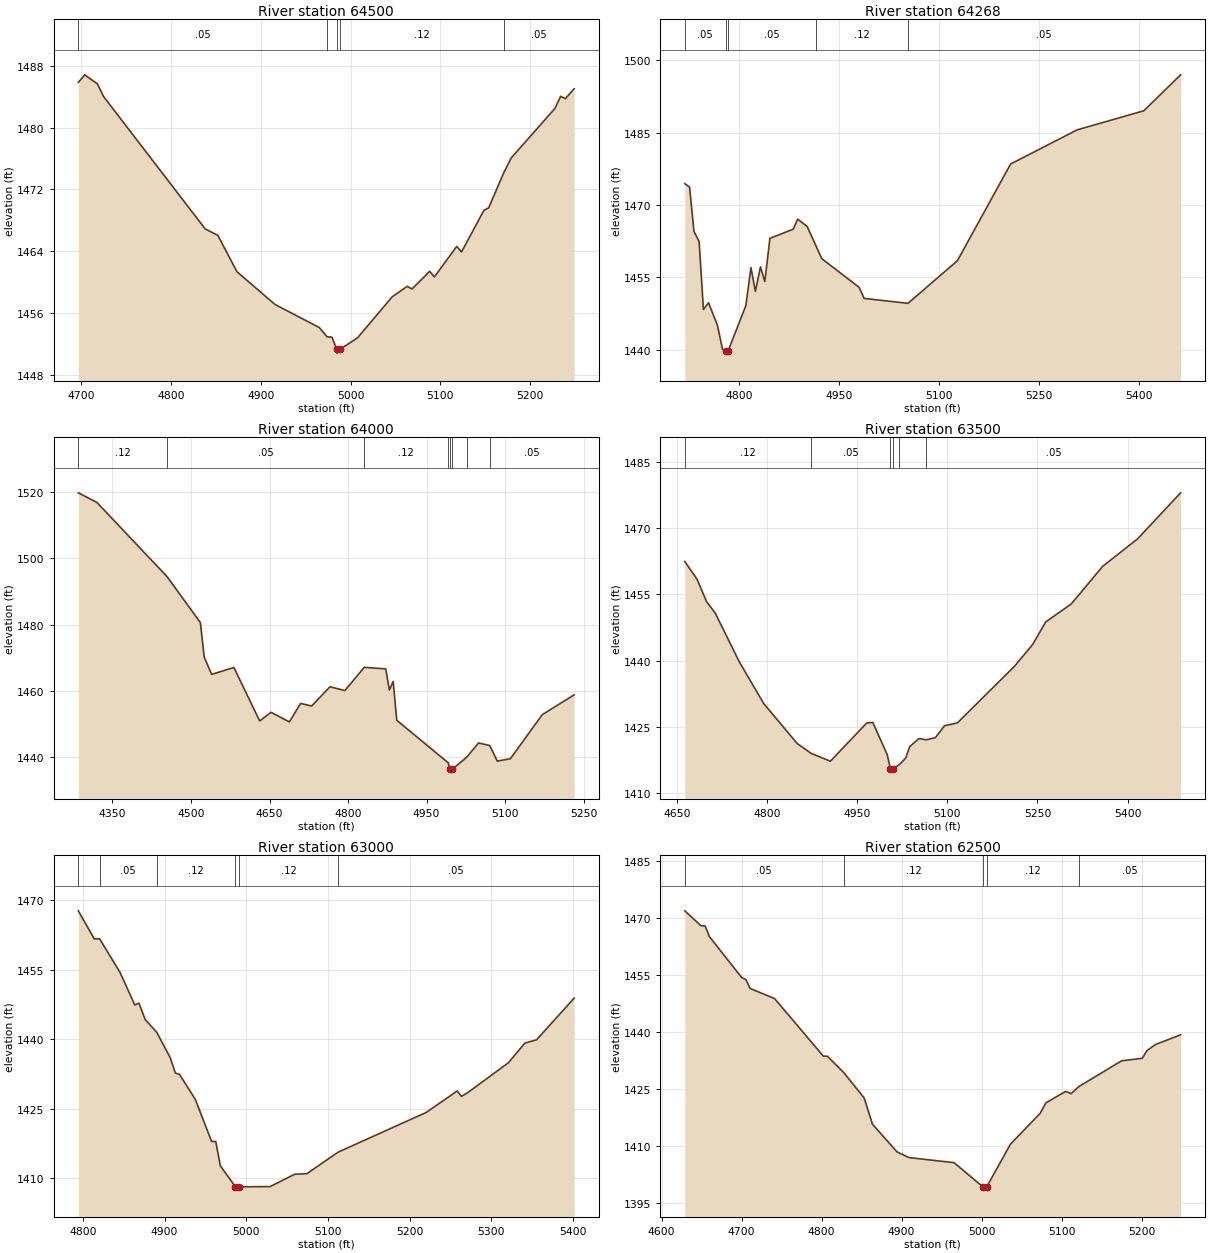
Type RM Length L Ch R = 1 ,64500   ,232,232,232
BEGIN DESCRIPTION:
SIXMILE CREEK 129.0
END DESCRIPTION:
XS GIS Cut Line= 3
       2790055.7     10193103.12      2790272.24     10193315.63
      2790505.69     10193403.11
#Sta/Elev= 30
  4696.6 1485.86  4703.7 1486.84  4717.8 1485.68  4724.8 1484.02    4838 1466.87
  4852.1 1466.04  4873.4 1461.32  4915.8 1457.08  4965.3 1454.08  4973.8 1452.89
  4979.4 1452.83  4984.5 1451.27  4984.8 1450.77  4988.5 1451.27    5008 1452.78
  5046.4 1458.06  5063.2 1459.43  5068.6 1459.09  5088.2 1461.37  5093.5 1460.65
  5118.4  1464.6  5123.8 1463.89  5148.7 1469.28    5154  1469.6  5170.7 1474.11
    5179 1476.05  5227.9 1482.49  5234.2 1484.06  5239.5 1483.75  5249.3 1485.03
#Mann= 5 ,-1 , 0
  4696.6     .05       0  4973.8     .12       0  4984.5     .07       0
  4988.5     .12       0  5170.7     .05       0
Bank Sta=4984.5,4988.5
XS Rating Curve= 0 ,0
Exp/Cntr=0.3,0.1

Type RM Length L Ch R = 1 ,64268   ,268,268,268
BEGIN DESCRIPTION:
Mapping XS f7292ed9
END DESCRIPTION:
XS GIS Cut Line= 3
      2789958.45     10193340.67      2790186.34       10193536.
      2790630.96     10193546.85
#Sta/Elev= 30
  4718.3 1474.43  4725.5 1473.71  4732.1 1464.51  4739.8 1462.44  4746.3 1448.32
    4754 1449.71  4767.3 1445.06  4774.9 1440.11  4779.5 1439.77  4779.7 1439.27
  4783.5 1439.77    4810 1449.12  4817.7 1457.02  4824.3 1452.09    4832 1457.16
  4838.5 1454.13  4846.2 1463.09  4881.3 1464.99  4887.9 1467.08  4902.2 1465.53
  4915.6 1461.45  4924.1 1458.87  4980.1 1452.93  4987.8 1450.62  5053.6  1449.6
  5127.8 1458.43  5207.8 1478.51  5307.9  1485.6  5407.9 1489.55  5463.2 1497.01
#Mann= 5 ,-1 , 0
  4718.3     .05       0  4779.5     .07       0  4783.5     .05       0
  4915.6     .12       0  5053.6     .05       0
Bank Sta=4779.5,4783.5
XS Rating Curve= 0 ,0
Exp/Cntr=0.3,0.1

Type RM Length L Ch R = 1 ,64000   ,500,500,500
BEGIN DESCRIPTION:
SIXMILE CREEK 128.0
END DESCRIPTION:
XS GIS Cut Line= 3
      2789505.71     10193253.14      2790027.13     10193742.66
      2790255.73      10193703.1
#Sta/Elev= 30
  4284.8  1519.8  4320.2 1516.91  4454.4 1494.46    4518 1480.56  4525.3 1470.13
  4539.5 1464.93    4582 1467.01  4631.3 1450.84  4652.8 1453.46    4688 1450.57
  4709.4 1456.15  4730.5 1455.36  4765.6 1461.17    4794 1460.04    4831 1467.06
  4872.1 1466.57    4879 1460.21  4886.3 1462.79  4893.1 1451.06  4991.4  1438.2
  4994.7 1436.18  4994.9 1435.68  4998.7 1436.18  5026.5 1439.86  5049.3 1444.19
  5070.8 1443.42  5085.1 1438.71  5110.2 1439.43  5171.1 1452.75    5232 1458.74
#Mann= 8 ,-1 , 0
  4284.8     .12       0  4454.4     .05       0    4831     .12       0
  4991.4     .05       0  4994.7     .05       0  4998.7     .05       0
  5026.5     .12       0  5070.8     .05       0
Bank Sta=4994.7,4998.7
XS Rating Curve= 0 ,0
Exp/Cntr=0.3,0.1

Type RM Length L Ch R = 1 ,63500   ,500,500,500
BEGIN DESCRIPTION:
SIXMILE CREEK 127.0
END DESCRIPTION:
XS GIS Cut Line= 3
      2789405.66     10194103.11      2789739.24      10194148.1
      2790155.67      10194403.1
#Sta/Elev= 30
  4663.4  1462.4  4683.6 1458.45  4699.8 1453.28  4713.9 1450.77  4754.2 1439.69
  4794.6  1430.3  4850.3 1421.26  4873.4 1419.03  4905.6 1417.24  4966.1 1425.89
  4976.2    1426    5000 1418.79  5005.6  1415.5  5005.8    1415  5009.6  1415.5
  5020.5 1416.49    5031 1417.97  5037.6 1420.55    5053 1422.37  5065.2 1422.08
  5080.2 1422.56  5095.6 1425.27  5116.9 1425.91  5211.7 1438.68  5242.1 1443.63
  5263.9 1448.74  5306.5 1452.82  5358.7 1461.32  5416.7 1467.52  5488.3 1477.93
#Mann= 6 ,-1 , 0
  4663.4     .12       0  4873.4     .05       0  5005.6     .05       0
  5009.6     .05       0  5020.5     .12       0  5065.2     .05       0
Bank Sta=5005.6,5009.6
XS Rating Curve= 0 ,0
Exp/Cntr=0.3,0.1

Type RM Length L Ch R = 1 ,63000   ,500,500,500
BEGIN DESCRIPTION:
SIXMILE CREEK 126.0
END DESCRIPTION:
XS GIS Cut Line= 3
      2789255.71     10194503.12      2789456.68     10194546.01
      2789855.68     10194503.11
#Sta/Elev= 30
  4794.5 1467.67  4814.1  1461.6  4820.5 1461.67  4845.6 1454.37  4863.6 1447.38
  4868.7 1447.78  4876.3 1444.25  4890.4 1441.51    4907 1436.01  4913.2 1432.72
  4918.3 1432.42  4937.6 1427.06  4957.6 1417.97  4962.7 1417.96  4968.3 1412.71
  4986.8 1408.19    4987 1407.69  4990.8 1408.19  5029.2 1408.24  5059.3  1410.9
  5074.2 1411.02  5112.4 1415.66  5220.3 1424.22  5258.2 1428.85  5263.3 1427.68
  5270.6 1428.43  5320.8 1434.92    5341 1439.16  5355.3 1439.88  5401.3 1448.85
#Mann= 6 ,-1 , 0
  4794.5     .12       0  4820.5     .05       0  4890.4     .12       0
  4986.8     .07       0  4990.8     .12       0  5112.4     .05       0
Bank Sta=4986.8,4990.8
XS Rating Curve= 0 ,0
Exp/Cntr=0.3,0.1

Type RM Length L Ch R = 1 ,62500   ,500,500,500
BEGIN DESCRIPTION:
SIXMILE CREEK 125.0
END DESCRIPTION:
XS GIS Cut Line= 3
      2789105.72     10194953.12      2789469.38     10195026.02
      2789705.72     10195103.12
#Sta/Elev= 30
  4629.1  1471.9  4649.4 1467.97  4654.5 1467.93  4659.7 1465.15  4700.4  1454.3
  4705.5  1453.8  4710.7 1451.48  4741.3 1448.82  4802.2 1433.67  4807.3 1433.65
  4827.6 1429.37  4853.2 1422.68  4863.6 1415.78  4894.2  1408.5  4909.2 1406.99
  4965.6 1405.65  5002.1 1399.19  5002.3 1398.69  5006.1 1399.19    5036 1410.52
  5073.1 1418.63  5080.3 1421.38    5105 1424.41  5111.8 1423.81  5121.5 1425.68
  5174.9 1432.45  5200.7  1433.1  5206.5 1435.12    5217 1436.71  5248.6 1439.29
#Mann= 5 ,-1 , 0
  4629.1     .05       0  4827.6     .12       0  5002.1     .07       0
  5006.1     .12       0  5121.5     .05       0
Bank Sta=5002.1,5006.1
XS Rating Curve= 0 ,0
Exp/Cntr=0.3,0.1

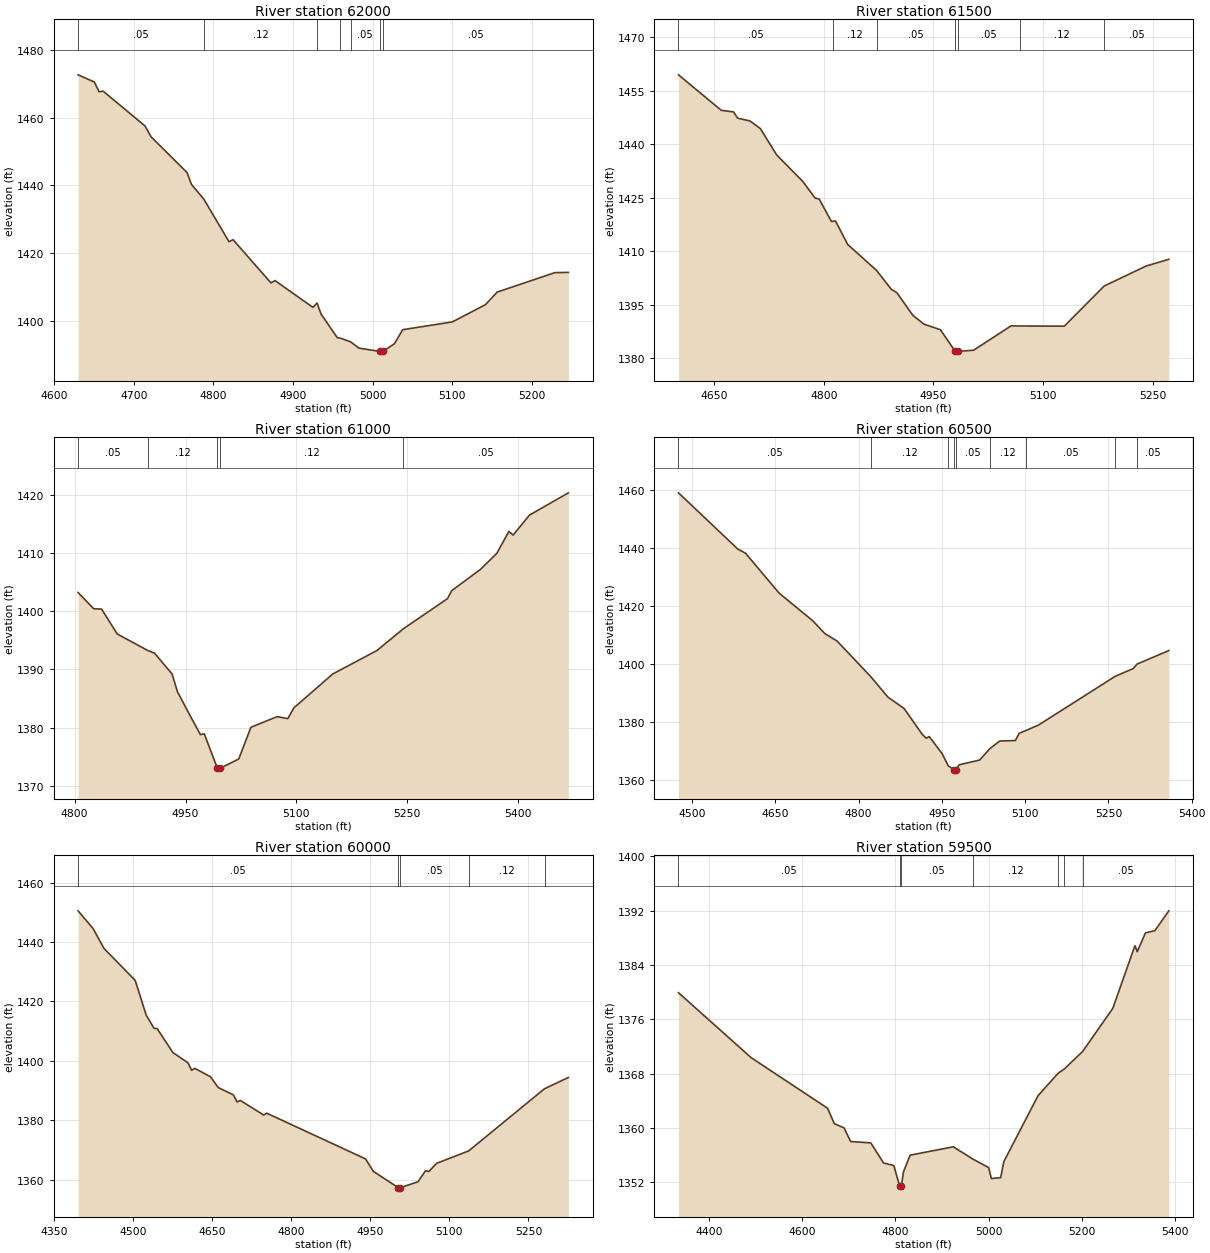
Type RM Length L Ch R = 1 ,62000   ,500,500,500
BEGIN DESCRIPTION:
SIXMILE CREEK 124.0
END DESCRIPTION:
XS GIS Cut Line= 3
      2788905.64      10195403.1      2789269.47     10195470.96
      2789505.72      10195403.1
#Sta/Elev= 30
  4629.9 1472.61  4650.3  1470.5  4656.3 1467.63  4661.4  1467.8  4714.1 1457.51
  4721.5 1454.37  4766.8  1443.8  4772.4 1440.28  4787.8 1435.99  4819.5 1423.41
  4824.6    1424  4872.2 1411.26  4877.3 1411.94  4924.9 1404.06  4930.1 1405.32
  4935.1 1402.09  4955.5 1395.12  4959.5 1394.96  4972.2  1393.9  4982.7 1392.04
    5009 1391.06  5009.2 1390.56    5013 1391.06  5027.3 1393.35  5037.7 1397.47
  5100.1 1399.77  5141.7 1404.86  5156.3 1408.55  5228.9  1414.3  5245.8 1414.36
#Mann= 7 ,-1 , 0
  4629.9     .05       0  4787.8     .12       0  4930.1     .05       0
  4959.5     .12       0  4972.2     .05       0    5009     .05       0
    5013     .05       0
Bank Sta=5009,5013
XS Rating Curve= 0 ,0
Exp/Cntr=0.3,0.1

Type RM Length L Ch R = 1 ,61500   ,500,500,500
BEGIN DESCRIPTION:
SIXMILE CREEK 123.0
END DESCRIPTION:
XS GIS Cut Line= 3
      2788805.73     10195753.13      2789161.99     10195932.36
      2789405.71     10196053.12
#Sta/Elev= 30
  4601.2 1459.45  4659.7 1449.51  4676.5 1449.06  4682.1 1447.31  4698.8 1446.53
  4713.1 1444.41  4735.5 1437.01  4771.3 1429.56  4788.1 1424.92  4793.7 1424.64
  4810.4 1418.35  4812.6 1418.41    4816 1418.49  4832.7 1411.91  4872.1 1404.66
  4892.2 1399.38  4899.7 1398.45    4922 1392.02    4937 1389.59  4959.4 1388.04
  4979.8 1381.97    4980 1381.47  4983.8 1381.97  5004.9 1382.28  5056.2 1389.11
  5068.5 1389.07    5129 1389.02  5183.5 1400.27  5241.1 1405.89    5272 1407.76
#Mann= 7 ,-1 , 0
  4601.2     .05       0  4812.6     .12       0  4872.1     .05       0
  4979.8     .05       0  4983.8     .05       0  5068.5     .12       0
  5183.5     .05       0
Bank Sta=4979.8,4983.8
XS Rating Curve= 0 ,0
Exp/Cntr=0.3,0.1

Type RM Length L Ch R = 1 ,61000   ,500,500,500
BEGIN DESCRIPTION:
SIXMILE CREEK 122.0
END DESCRIPTION:
XS GIS Cut Line= 3
      2788905.65      10196353.1        2789090.     10196417.59
      2789505.72     10196203.09
#Sta/Elev= 30
  4804.7 1403.21  4825.9 1400.41  4836.5 1400.36  4857.7 1396.08  4898.8 1393.26
  4908.1 1392.79  4931.9 1389.21  4939.1 1386.17  4953.1 1382.81  4970.1 1378.81
  4975.4 1378.94  4993.1 1373.04  4993.3 1372.54  4997.1 1373.04    5022 1374.63
  5038.5 1380.07  5073.9 1381.89  5088.4 1381.55  5096.4 1383.38  5149.3 1389.23
  5208.9 1393.24  5244.7 1396.98  5304.2 1402.14  5310.2 1403.54  5348.7 1407.15
  5370.9 1409.91  5387.4 1413.69    5393 1413.05  5415.2 1416.49  5467.8 1420.31
#Mann= 5 ,-1 , 0
  4804.7     .05       0  4898.8     .12       0  4993.1     .07       0
  4997.1     .12       0  5244.7     .05       0
Bank Sta=4993.1,4997.1
XS Rating Curve= 0 ,0
Exp/Cntr=0.3,0.1

Type RM Length L Ch R = 1 ,60500   ,500,500,500
BEGIN DESCRIPTION:
SIXMILE CREEK 121.0
END DESCRIPTION:
XS GIS Cut Line= 3
      2788455.66      10196653.1        2788933.     10196869.73
      2789205.67      10197103.1
#Sta/Elev= 30
  4475.8 1459.03  4582.4 1439.71  4596.6 1438.22  4657.2 1424.46  4717.4 1415.02
  4739.4 1410.56  4761.4    1408  4821.8 1395.79  4852.8 1388.72  4882.1 1384.77
  4915.1 1375.79    4922 1374.55  4927.5 1375.09  4950.6 1369.22  4961.5 1365.04
  4971.7  1363.7  4971.9  1363.2  4975.7  1363.7    4981 1365.36  5018.1 1367.02
  5036.8 1370.97  5054.3 1373.56  5082.5 1373.74  5089.4 1376.24  5102.5 1377.27
  5124.6 1379.11  5261.6 1395.77  5294.7 1398.52  5301.9 1400.08  5358.9 1404.71
#Mann= 9 ,-1 , 0
  4475.8     .05       0  4821.8     .12       0  4961.5     .05       0
  4971.7     .05       0  4975.7     .05       0  5036.8     .12       0
  5102.5     .05       0  5261.6     .12       0  5301.9     .05       0
Bank Sta=4971.7,4975.7
XS Rating Curve= 0 ,0
Exp/Cntr=0.3,0.1

Type RM Length L Ch R = 1 ,60000   ,500,500,500
BEGIN DESCRIPTION:
SIXMILE CREEK 120.0
END DESCRIPTION:
XS GIS Cut Line= 3
      2788355.65     10197003.09       2788848.2      10197352.5
      2789105.72     10197153.08
#Sta/Elev= 30
  4396.1 1450.48  4424.4 1444.57  4445.3 1437.82  4504.4 1427.07  4525.3 1415.36
  4540.1 1410.96  4546.2 1410.81  4575.8  1402.8  4604.6  1399.3  4611.4  1396.8
  4617.6 1397.45  4647.1 1394.64  4661.9 1390.99  4690.4 1388.56  4697.6 1386.14
  4703.7 1386.67    4748 1381.75  4754.1 1382.35  4941.2 1366.97  4955.9 1362.79
  5003.1 1357.31  5003.4 1356.81  5007.1 1357.31  5040.5 1359.28  5054.9    1363
  5061.3 1362.76  5075.8 1365.49  5136.5 1369.66  5280.4 1390.59  5325.7  1394.4
#Mann= 5 ,-1 , 0
  4396.1     .05       0  5003.1     .05       0  5007.1     .05       0
  5136.5     .12       0  5280.4     .05       0
Bank Sta=5003.1,5007.1
XS Rating Curve= 0 ,0
Exp/Cntr=0.3,0.1

Type RM Length L Ch R = 1 ,59500   ,500,500,500
BEGIN DESCRIPTION:
SIXMILE CREEK 119.0
END DESCRIPTION:
XS GIS Cut Line= 3
      2788455.68     10198253.11      2788969.94     10197830.55
      2789355.67     10197803.11
#Sta/Elev= 30
  4334.4 1379.92  4490.1 1370.37  4654.4 1362.91  4668.8 1360.64  4689.6 1360.03
  4703.9 1358.01    4747 1357.82  4774.5 1354.86  4796.5 1354.48  4808.8 1351.51
  4809.1 1351.01  4812.8 1351.51  4817.3 1353.58  4831.6 1356.01  4924.2 1357.24
  4966.3 1355.43    5000 1354.18  5005.8 1352.57  5025.8  1352.7  5032.6 1355.06
    5106 1364.76    5149 1368.06  5162.2 1368.68  5201.7 1371.27  5266.4 1377.61
  5313.9 1386.83  5318.9 1385.96  5336.6 1388.73  5356.6 1389.04  5386.7 1391.97
#Mann= 7 ,-1 , 0
  4334.4     .05       0  4808.8     .07       0  4812.8     .05       0
  4966.3     .12       0    5149     .05       0  5162.2     .12       0
  5201.7     .05       0
Bank Sta=4808.8,4812.8
XS Rating Curve= 0 ,0
Exp/Cntr=0.3,0.1

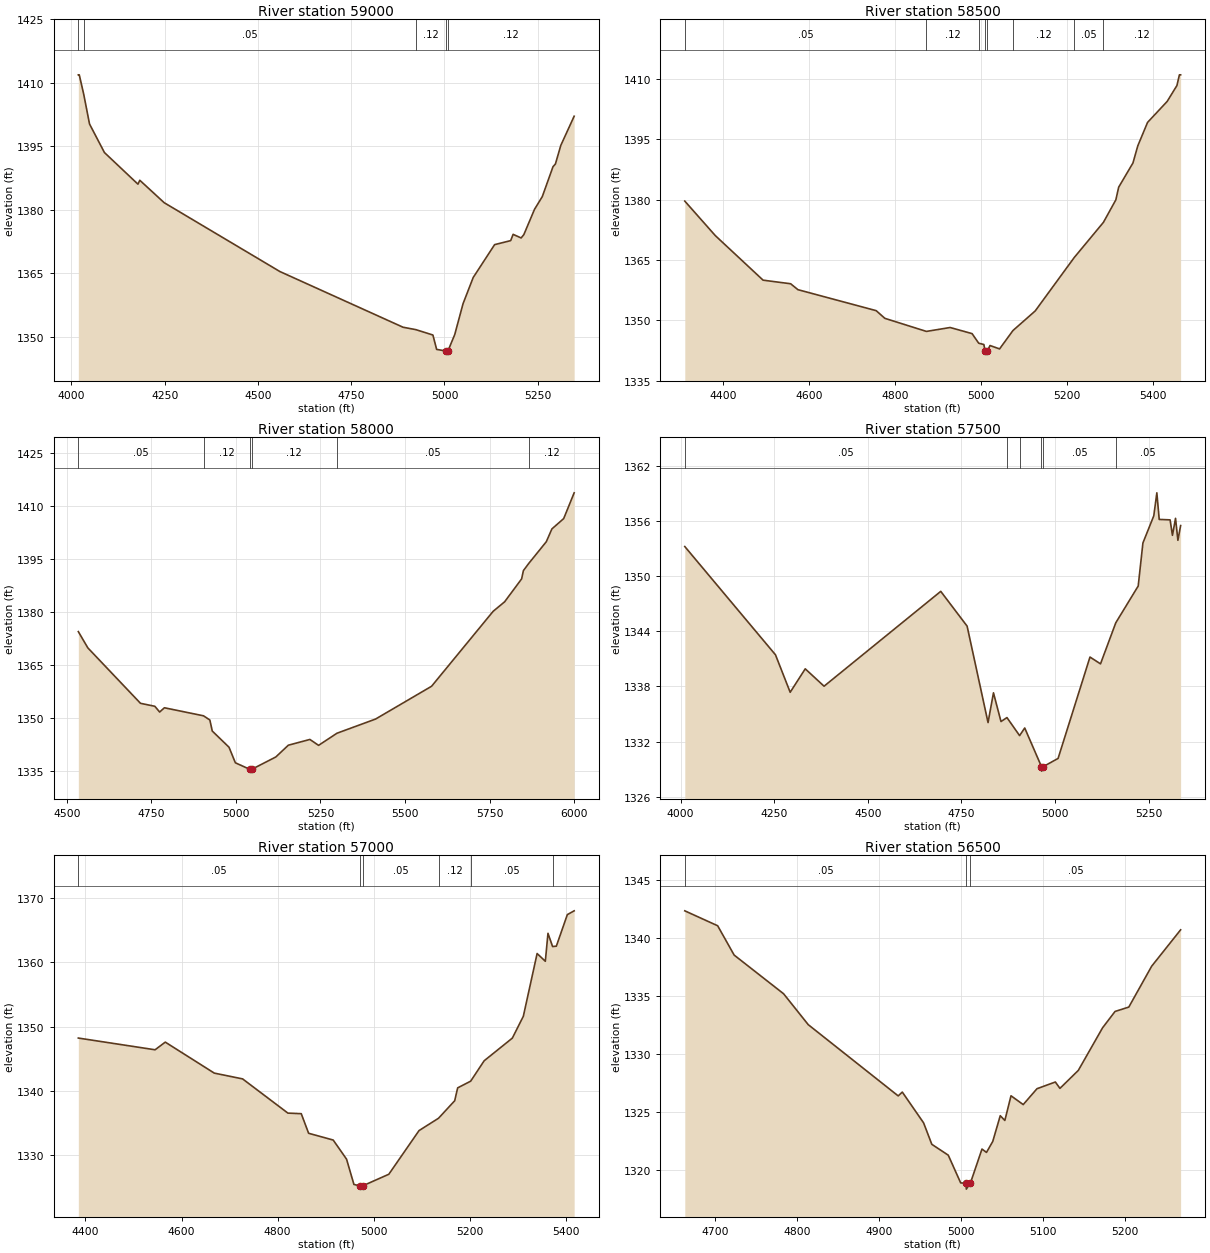
Type RM Length L Ch R = 1 ,59000   ,500,500,500
BEGIN DESCRIPTION:
SIXMILE CREEK 118.0
END DESCRIPTION:
XS GIS Cut Line= 3
      2788205.68     10198303.11      2789186.53     10198273.28
      2789455.66     10198053.13
#Sta/Elev= 30
  4018.7  1411.9  4021.2  1411.9  4033.1 1407.33  4048.7 1400.28  4088.7 1393.53
  4178.5 1386.06  4183.5 1386.98  4248.8 1381.68    4559 1365.41  4889.1 1352.25
  4923.4 1351.68  4969.1 1350.41  4979.1 1347.01  5004.2 1346.63  5004.6 1346.13
  5009.3 1346.63  5027.6 1350.51  5049.8 1357.79  5077.1    1364  5134.5 1371.77
  5177.6 1372.72  5184.1  1374.2  5205.6 1373.35  5212.8 1374.13  5241.5 1380.12
  5262.3 1383.12    5291 1390.19  5297.5 1390.83  5311.8  1395.2  5347.7 1402.12
#Mann= 5 ,-1 , 0
  4018.7     .12       0  4033.1     .05       0  4923.4     .12       0
  5004.2     .07       0  5009.3     .12       0
Bank Sta=5004.2,5009.3
XS Rating Curve= 0 ,0
Exp/Cntr=0.3,0.1

Type RM Length L Ch R = 1 ,58500   ,500,500,500
BEGIN DESCRIPTION:
SIXMILE CREEK 117.0
END DESCRIPTION:
XS GIS Cut Line= 3
      2788605.64     10198653.11      2789287.03     10198751.79
      2789705.68     10198553.11
#Sta/Elev= 30
  4311.5 1379.64  4382.3 1371.07  4493.4 1359.98  4557.4 1359.09  4574.3 1357.62
  4756.1  1352.4  4776.3 1350.49  4872.8 1347.24  4927.9 1348.21  4978.9 1346.69
  4994.3 1344.31  5006.3 1343.98  5009.2 1342.34  5009.6 1341.84  5014.4 1342.34
  5020.6 1343.73  5042.8 1342.89  5073.9 1347.46  5125.5 1352.32  5216.3 1365.62
    5284 1374.35  5312.9 1379.95  5319.5  1383.1  5352.7 1389.13  5363.9 1393.38
  5386.6 1399.21  5432.1 1404.42  5454.8 1408.38  5460.6 1411.04  5463.4 1411.04
#Mann= 8 ,-1 , 0
  4311.5     .05       0  4872.8     .12       0  4994.3     .05       0
  5009.2     .05       0  5014.4     .05       0  5073.9     .12       0
  5216.3     .05       0    5284     .12       0
Bank Sta=5009.2,5014.4
XS Rating Curve= 0 ,0
Exp/Cntr=0.3,0.1

Type RM Length L Ch R = 1 ,58000   ,500,500,500
BEGIN DESCRIPTION:
SIXMILE CREEK 116.0
END DESCRIPTION:
XS GIS Cut Line= 3
      2788605.69     10198753.12      2788932.93     10199084.74
      2789905.73      10198853.1
#Sta/Elev= 30
  4534.1 1374.34  4562.3 1369.73  4717.9 1354.04  4760.3  1353.2  4774.5 1351.57
  4788.6 1352.78  4904.3  1350.5    4923 1349.31  4930.1 1346.19  4979.6 1341.61
  4998.4  1337.2  5041.4 1335.34  5041.8 1334.84  5046.6 1335.34    5118 1338.85
    5155 1342.18  5218.7 1343.81  5244.4 1342.14  5298.8 1345.57    5413 1349.59
  5578.5 1358.87  5760.5 1380.09  5794.4 1382.78  5844.7 1389.27  5849.9 1391.61
  5865.3 1393.59  5917.7  1399.8  5934.2 1403.42  5969.1 1406.35    6000 1413.64
#Mann= 6 ,-1 , 0
  4534.1     .05       0  4904.3     .12       0  5041.4     .07       0
  5046.6     .12       0  5298.8     .05       0  5865.3     .12       0
Bank Sta=5041.4,5046.6
XS Rating Curve= 0 ,0
Exp/Cntr=0.3,0.1

Type RM Length L Ch R = 1 ,57500   ,500,500,500
BEGIN DESCRIPTION:
SIXMILE CREEK 115.0
END DESCRIPTION:
XS GIS Cut Line= 3
      2788205.73     10199303.12      2789189.28     10199406.82
      2789455.71     10199203.09
#Sta/Elev= 30
    4011  1353.2  4253.3 1341.43  4292.5 1337.36  4332.7 1339.91    4383 1338.02
  4694.7 1348.33  4765.1 1344.55    4821 1334.07  4835.5  1337.3  4855.6 1334.18
  4871.5 1334.61  4905.3 1332.65    4919 1333.48  4963.6 1329.29    4964 1328.79
  4968.9 1329.29  5008.1 1330.17  5093.3 1341.19  5121.4 1340.45  5162.3 1344.92
  5222.1 1348.91  5234.7 1353.59  5263.7 1356.54  5271.9 1359.04  5278.2 1356.15
  5307.3  1356.1  5313.6 1354.42  5321.8 1356.27  5328.1 1353.88  5335.4 1355.48
#Mann= 6 ,-1 , 0
    4011     .05       0  4871.5     .12       0  4905.3     .05       0
  4963.6     .07       0  4968.9     .05       0  5162.3     .05       0
Bank Sta=4963.6,4968.9
XS Rating Curve= 0 ,0
Exp/Cntr=0.3,0.1

Type RM Length L Ch R = 1 ,57000   ,500,500,500
BEGIN DESCRIPTION:
SIXMILE CREEK 114.0
END DESCRIPTION:
XS GIS Cut Line= 3
      2788905.68     10199503.11      2789427.06     10199828.89
      2789805.65     10199653.13
#Sta/Elev= 30
  4385.2 1348.21    4545 1346.39  4566.2 1347.58  4668.2 1342.77  4727.2 1341.87
  4821.5 1336.56  4849.3 1336.47  4864.6 1333.43  4915.8 1332.38  4943.6 1329.41
  4958.9 1325.49  4971.6 1325.26    4972 1324.76  4976.9 1325.26  5031.6 1327.07
  5094.5 1333.85    5135 1335.76  5168.7 1338.48  5174.9 1340.48    5202 1341.52
    5230 1344.68  5288.7  1348.2  5311.6 1351.59  5340.3 1361.33  5357.4 1360.13
  5362.9 1364.47  5372.5 1362.42  5380.3 1362.47  5403.2 1367.37  5417.4 1367.96
#Mann= 6 ,-1 , 0
  4385.2     .05       0  4971.6     .05       0  4976.9     .05       0
    5135     .12       0    5202     .05       0  5372.5     .12       0
Bank Sta=4971.6,4976.9
XS Rating Curve= 0 ,0
Exp/Cntr=0.3,0.1

Type RM Length L Ch R = 1 ,56500   ,500,500,500
BEGIN DESCRIPTION:
SIXMILE CREEK 113.0
END DESCRIPTION:
XS GIS Cut Line= 3
      2789055.69     10199703.16      2789087.48     10200038.15
      2789207.09     10200278.32
#Sta/Elev= 30
  4663.5 1342.34  4703.6 1341.05  4723.7 1338.52    4784 1335.18  4814.1 1332.51
  4923.8 1326.36  4928.8 1326.69  4954.8 1324.03  4964.8 1322.18  4984.9 1321.24
    5000 1318.85  5006.5 1318.81  5006.9 1318.31  5011.8 1318.81    5026 1321.77
  5031.5 1321.48  5039.1 1322.42  5048.3 1324.65  5053.9 1324.24  5061.4 1326.37
  5076.3 1325.61  5093.1 1326.98  5115.5 1327.56  5121.1 1327.01  5143.5 1328.56
  5173.1 1332.24  5188.3 1333.65  5205.1 1334.03    5233 1337.56  5268.3  1340.7
#Mann= 3 ,-1 , 0
  4663.5     .05       0  5006.5     .03       0  5011.8     .05       0
Bank Sta=5006.5,5011.8
XS Rating Curve= 0 ,0
Exp/Cntr=0.3,0.1

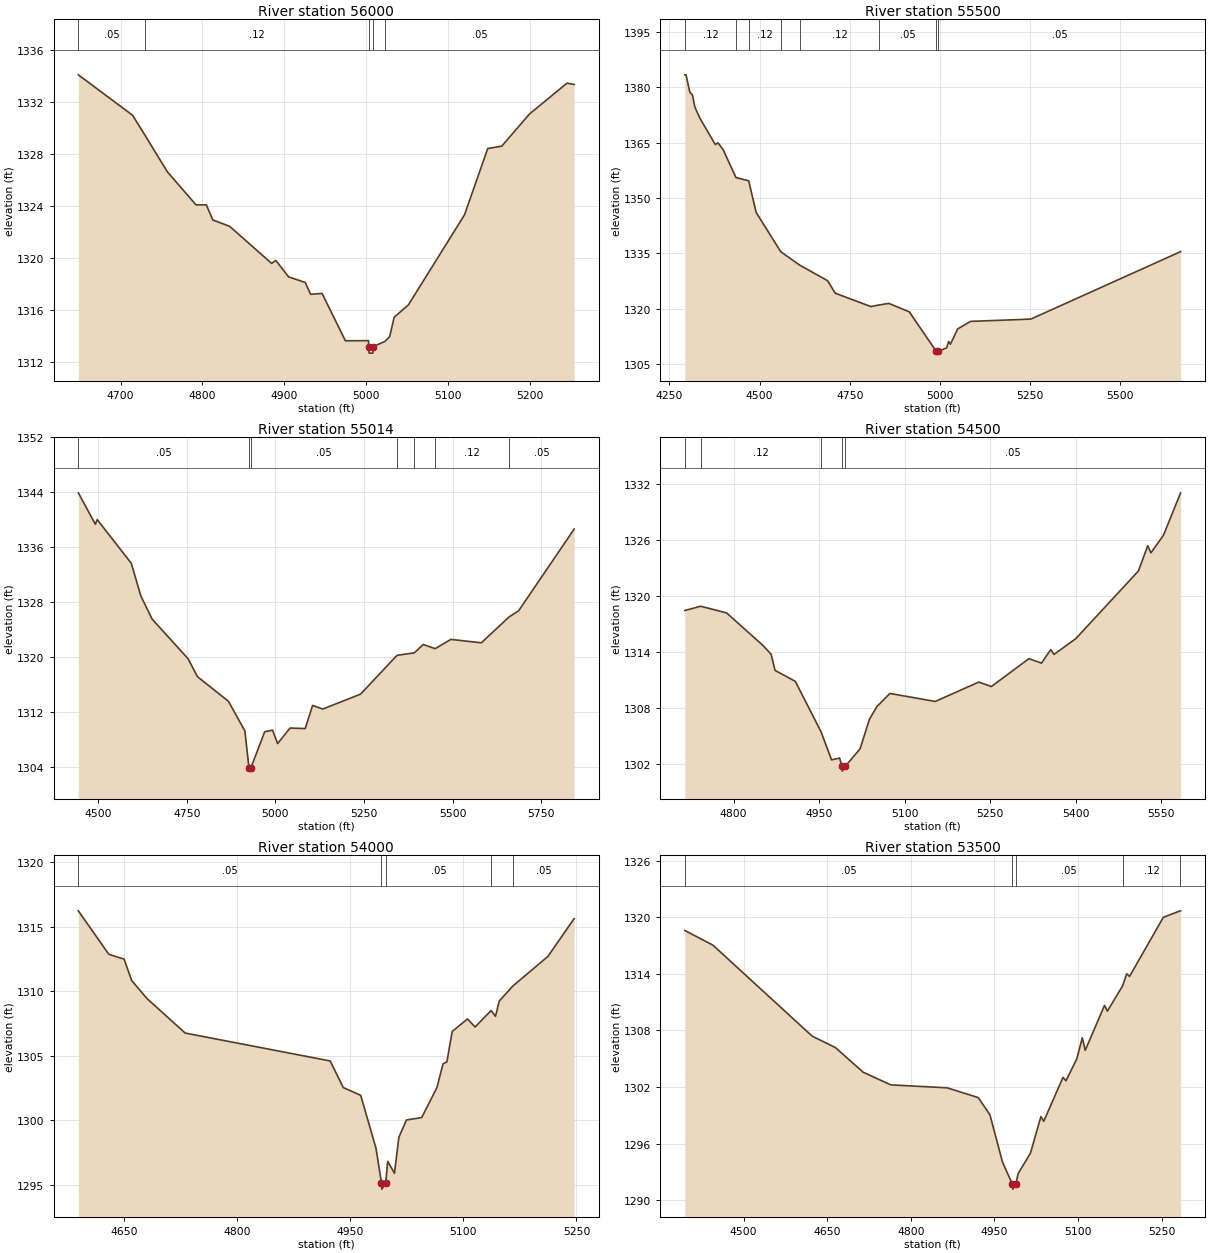
Type RM Length L Ch R = 1 ,56000   ,500,500,500
BEGIN DESCRIPTION:
SIXMILE CREEK 112.0
END DESCRIPTION:
XS GIS Cut Line= 3
      2788705.69      10199853.1      2788625.53     10200195.54
      2788855.73     10200303.13
#Sta/Elev= 30
  4648.3  1334.1  4714.6 1330.99  4729.2 1329.51  4757.1 1326.64  4792.1  1324.1
  4804.7  1324.1  4812.6 1322.94  4833.2 1322.45  4884.5  1319.6  4889.6 1319.83
  4905.1 1318.57  4925.6 1318.13  4932.1 1317.22  4946.1 1317.29  4974.6 1313.65
  5002.8 1313.66  5003.2  1313.2  5003.6  1312.7  5008.1  1312.7  5008.6  1313.2
  5022.9  1313.6  5028.7 1313.97  5034.2 1315.46  5051.6 1316.41  5120.1 1323.33
  5148.5 1328.43  5165.7 1328.62  5199.7  1331.1  5245.4 1333.46  5254.1 1333.36
#Mann= 5 ,-1 , 0
  4648.3     .05       0  4729.2     .12       0  5003.2     .07       0
  5008.6     .12       0  5022.9     .05       0
Bank Sta=5003.2,5008.6
XS Rating Curve= 0 ,0
Exp/Cntr=0.3,0.1

Type RM Length L Ch R = 1 ,55500   ,486,486,486
BEGIN DESCRIPTION:
SIXMILE CREEK 111.0
END DESCRIPTION:
XS GIS Cut Line= 3
      2787755.72     10200003.15       2788246.9     10200512.08
      2788905.65     10200403.12
#Sta/Elev= 30
  4292.7 1383.39  4296.1 1383.39  4306.7 1378.68  4313.9 1377.94  4320.8 1374.59
    4335 1371.56  4377.4 1364.48  4384.6 1364.97  4398.8 1363.15  4434.7 1355.55
  4469.9 1354.68  4490.6  1346.1  4558.9 1335.45  4612.4 1331.77  4688.7 1327.61
  4709.8 1324.22  4808.8 1320.59  4831.1 1321.02  4858.5 1321.45  4915.1 1319.18
    4990 1308.48  4990.4 1307.98  4995.6 1308.48    5019 1309.41  5024.2 1311.15
  5029.3 1310.39  5049.4 1314.54  5085.3 1316.58  5252.2  1317.2  5667.7 1335.48
#Mann= 8 ,-1 , 0
  4292.7     .12       0  4434.7     .05       0  4469.9     .12       0
  4558.9     .05       0  4612.4     .12       0  4831.1     .05       0
    4990     .05       0  4995.6     .05       0
Bank Sta=4990,4995.6
XS Rating Curve= 0 ,0
Exp/Cntr=0.3,0.1

Type RM Length L Ch R = 1 ,55014   ,514,514,514
BEGIN DESCRIPTION:
SIXMILE CREEK 110.0
END DESCRIPTION:
XS GIS Cut Line= 3
      2787805.67     10200903.11      2788206.37      10201032.4
      2788955.65     10200403.14
#Sta/Elev= 30
  4443.8 1343.94  4491.9 1339.36  4497.1 1340.04  4593.3 1333.68  4620.1 1328.95
  4652.1 1325.55  4753.5 1319.79  4780.1 1317.17  4867.7 1313.58  4913.9 1309.27
  4925.4 1303.92  4925.9 1303.42    4931 1303.92  4969.9 1309.16    4992 1309.38
  5006.3 1307.44  5041.4 1309.69  5084.3 1309.62  5105.1 1312.99  5133.8 1312.46
  5240.4 1314.63  5343.4 1320.28  5392.1 1320.64  5417.3 1321.86  5450.9 1321.25
  5495.4  1322.6  5581.2  1322.1  5659.8 1325.88  5686.6 1326.77  5843.3 1338.66
#Mann= 7 ,-1 , 0
  4443.8     .05       0  4925.4     .05       0    4931     .05       0
  5343.4     .12       0  5392.1     .05       0  5450.9     .12       0
  5659.8     .05       0
Bank Sta=4925.4,4931
XS Rating Curve= 0 ,0
Exp/Cntr=0.3,0.1

Type RM Length L Ch R = 1 ,54500   ,500,500,500
BEGIN DESCRIPTION:
SIXMILE CREEK 109.0
END DESCRIPTION:
XS GIS Cut Line= 3
      2788574.75     10201316.07      2788781.02     10201118.39
      2789055.68     10200603.12
#Sta/Elev= 30
  4714.3 1318.44  4742.2  1318.9  4787.7 1318.18  4851.5 1314.69  4865.7 1313.75
  4872.6 1312.02  4908.1 1310.85  4953.1 1305.46  4971.7 1302.43  4985.8 1302.62
  4989.9 1301.72  4990.4 1301.22  4995.5 1301.72  5021.8 1303.62  5038.1 1306.78
  5051.3 1308.14    5074 1309.55  5153.5 1308.69    5230 1310.77    5252 1310.29
  5317.9 1313.28  5339.9  1312.8  5356.1 1314.25  5361.8 1313.73  5400.1 1315.43
  5509.9 1322.68  5526.2 1325.39  5531.8 1324.63  5553.8 1326.51  5583.9 1331.06
#Mann= 5 ,-1 , 0
  4714.3     .05       0  4742.2     .12       0  4953.1     .05       0
  4989.9     .03       0  4995.5     .05       0
Bank Sta=4989.9,4995.5
XS Rating Curve= 0 ,0
Exp/Cntr=0.3,0.1

Type RM Length L Ch R = 1 ,54000   ,500,500,500
BEGIN DESCRIPTION:
SIXMILE CREEK 108.0
END DESCRIPTION:
XS GIS Cut Line= 3
      2788805.73      10201353.1      2789211.44     10201289.25
      2789455.68     10201253.11
#Sta/Elev= 30
  4589.3 1316.22  4629.7 1312.86    4650 1312.48  4660.1 1310.82  4680.4 1309.43
    4731 1306.76  4923.3  1304.6  4940.7 1302.54  4963.8 1301.94  4984.1 1297.84
  4991.3 1295.18  4991.8 1294.68    4997 1295.18  4999.6 1296.83  5008.6 1295.91
  5014.4 1298.69  5024.5 1300.03  5044.7 1300.22  5064.9 1302.54    5073 1304.38
  5078.1 1304.53  5085.2 1306.89  5105.4 1307.85  5115.5 1307.23  5136.7  1308.5
  5142.6 1308.06  5147.6 1309.24  5165.6  1310.4  5212.1 1312.69  5246.9 1315.62
#Mann= 5 ,-1 , 0
  4589.3     .05       0  4991.3     .05       0    4997     .05       0
  5136.7     .12       0  5165.6     .05       0
Bank Sta=4991.3,4997
XS Rating Curve= 0 ,0
Exp/Cntr=0.3,0.1

Type RM Length L Ch R = 1 ,53500   ,500,500,500
BEGIN DESCRIPTION:
SIXMILE CREEK 107.0
END DESCRIPTION:
XS GIS Cut Line= 3
      2788705.71     10201403.13      2789181.43     10201777.72
      2789455.67     10201703.12
#Sta/Elev= 30
  4394.5  1318.6    4445 1317.04    4623  1307.4  4664.7 1306.19  4714.4 1303.58
  4764.1 1302.23  4865.2 1301.92  4921.2 1300.88  4942.1 1299.05  4964.6 1294.04
  4982.5 1291.68    4983 1291.18  4988.2 1291.68  4992.7 1292.83  5014.8    1295
  5033.5 1298.87  5038.6 1298.37  5073.2 1303.03  5078.4 1302.66  5097.7 1304.96
  5107.8 1307.23    5113 1305.89  5147.6 1310.65  5152.8 1310.05    5180 1312.72
  5187.4 1314.01  5192.6 1313.73  5253.1 1319.99  5283.5 1320.68  5284.2 1320.68
#Mann= 5 ,-1 , 0
  4394.5     .05       0  4982.5     .05       0  4988.2     .05       0
    5180     .12       0  5283.5     .05       0
Bank Sta=4982.5,4988.2
XS Rating Curve= 0 ,0
Exp/Cntr=0.3,0.1