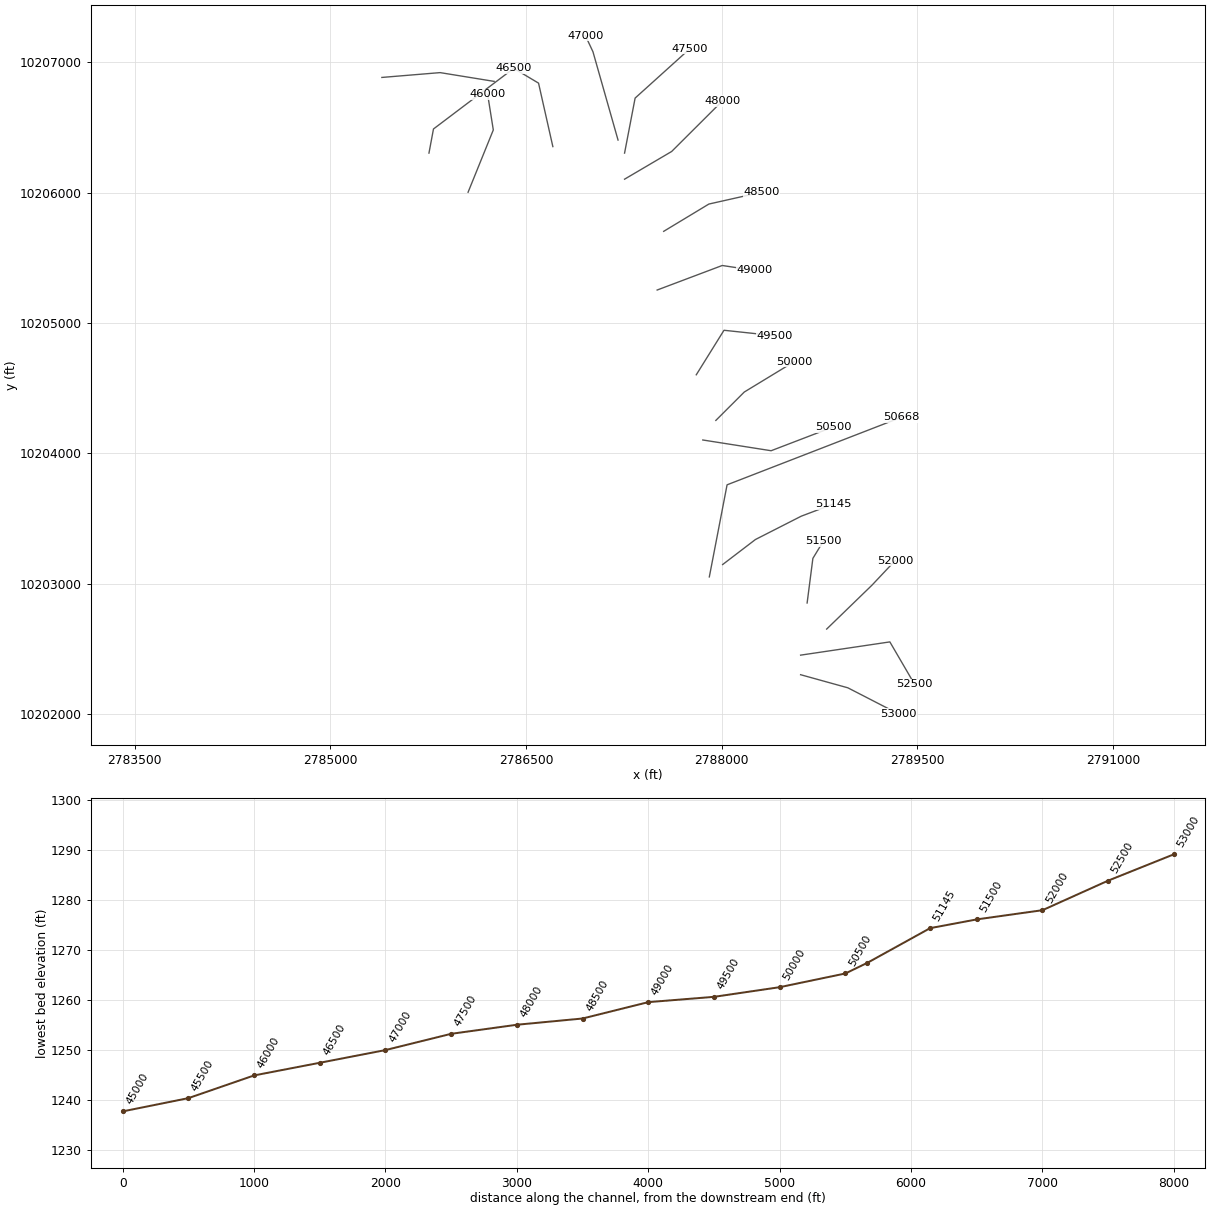
HEC-RAS study SIXMILE CREEK.prj: SIXMILE CREEK Base Level Engineering

--- SIXMILE CREEK.g01 (geometry) --- (continued)

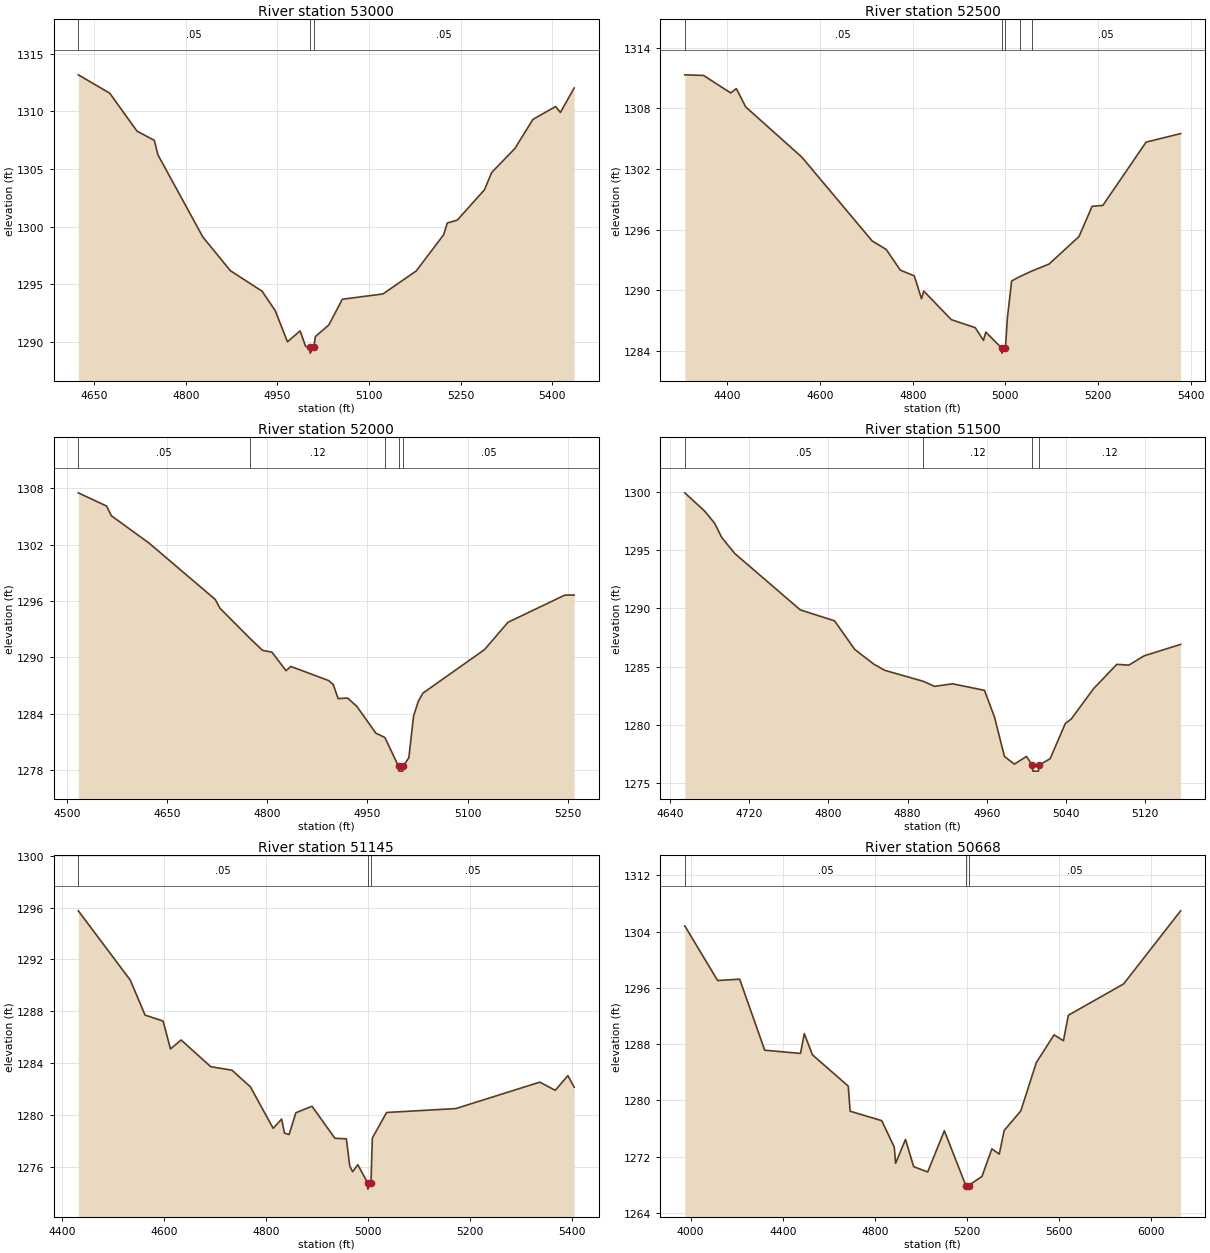
Type RM Length L Ch R = 1 ,53000   ,500,500,500
BEGIN DESCRIPTION:
SIXMILE CREEK 106.0
END DESCRIPTION:
XS GIS Cut Line= 3
      2788605.69     10202303.11       2788968.1     10202202.59
      2789355.68     10202003.11
#Sta/Elev= 30
  4623.9 1313.17  4675.3 1311.58    4720 1308.29  4748.4 1307.49  4754.2 1306.24
    4828  1299.1    4873 1296.19  4924.8 1294.42  4946.4 1292.73  4966.4 1290.03
  4987.1 1290.98  4996.2 1289.63    5003 1289.55  5003.5 1289.05  5009.6 1289.55
    5012 1290.48  5034.1 1291.49  5056.3 1293.72  5122.8 1294.18  5177.2 1296.17
  5222.2 1299.31  5228.1 1300.33  5244.6 1300.58    5289 1303.21  5300.9 1304.71
  5338.9 1306.79  5368.4 1309.31  5405.5 1310.42  5413.4 1309.91  5435.9 1312.03
#Mann= 3 ,-1 , 0
  4623.9     .05       0    5003     .05       0  5009.6     .05       0
Bank Sta=5003,5009.6
XS Rating Curve= 0 ,0
Exp/Cntr=0.3,0.1

Type RM Length L Ch R = 1 ,52500   ,500,500,500
BEGIN DESCRIPTION:
SIXMILE CREEK 105.0
END DESCRIPTION:
XS GIS Cut Line= 3
      2788605.68     10202453.11      2789290.19     10202554.67
      2789480.71     10202228.07
#Sta/Elev= 30
    4308  1311.3  4348.4 1311.24  4407.1 1309.51  4419.2 1309.94  4439.4 1308.13
  4560.7 1303.16  4712.4 1294.88  4742.7 1294.04    4773    1292  4803.4 1291.42
  4818.8 1289.17  4823.8 1289.92  4883.2  1287.1  4934.8 1286.31  4952.6 1285.05
  4957.7 1285.87  4991.8 1284.29  4992.3 1283.79  4998.5 1284.29    5000 1284.29
  5004.3 1287.31  5013.4 1290.92  5030.4 1291.34  5056.3 1291.89  5094.4  1292.6
  5158.9 1295.32    5187  1298.3  5210.2 1298.39  5303.6 1304.65  5378.1 1305.49
#Mann= 5 ,-1 , 0
    4308     .05       0  4991.8     .05       0  4998.5     .05       0
  5030.4     .12       0  5056.3     .05       0
Bank Sta=4991.8,4998.5
XS Rating Curve= 0 ,0
Exp/Cntr=0.3,0.1

Type RM Length L Ch R = 1 ,52000   ,500,500,500
BEGIN DESCRIPTION:
SIXMILE CREEK 104.0
END DESCRIPTION:
XS GIS Cut Line= 3
      2788805.68     10202653.11      2789152.56     10202989.21
      2789330.66     10203178.09
#Sta/Elev= 30
    4517  1307.5  4559.3 1306.09  4566.5 1305.06  4623.1 1302.14  4722.1 1296.15
  4729.1 1295.22    4774 1292.01  4792.9 1290.73    4807 1290.54  4828.1 1288.57
  4835.3 1289.02  4891.9 1287.52  4898.9 1287.08  4906.1  1285.6  4920.2 1285.66
  4934.3 1284.76  4962.6 1281.92  4976.1 1281.46  4996.7 1278.38  4997.2 1277.88
  5002.9 1277.88  5003.4 1278.38    5012 1279.31  5019.1 1283.75  5026.2 1285.31
  5033.1 1286.18  5125.3 1290.81  5160.5 1293.72  5245.5 1296.61  5259.6 1296.62
#Mann= 5 ,-1 , 0
    4517     .05       0    4774     .12       0  4976.1     .05       0
  4996.7     .05       0  5003.4     .05       0
Bank Sta=4996.7,5003.4
XS Rating Curve= 0 ,0
Exp/Cntr=0.3,0.1

Type RM Length L Ch R = 1 ,51500   ,355,355,355
BEGIN DESCRIPTION:
SIXMILE CREEK 103.0
END DESCRIPTION:
XS GIS Cut Line= 3
      2788655.68     10202853.11      2788699.84     10203195.18
      2788780.69     10203328.12
#Sta/Elev= 30
  4655.1 1299.91  4675.3 1298.33  4685.3 1297.29  4692.3 1296.09  4705.5 1294.71
  4771.7 1289.87  4806.3 1288.93  4826.5 1286.49    4846 1285.21  4856.8 1284.69
  4895.6 1283.75  4907.2 1283.31  4925.4 1283.53  4957.6 1282.97  4967.7 1280.68
  4977.8 1277.29  4987.8 1276.64    5000  1277.3  5005.9 1276.54  5006.4 1276.04
  5012.1 1276.04  5012.6 1276.54  5023.9 1277.11  5039.3 1280.14  5045.2 1280.51
  5067.8 1283.12  5091.2  1285.2  5103.3 1285.13  5118.8 1285.93  5155.6 1286.91
#Mann= 4 ,-1 , 0
  4655.1     .05       0  4895.6     .12       0  5005.9     .07       0
  5012.6     .12       0
Bank Sta=5005.9,5012.6
XS Rating Curve= 0 ,0
Exp/Cntr=0.3,0.1

Type RM Length L Ch R = 1 ,51145   ,477,477,477
BEGIN DESCRIPTION:
Mapping XS 62c18ccd
END DESCRIPTION:
XS GIS Cut Line= 4
       2788007.8     10203147.85      2788259.39     10203339.86
       2788610.3     10203518.62      2788855.25      10203611.3
#Sta/Elev= 30
  4432.6 1295.75  4534.4 1290.41  4563.5 1287.71  4598.8 1287.25  4613.3  1285.1
  4634.2 1285.79  4692.3 1283.73  4733.9 1283.46  4770.1 1282.17  4814.6 1278.98
  4831.2 1279.69  4836.8 1278.61  4845.9  1278.5  4859.1 1280.18  4890.8 1280.68
  4935.7 1278.21  4958.2 1278.17  4964.7 1276.09  4970.3 1275.63  4980.6 1276.17
  4999.7 1274.79  5000.2 1274.29  5006.4 1274.79  5009.1 1278.23    5037  1280.2
  5172.6  1280.5  5337.5 1282.54  5367.7 1281.91  5392.5 1283.04  5404.8 1282.15
#Mann= 3 ,-1 , 0
  4432.6     .05       0  4999.7     .05       0  5006.4     .05       0
Bank Sta=4999.7,5006.4
XS Rating Curve= 0 ,0
Exp/Cntr=0.3,0.1

Type RM Length L Ch R = 1 ,50668   ,168,168,168
BEGIN DESCRIPTION:
SIXMILE CREEK 102.0
END DESCRIPTION:
XS GIS Cut Line= 3
      2787905.69     10203053.13      2788041.85     10203759.28
      2789380.67     10204278.11
#Sta/Elev= 30
  3974.5 1304.81  4117.1 1297.04    4213 1297.23  4321.8 1287.13  4477.4 1286.67
  4493.9 1289.49  4529.3 1286.47  4684.9 1282.02  4693.1 1278.45  4830.3 1277.11
  4884.8 1273.36  4890.8 1271.04  4933.7 1274.44  4969.2 1270.57  5030.2 1269.81
  5102.7 1275.67  5196.1 1267.87  5196.6 1267.37  5207.6 1267.87  5266.2 1269.18
  5309.1  1273.1  5341.3 1272.35  5362.7 1275.71    5435  1278.5  5502.1 1285.35
  5579.3 1289.31  5620.1 1288.48  5641.5  1292.1  5881.6 1296.55  6129.5 1306.95
#Mann= 3 ,-1 , 0
  3974.5     .05       0  5196.1     .05       0  5207.6     .05       0
Bank Sta=5196.1,5207.6
XS Rating Curve= 0 ,0
Exp/Cntr=0.3,0.1

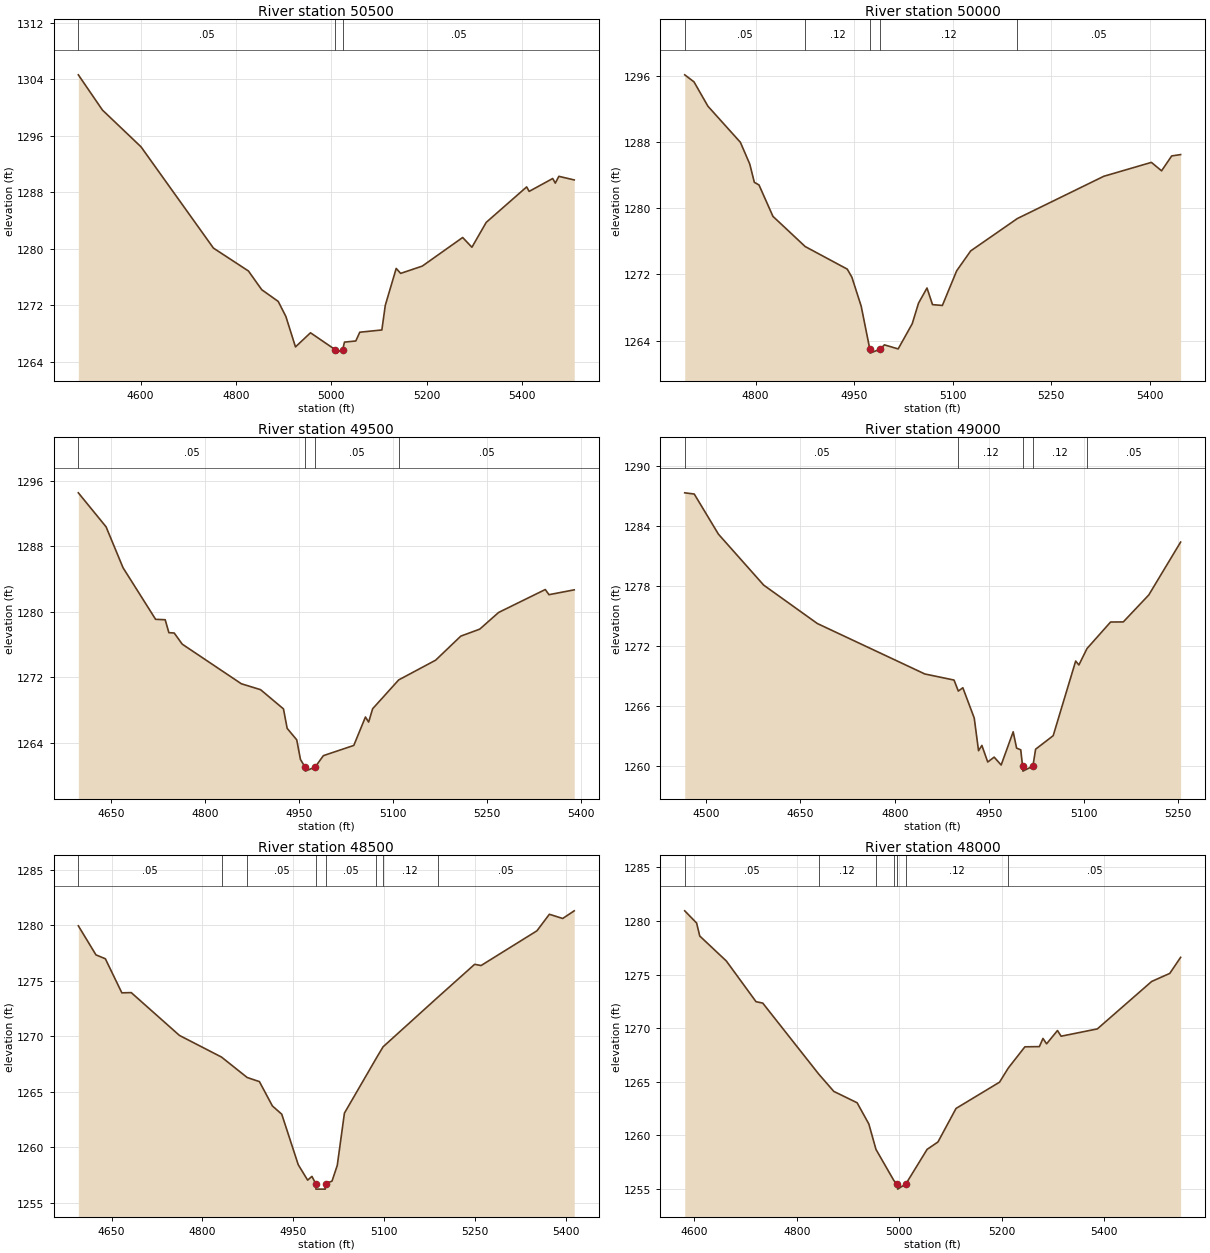
Type RM Length L Ch R = 1 ,50500   ,500,500,500
BEGIN DESCRIPTION:
SIXMILE CREEK 101.0
END DESCRIPTION:
XS GIS Cut Line= 3
      2787855.69     10204103.11      2788379.66     10204020.74
      2788855.72     10204203.12
#Sta/Elev= 30
  4469.6 1304.63  4520.2 1299.64  4601.2 1294.43    4753  1280.1  4826.4 1276.86
  4854.3 1274.21  4888.9 1272.55  4904.9 1270.43  4925.1 1266.11  4956.6 1268.11
  5008.3 1265.73  5008.8 1265.23  5024.1 1265.73  5027.9 1266.79  5051.6 1266.95
    5060 1268.19  5106.3 1268.51  5113.5    1272  5136.4 1277.22  5145.7 1276.52
  5191.1 1277.55  5275.8  1281.6  5295.2 1280.22  5325.2 1283.74    5410 1288.76
  5415.3 1288.13  5464.7 1289.95  5470.1  1289.3  5477.6 1290.26  5509.8 1289.75
#Mann= 3 ,-1 , 0
  4469.6     .05       0  5008.3     .03       0  5024.1     .05       0
Bank Sta=5008.3,5024.1
XS Rating Curve= 0 ,0
Exp/Cntr=0.3,0.1

Type RM Length L Ch R = 1 ,50000   ,500,500,500
BEGIN DESCRIPTION:
SIXMILE CREEK 100.0
END DESCRIPTION:
XS GIS Cut Line= 3
      2787955.71     10204253.14      2788173.65     10204470.77
      2788555.65     10204703.09
#Sta/Elev= 30
    4692 1296.12  4706.1 1295.27  4727.3 1292.33  4776.8 1287.96    4791 1285.34
    4798 1283.13  4805.1 1282.81  4826.3 1279.02  4875.4 1275.37  4939.5 1272.64
  4946.5 1271.67  4960.7 1268.16  4973.8 1262.99  4974.3 1262.49    4990 1262.99
    4996 1263.49    5017    1263  5038.4 1266.04    5048 1268.53  5060.9 1270.36
  5069.3 1268.35  5084.3 1268.25  5106.1 1272.44  5127.4 1274.84  5198.4 1278.75
  5330.1 1283.86  5402.6 1285.54  5418.1 1284.52  5433.5 1286.32  5447.1 1286.48
#Mann= 5 ,-1 , 0
    4692     .05       0  4875.4     .12       0  4973.8     .07       0
    4990     .12       0  5198.4     .05       0
Bank Sta=4973.8,4990
XS Rating Curve= 0 ,0
Exp/Cntr=0.3,0.1

Type RM Length L Ch R = 1 ,49500   ,500,500,500
BEGIN DESCRIPTION:
SIXMILE CREEK 99.0
END DESCRIPTION:
XS GIS Cut Line= 3
      2787805.67     10204603.09      2788018.13     10204944.48
      2788405.73     10204903.11
#Sta/Elev= 30
  4597.9 1294.55  4642.2  1290.4  4669.3  1285.4  4721.3  1279.1  4736.6 1279.05
  4742.5 1277.47    4751 1277.43  4763.8 1276.07  4858.2 1271.23  4888.9 1270.51
  4925.5 1268.16  4931.4 1265.78  4946.7 1264.38  4952.6 1261.99  4959.9 1261.06
  4960.4 1260.56  4976.1 1261.06  4989.2 1262.45  5037.8  1263.7  5056.4 1267.17
  5061.5 1266.55  5067.9 1268.18  5109.5  1271.7  5168.5 1274.11  5208.7 1277.05
  5238.9  1277.9  5269.1 1279.94  5343.6 1282.74  5349.5 1282.11  5389.8  1282.7
#Mann= 4 ,-1 , 0
  4597.9     .05       0  4959.9     .07       0  4976.1     .05       0
  5109.5     .05       0
Bank Sta=4959.9,4976.1
XS Rating Curve= 0 ,0
Exp/Cntr=0.3,0.1

Type RM Length L Ch R = 1 ,49000   ,500,500,500
BEGIN DESCRIPTION:
SIXMILE CREEK 98.0
END DESCRIPTION:
XS GIS Cut Line= 3
      2787505.64      10205253.1      2788004.75     10205441.26
      2788255.67     10205403.11
#Sta/Elev= 30
  4466.6 1287.31  4481.7 1287.19  4520.1 1283.18  4591.9 1278.09  4677.1 1274.25
  4847.7 1269.21  4894.1  1268.6  4900.9  1267.5  4908.1 1267.83  4926.2  1264.8
    4933 1261.54  4938.3 1262.07  4947.6 1260.41  4957.8  1260.9  4968.9 1260.11
    4988 1263.43  4993.4  1261.8    5000 1261.63  5002.9    1260  5003.4  1259.5
  5019.3    1260  5023.6 1261.69  5051.5 1263.04  5087.2  1270.5  5092.3 1270.11
  5105.2 1271.75  5142.6  1274.4  5162.8 1274.41  5203.2  1277.1  5253.8 1282.39
#Mann= 5 ,-1 , 0
  4466.6     .05       0  4900.9     .12       0  5002.9     .07       0
  5019.3     .12       0  5105.2     .05       0
Bank Sta=5002.9,5019.3
XS Rating Curve= 0 ,0
Exp/Cntr=0.3,0.1

Type RM Length L Ch R = 1 ,48500   ,500,500,500
BEGIN DESCRIPTION:
SIXMILE CREEK 97.0
END DESCRIPTION:
XS GIS Cut Line= 3
      2787555.71     10205703.13      2787902.21     10205912.41
      2788305.64      10206003.1
#Sta/Elev= 30
  4595.2 1279.96  4624.3 1277.34  4639.8 1276.99    4667 1273.92  4682.5 1273.94
  4762.1 1270.08  4831.5 1268.13  4873.8 1266.29    4894 1265.92  4915.4 1263.73
  4930.9 1262.98  4958.1 1258.43  4973.6 1257.04  4980.7 1257.38  4986.8 1256.73
  4987.3 1256.23  5002.7 1256.23  5003.2 1256.73  5013.8 1256.95  5022.5 1258.37
  5034.3 1263.08  5087.2 1268.06    5098 1269.05  5188.2 1273.51  5249.2 1276.49
  5259.8 1276.38    5352 1279.51  5372.5    1281  5394.5 1280.62  5413.5 1281.31
#Mann= 8 ,-1 , 0
  4595.2     .05       0  4831.5     .12       0  4873.8     .05       0
  4986.8     .07       0  5003.2     .05       0  5087.2     .05       0
    5098     .12       0  5188.2     .05       0
Bank Sta=4986.8,5003.2
XS Rating Curve= 0 ,0
Exp/Cntr=0.3,0.1

Type RM Length L Ch R = 1 ,48000   ,500,500,500
BEGIN DESCRIPTION:
SIXMILE CREEK 96.0
END DESCRIPTION:
XS GIS Cut Line= 3
      2787255.66      10206103.1      2787616.74     10206315.46
      2788005.66     10206703.09
#Sta/Elev= 30
  4581.1 1280.95  4604.3 1279.81  4610.4  1278.6  4662.3 1276.27  4720.3 1272.47
  4733.4 1272.34  4842.6 1265.72  4872.1  1264.1  4917.6 1263.04  4940.5 1261.06
  4954.4 1258.69  4989.6 1255.76  4996.3 1255.48  4996.8 1254.98    5013 1255.48
  5054.2 1258.69  5075.4 1259.38  5110.7 1262.51  5195.6 1264.96  5212.7 1266.28
  5245.1 1268.26  5273.4 1268.28  5280.4 1269.04  5287.5 1268.54  5308.7 1269.78
  5315.8 1269.25  5386.5 1269.93  5492.6 1274.36  5527.9 1275.11  5549.1 1276.61
#Mann= 7 ,-1 , 0
  4581.1     .05       0  4842.6     .12       0  4954.4     .05       0
  4989.6     .12       0  4996.3     .07       0    5013     .12       0
  5212.7     .05       0
Bank Sta=4996.3,5013
XS Rating Curve= 0 ,0
Exp/Cntr=0.3,0.1

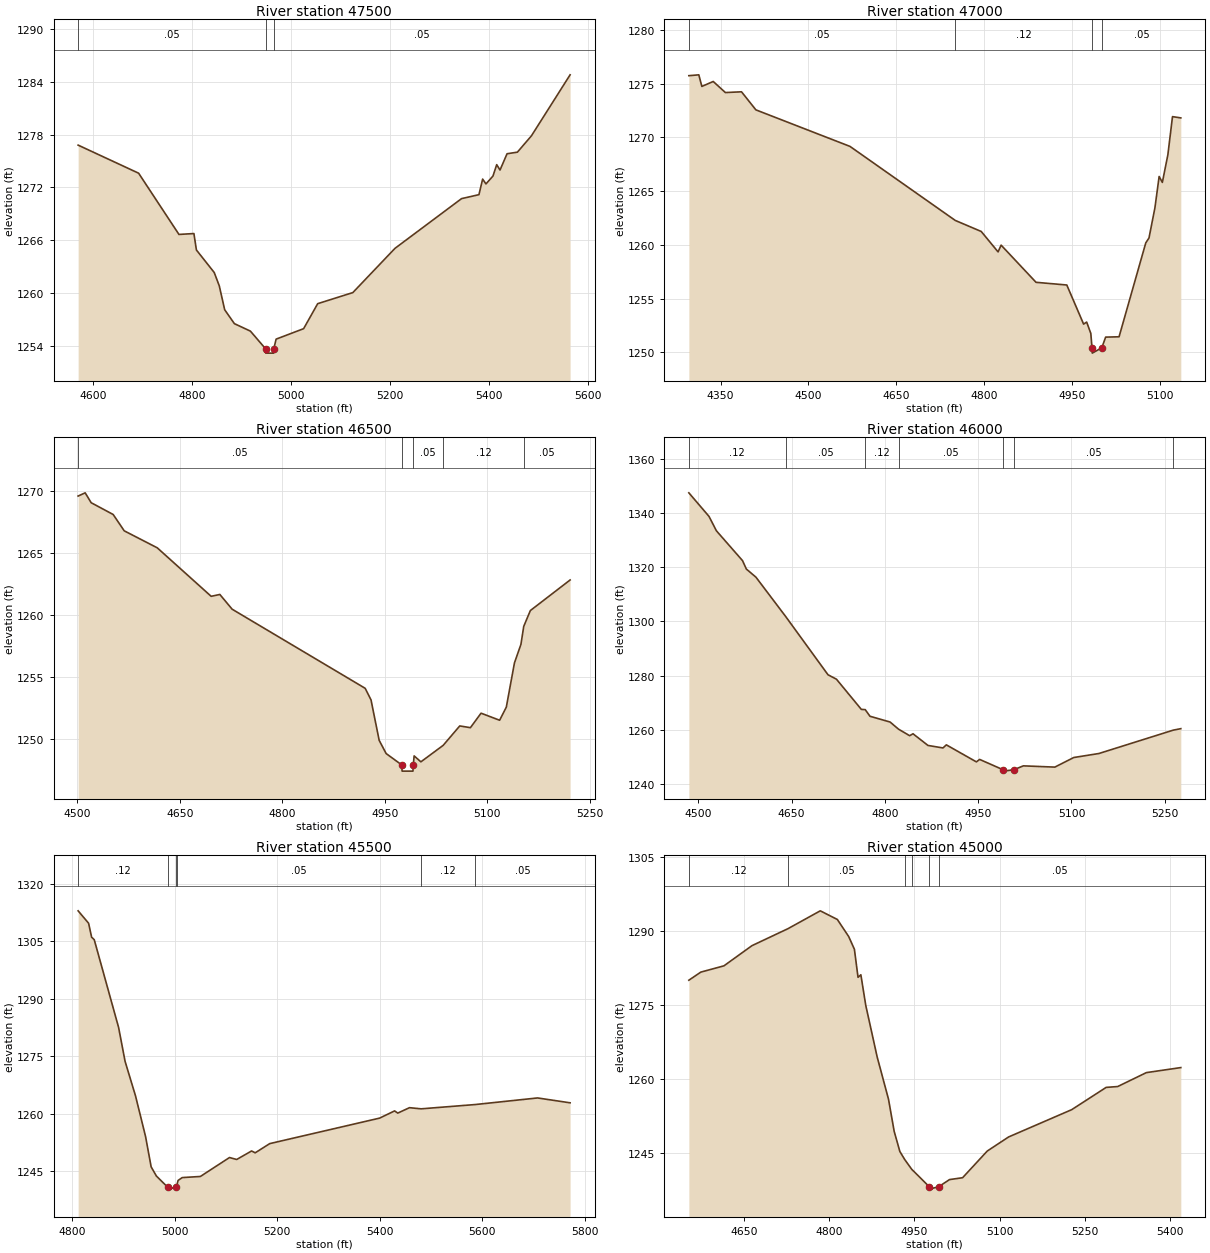
Type RM Length L Ch R = 1 ,47500   ,500,500,500
BEGIN DESCRIPTION:
SIXMILE CREEK 95.0
END DESCRIPTION:
XS GIS Cut Line= 3
      2787255.68     10206303.07      2787336.67     10206724.97
      2787755.67      10207103.1
#Sta/Elev= 30
  4570.4 1276.81  4692.6 1273.62  4774.1 1266.66  4804.3 1266.76  4809.4 1264.89
  4845.4 1262.33  4855.6 1260.81  4866.5  1258.1  4886.1 1256.52  4918.5 1255.67
    4949 1253.67  4949.5 1253.17  4965.2 1253.17  4965.7 1253.67  4970.4 1254.76
    5026 1255.95  5054.4 1258.79  5125.4 1260.05  5210.6 1265.08  5345.1 1270.73
  5380.2 1271.18  5387.7 1272.95  5394.4  1272.4  5408.6  1273.3  5416.1 1274.59
  5422.8 1273.98    5437 1275.83  5457.9 1276.01  5486.3 1277.87  5564.4  1284.8
#Mann= 3 ,-1 , 0
  4570.4     .05       0    4949     .05       0  4965.7     .05       0
Bank Sta=4949,4965.7
XS Rating Curve= 0 ,0
Exp/Cntr=0.3,0.1

Type RM Length L Ch R = 1 ,47000   ,500,500,500
BEGIN DESCRIPTION:
SIXMILE CREEK 94.0
END DESCRIPTION:
XS GIS Cut Line= 3
      2787205.69      10206403.1      2787013.27     10207080.51
      2786955.67     10207203.15
#Sta/Elev= 30
  4295.8 1275.74  4312.8 1275.82    4318 1274.74  4337.4  1275.2  4358.2 1274.17
  4385.7 1274.24  4410.2 1272.56  4570.8 1269.16  4750.5 1262.27  4794.9 1261.24
  4823.6 1259.34  4828.8 1259.97  4888.4 1256.51  4940.9 1256.26  4969.6 1252.62
  4974.8 1252.81  4981.9 1251.75  4983.9 1250.42  4984.4 1249.92  5000.7 1250.42
  5007.2 1251.41  5030.1 1251.44  5075.7 1260.18  5081.2 1260.64  5091.3 1263.44
  5098.5 1266.36    5104 1265.81  5113.4 1268.38  5121.3 1271.93  5135.5 1271.81
#Mann= 4 ,-1 , 0
  4295.8     .05       0  4750.5     .12       0  4983.9     .05       0
  5000.7     .05       0
Bank Sta=4983.9,5000.7
XS Rating Curve= 0 ,0
Exp/Cntr=0.3,0.1

Type RM Length L Ch R = 1 ,46500   ,500,500,500
BEGIN DESCRIPTION:
SIXMILE CREEK 93.0
END DESCRIPTION:
XS GIS Cut Line= 3
      2786705.69      10206353.1      2786596.07      10206839.7
      2786405.69     10206953.11
#Sta/Elev= 30
  4501.2  1269.6  4511.5 1269.86  4520.3 1269.06  4552.5 1268.11  4568.7 1266.79
    4617 1265.42    4696  1261.5  4708.7 1261.65  4726.7 1260.46  4921.5 1254.07
  4930.1 1253.13    4942 1249.87  4952.2  1248.8  4975.1 1247.88  4975.6 1247.38
  4991.5 1247.38    4992 1247.88  4993.2 1248.61  5003.1 1248.13  5035.7 1249.46
    5060 1251.03  5075.6 1250.89  5091.2 1252.06  5118.4 1251.49  5128.2 1252.55
  5140.1 1256.12  5149.6 1257.62  5153.7 1259.07  5163.4 1260.35  5221.6 1262.82
#Mann= 5 ,-1 , 0
  4501.2     .05       0  4975.1     .05       0    4992     .05       0
  5035.7     .12       0  5153.7     .05       0
Bank Sta=4975.1,4992
XS Rating Curve= 0 ,0
Exp/Cntr=0.3,0.1

Type RM Length L Ch R = 1 ,46000   ,500,500,500
BEGIN DESCRIPTION:
SIXMILE CREEK 92.0
END DESCRIPTION:
XS GIS Cut Line= 3
      2786055.68     10206003.09      2786249.14     10206480.69
      2786205.68     10206753.15
#Sta/Elev= 30
  4484.7 1347.36  4517.1 1338.69    4529 1333.38    4571 1322.39  4577.2 1319.28
  4592.6 1316.29  4640.6 1301.75  4708.5 1280.34  4722.1 1278.71  4762.1 1267.59
  4768.3 1267.51    4776 1265.06  4808.4 1262.93  4821.9 1260.31  4839.8  1257.9
  4845.2 1258.61  4869.3 1254.31  4893.4 1253.39  4898.8 1254.53  4947.1 1248.26
  4952.4 1249.16  4990.2 1245.35  4990.7 1244.85  5007.1 1245.35  5022.7 1246.79
  5073.3 1246.33  5103.7 1249.86  5144.2 1251.34  5263.8 1259.95  5275.9 1260.49
#Mann= 7 ,-1 , 0
  4484.7     .12       0  4640.6     .05       0  4768.3     .12       0
  4821.9     .05       0  4990.2     .05       0  5007.1     .05       0
  5263.8     .12       0
Bank Sta=4990.2,5007.1
XS Rating Curve= 0 ,0
Exp/Cntr=0.3,0.1

Type RM Length L Ch R = 1 ,45500   ,500,500,500
BEGIN DESCRIPTION:
SIXMILE CREEK 91.0
END DESCRIPTION:
XS GIS Cut Line= 3
      2785755.68      10206303.1      2785790.31     10206488.09
      2786405.67      10206953.1
#Sta/Elev= 30
  4811.8 1312.89  4832.2 1309.65  4838.1 1306.01  4843.2 1305.37  4890.7 1282.49
  4903.4 1273.61  4923.7 1264.64  4943.3 1254.03  4954.2 1246.12  4964.4 1243.73
  4986.5 1240.81    4987 1240.31  5003.4 1240.81  5004.5  1241.4  5006.7 1242.57
  5014.8 1243.32  5050.2 1243.61    5107 1248.55    5121 1248.04  5150.1 1250.26
  5157.1 1249.78  5185.5 1252.18  5399.8 1258.83    5429 1260.71  5435.2 1260.14
    5458 1261.55  5480.8 1261.25  5586.4 1262.37  5707.8 1264.09  5771.3 1262.82
#Mann= 6 ,-1 , 0
  4811.8     .12       0  4986.5     .07       0  5003.4     .12       0
  5004.5     .05       0  5480.8     .12       0  5586.4     .05       0
Bank Sta=4986.5,5003.4
XS Rating Curve= 0 ,0
Exp/Cntr=0.3,0.1

Type RM Length L Ch R = 1 ,45000   ,500,500,500
BEGIN DESCRIPTION:
SIXMILE CREEK 90.0
END DESCRIPTION:
XS GIS Cut Line= 3
      2785394.62     10206883.37      2785841.19     10206920.34
      2786255.67     10206853.11
#Sta/Elev= 30
  4551.9 1279.96    4573  1281.6  4613.8 1282.87  4663.3 1286.96  4726.7 1290.39
  4783.8 1294.01  4813.9 1292.26  4833.9 1288.81    4844 1286.23  4850.4 1280.55
  4855.4 1281.06    4864 1274.89  4884.1 1264.45  4904.2 1255.85  4914.2 1249.35
  4924.2 1245.28  4932.8 1243.65  4945.1 1241.68    4976 1238.16  4976.5 1237.66
  4992.9 1238.16  5011.8 1239.59  5034.9 1239.97  5078.4 1245.37    5116 1248.22
  5227.4 1253.75  5288.2 1258.26  5308.5 1258.43  5359.1 1261.25  5419.9 1262.27
#Mann= 6 ,-1 , 0
  4551.9     .12       0  4726.7     .05       0  4932.8     .12       0
  4945.1     .05       0    4976     .05       0  4992.9     .05       0
Bank Sta=4976,4992.9
XS Rating Curve= 0 ,0
Exp/Cntr=0.3,0.1