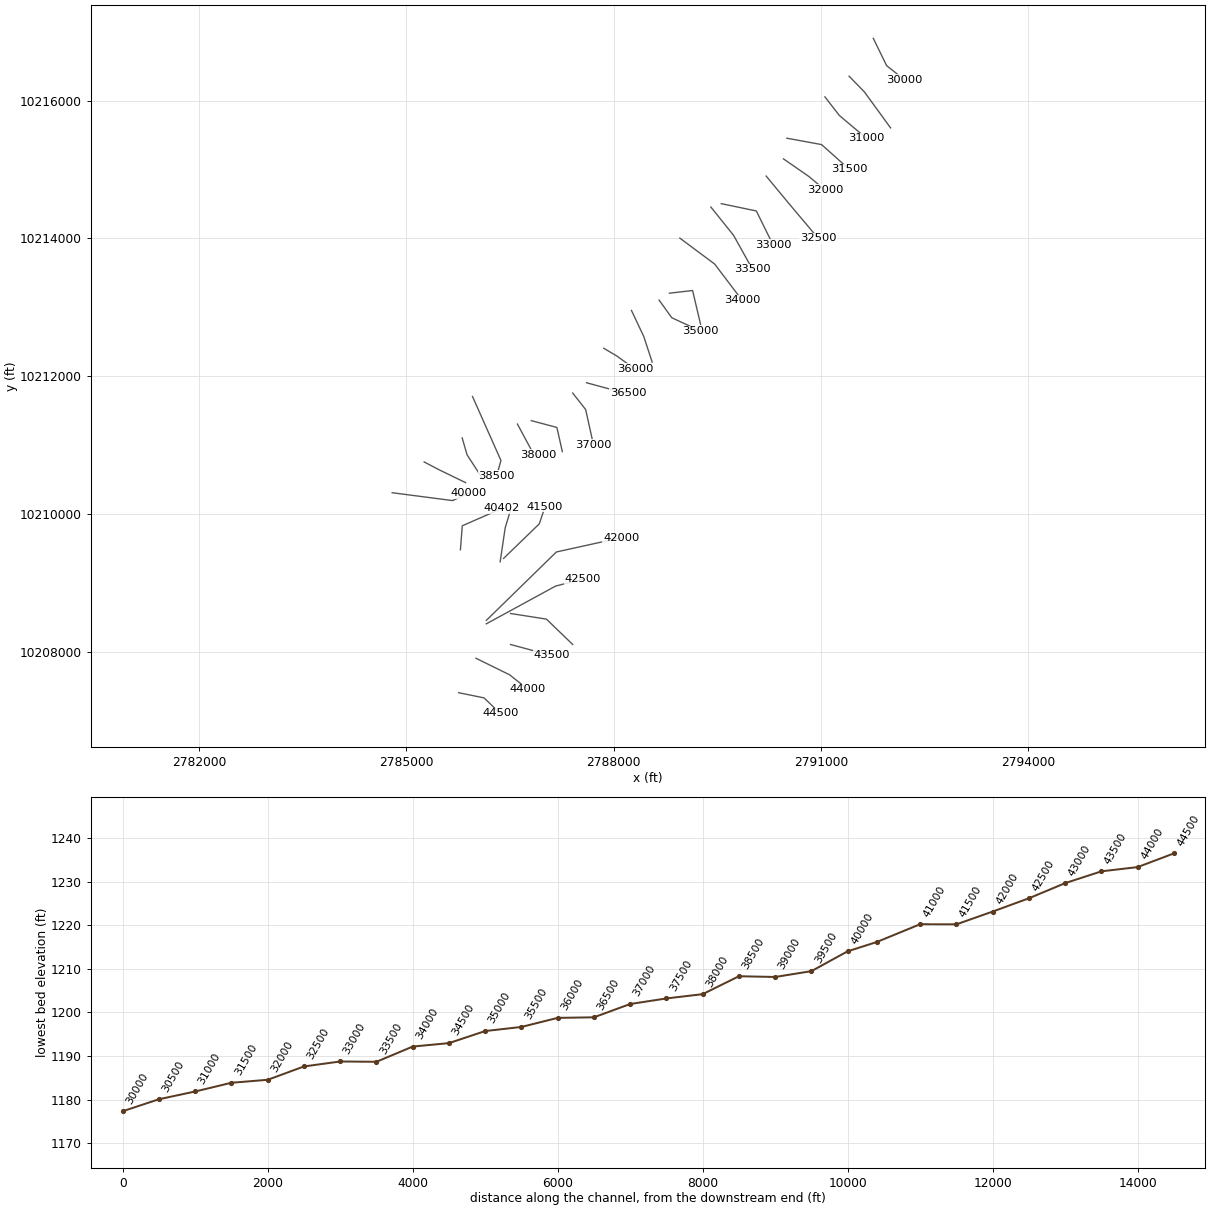
HEC-RAS study SIXMILE CREEK.prj: SIXMILE CREEK Base Level Engineering

--- SIXMILE CREEK.g01 (geometry) --- (continued)

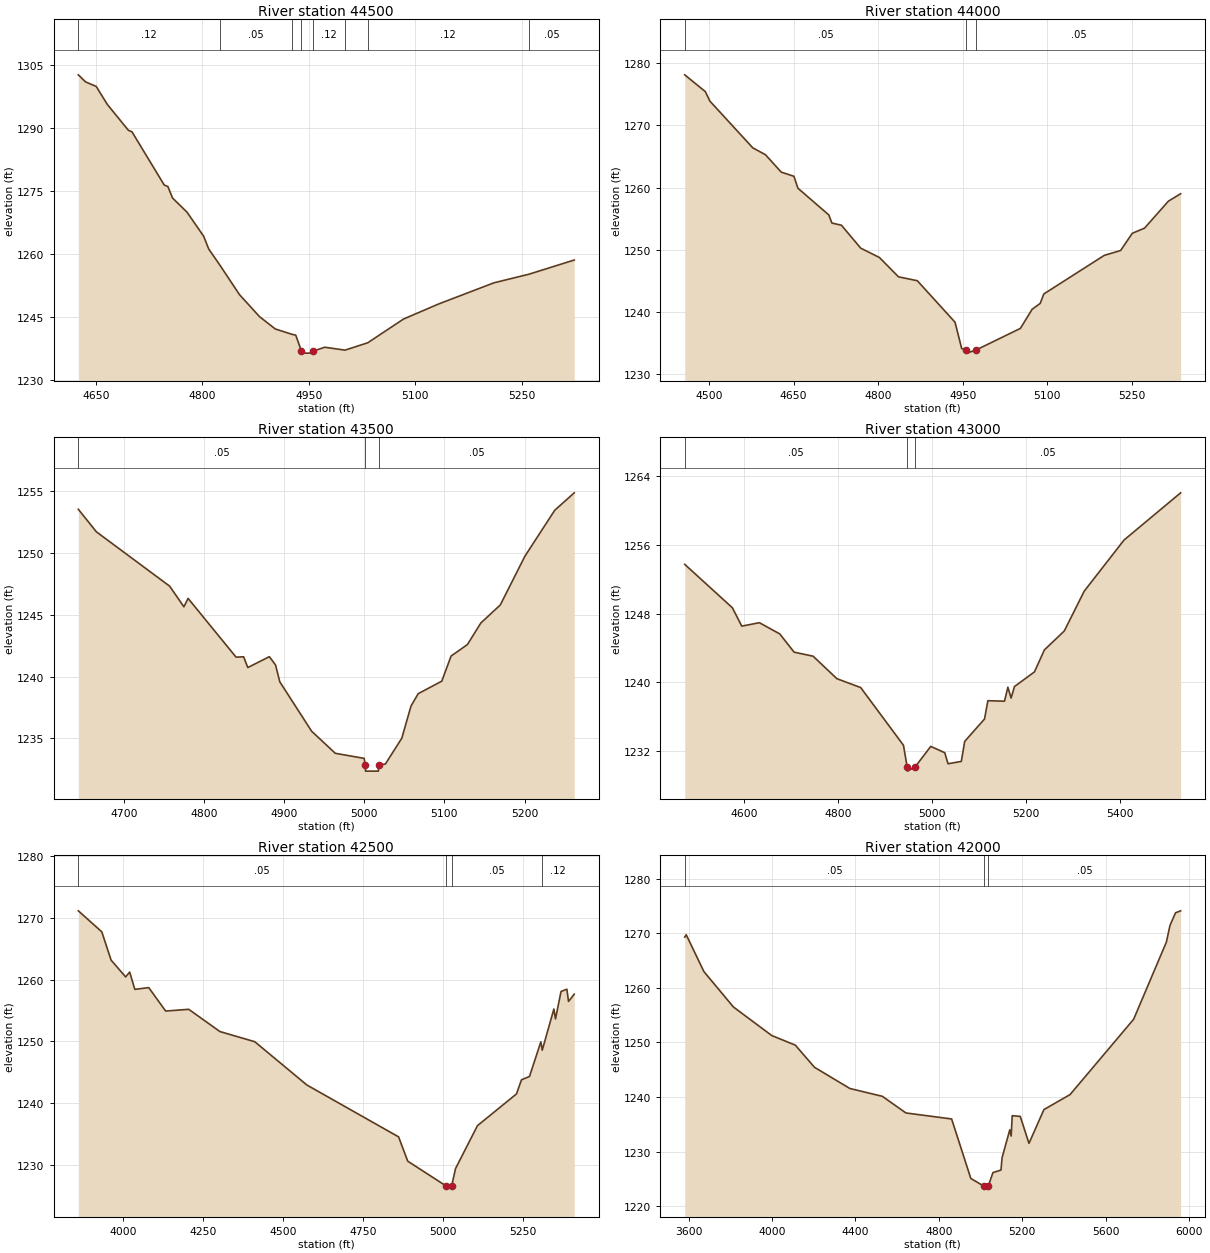
Type RM Length L Ch R = 1 ,44500   ,500,500,500
BEGIN DESCRIPTION:
SIXMILE CREEK 89.0
END DESCRIPTION:
XS GIS Cut Line= 3
      2785755.68     10207403.11      2786122.56     10207327.94
       2786355.7     10207103.09
#Sta/Elev= 30
  4625.5 1302.62  4635.7 1300.94  4650.7 1299.86  4666.3 1295.59    4696 1289.44
  4701.1 1289.06  4746.5 1276.42  4751.6 1276.07  4758.2 1273.34  4778.6 1269.97
    4802 1264.26  4809.2  1261.2  4824.9 1257.38  4852.4 1250.39  4880.7 1245.14
  4902.9 1242.21  4926.6 1240.93  4931.7 1240.75  4939.7 1236.97  4940.2 1236.47
  4956.2 1236.47  4956.7 1236.97  4972.6 1237.87  5001.1 1237.18  5033.1 1238.93
  5083.5 1244.57  5132.9 1248.15  5210.8 1253.18  5260.2 1255.23  5323.9  1258.6
#Mann= 8 ,-1 , 0
  4625.5     .12       0  4824.9     .05       0  4926.6     .12       0
  4939.7     .07       0  4956.7     .12       0  5001.1     .05       0
  5033.1     .12       0  5260.2     .05       0
Bank Sta=4939.7,4956.7
XS Rating Curve= 0 ,0
Exp/Cntr=0.3,0.1

Type RM Length L Ch R = 1 ,44000   ,500,500,500
BEGIN DESCRIPTION:
SIXMILE CREEK 88.0
END DESCRIPTION:
XS GIS Cut Line= 3
      2786005.69     10207903.11      2786492.91     10207662.94
      2786755.71     10207453.09
#Sta/Elev= 30
  4456.8 1278.15  4493.3 1275.45  4501.4 1273.92  4577.5 1266.39    4600 1265.28
    4628 1262.48  4650.5 1261.81  4657.5 1259.89  4712.3 1255.59  4717.8 1254.28
  4734.7 1253.93    4769 1250.23  4802.1 1248.73  4835.9 1245.62  4869.3 1244.99
  4936.2 1238.31    4948 1234.07  4956.4 1233.83  4956.9 1233.33  4973.4 1233.83
  5052.1 1237.31  5072.9 1240.39  5087.3 1241.34  5093.7 1242.86    5201 1249.08
  5229.8 1249.85  5250.6 1252.63  5272.3 1253.46  5314.7 1257.81  5336.3    1259
#Mann= 3 ,-1 , 0
  4456.8     .05       0  4956.4     .03       0  4973.4     .05       0
Bank Sta=4956.4,4973.4
XS Rating Curve= 0 ,0
Exp/Cntr=0.3,0.1

Type RM Length L Ch R = 1 ,43500   ,500,500,500
BEGIN DESCRIPTION:
SIXMILE CREEK 87.0
END DESCRIPTION:
XS GIS Cut Line= 3
       2786505.7     10208103.11      2786849.91     10208009.93
      2787105.67     10207953.11
#Sta/Elev= 30
  4643.4 1253.52  4665.9  1251.7  4757.3 1247.31  4775.1 1245.64  4780.3 1246.32
  4840.2 1241.57  4849.6  1241.6  4854.8 1240.73  4881.7 1241.61  4889.5 1240.93
  4894.7 1239.58  4934.5 1235.58    4964  1233.8    5000 1233.39  5001.2 1232.86
  5001.7 1232.36  5017.7 1232.36  5018.2 1232.86  5026.4 1232.93  5046.9 1235.02
  5058.4 1237.62  5067.4 1238.62  5096.8 1239.63  5108.4 1241.66  5128.8 1242.59
  5145.5 1244.33  5169.8 1245.79  5200.5 1249.73  5237.7 1253.44    5262 1254.85
#Mann= 3 ,-1 , 0
  4643.4     .05       0  5001.2     .03       0  5018.2     .05       0
Bank Sta=5001.2,5018.2
XS Rating Curve= 0 ,0
Exp/Cntr=0.3,0.1

Type RM Length L Ch R = 1 ,43000   ,500,500,500
BEGIN DESCRIPTION:
SIXMILE CREEK 86.0
END DESCRIPTION:
XS GIS Cut Line= 3
      2786505.73      10208553.1      2787025.55     10208471.41
      2787405.69      10208103.1
#Sta/Elev= 30
  4473.8 1253.72  4575.2 1248.67  4595.2 1246.53  4632.7 1246.93  4676.2 1245.62
  4706.6  1243.5  4747.1 1243.03  4797.7 1240.41  4848.3 1239.38  4939.4 1232.66
  4947.2 1230.15  4947.7 1229.65  4964.3 1230.15  4997.5 1232.53  5027.3 1231.79
  5034.2 1230.51  5062.5 1230.78  5069.7 1233.11  5111.9 1235.72  5119.1 1237.85
  5154.4 1237.79  5161.6 1239.42  5168.5 1238.16  5175.7  1239.5  5218.2  1241.2
  5239.3 1243.76  5281.7 1245.97  5324.2 1250.61    5409 1256.56  5529.3 1262.05
#Mann= 3 ,-1 , 0
  4473.8     .05       0  4947.2     .05       0  4964.3     .05       0
Bank Sta=4947.2,4964.3
XS Rating Curve= 0 ,0
Exp/Cntr=0.3,0.1

Type RM Length L Ch R = 1 ,42500   ,500,500,500
BEGIN DESCRIPTION:
SIXMILE CREEK 85.0
END DESCRIPTION:
XS GIS Cut Line= 3
       2786155.7     10208403.12      2787157.18      10208950.7
      2787555.73     10209053.12
#Sta/Elev= 30
  3858.6 1271.08  3932.1 1267.69  3961.2 1263.13  4006.7 1260.42  4019.4  1261.2
  4035.5 1258.41  4079.1 1258.69  4132.1 1254.91  4204.4 1255.19  4302.1  1251.6
  4411.2 1249.96  4574.3 1242.98  4861.5 1234.61  4890.2 1230.69  5010.6 1226.68
  5011.1 1226.18  5027.7 1226.68  5039.8 1229.49  5108.5 1236.42  5230.7 1241.54
  5246.3 1243.81  5271.5 1244.36    5307 1249.94  5311.4  1248.6  5347.8 1255.24
  5352.9 1253.64  5370.2 1258.07  5388.5 1258.43  5393.7 1256.46  5411.5 1257.63
#Mann= 4 ,-1 , 0
  3858.6     .05       0  5010.6     .03       0  5027.7     .05       0
  5311.4     .12       0
Bank Sta=5010.6,5027.7
XS Rating Curve= 0 ,0
Exp/Cntr=0.3,0.1

Type RM Length L Ch R = 1 ,42000   ,500,500,500
BEGIN DESCRIPTION:
SIXMILE CREEK 84.0
END DESCRIPTION:
XS GIS Cut Line= 3
      2786155.67      10208453.1      2787169.11     10209446.18
      2788105.72     10209653.12
#Sta/Elev= 30
  3581.1 1269.28  3588.2 1269.72  3673.1 1262.97  3814.5 1256.49  3998.4 1251.26
  4111.5  1249.5  4203.4 1245.44  4373.1 1241.56  4528.7 1240.13  4641.9 1237.08
    4861 1235.98  4953.1 1225.08    5018 1223.63  5018.5 1223.13  5036.4 1223.63
  5059.2 1226.16  5097.7 1226.62  5102.8 1228.86  5139.9 1233.99  5146.5 1232.85
  5151.6 1236.58  5190.2 1236.45    5232 1231.51  5303.7  1237.7  5428.9 1240.44
  5733.9 1254.24  5891.1 1268.39    5908  1271.4  5934.8 1273.74  5959.2  1274.1
#Mann= 3 ,-1 , 0
  3581.1     .05       0    5018     .03       0  5036.4     .05       0
Bank Sta=5018,5036.4
XS Rating Curve= 0 ,0
Exp/Cntr=0.3,0.1

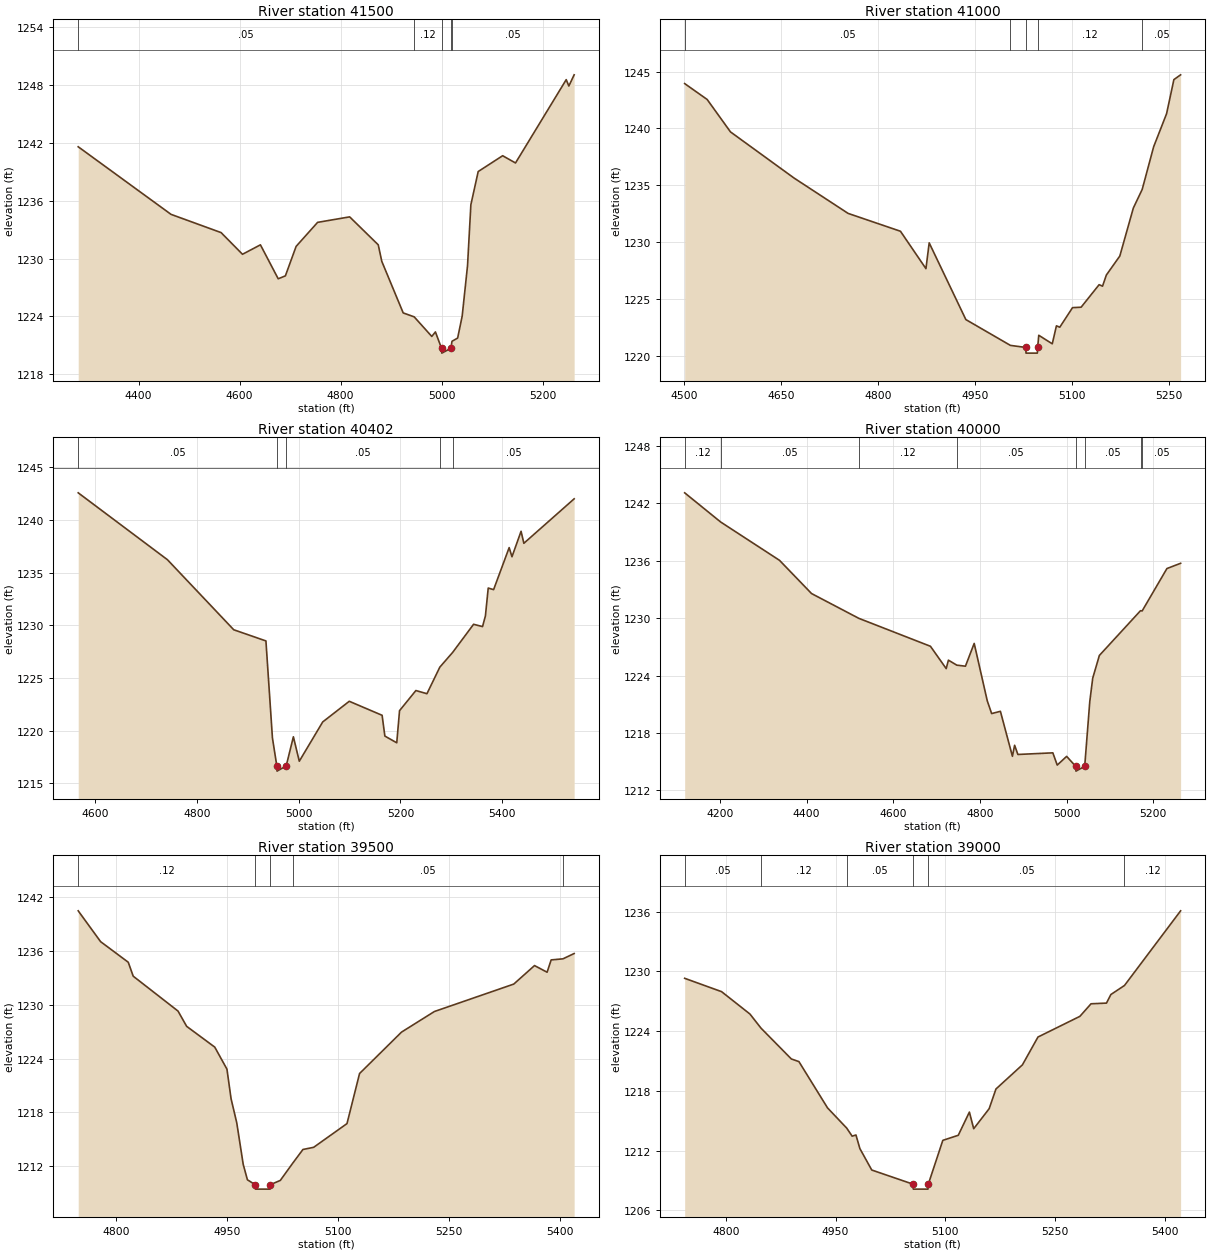
Type RM Length L Ch R = 1 ,41500   ,500,500,500
BEGIN DESCRIPTION:
SIXMILE CREEK 83.0
END DESCRIPTION:
XS GIS Cut Line= 3
      2786405.65     10209353.08      2786921.75     10209854.41
      2787005.69     10210103.12
#Sta/Elev= 30
  4280.5  1241.6  4464.3 1234.59  4563.4  1232.7  4605.8 1230.45  4641.3 1231.43
  4676.5 1227.91  4690.7 1228.21    4712 1231.27  4754.5 1233.76    4818 1234.33
  4874.6 1231.43  4881.6 1229.72    4924 1224.37  4945.8 1223.96  4980.6 1221.93
  4987.8  1222.4  4999.9  1220.7  5000.4  1220.2  5018.4  1220.7  5020.6 1221.43
  5031.8 1221.76  5040.8 1224.04  5051.4 1229.28    5058 1235.59  5072.5 1239.03
  5120.9 1240.67  5146.4 1239.92  5246.8 1248.56    5252  1247.9  5262.5 1249.06
#Mann= 5 ,-1 , 0
  4280.5     .05       0  4945.8     .12       0  4999.9     .07       0
  5018.4     .12       0  5020.6     .05       0
Bank Sta=4999.9,5018.4
XS Rating Curve= 0 ,0
Exp/Cntr=0.3,0.1

Type RM Length L Ch R = 1 ,41000   ,598,598,598
BEGIN DESCRIPTION:
SIXMILE CREEK 82.0
END DESCRIPTION:
XS GIS Cut Line= 3
      2786355.68     10209303.09      2786428.47     10209796.55
      2786505.68     10210053.08
#Sta/Elev= 30
  4501.2 1243.94    4536 1242.54    4572 1239.69  4670.3 1235.63  4753.9 1232.52
  4834.8 1230.95  4874.2 1227.66  4879.2 1229.93  4935.9 1223.18  5004.8 1220.91
  5028.4 1220.73  5028.9 1220.23  5046.4 1220.23  5046.9 1220.73  5048.6  1221.8
  5069.5 1221.05  5075.9 1222.63  5081.1 1222.51  5100.8 1224.23  5114.1 1224.27
  5141.9 1226.25  5147.2 1226.12  5153.1  1227.1  5173.9 1228.77  5194.8 1232.99
  5208.5 1234.63  5226.2 1238.38  5246.2 1241.29  5257.5 1244.29  5267.9 1244.71
#Mann= 5 ,-1 , 0
  4501.2     .05       0  5004.8     .12       0  5028.4     .03       0
  5046.9     .12       0  5208.5     .05       0
Bank Sta=5028.4,5046.9
XS Rating Curve= 0 ,0
Exp/Cntr=0.3,0.1

Type RM Length L Ch R = 1 ,40402   ,402,402,402
BEGIN DESCRIPTION:
SIXMILE CREEK 81.0
END DESCRIPTION:
XS GIS Cut Line= 3
      2785780.69     10209478.14      2785807.48     10209826.46
      2786380.72     10210078.13
#Sta/Elev= 30
  4566.3 1242.57  4741.8 1236.22  4872.2 1229.57  4935.5 1228.51  4948.3  1219.3
  4956.9 1216.65  4957.4 1216.15  4975.4 1216.65  4989.5 1219.41  5001.1 1217.09
  5047.2 1220.82  5099.4 1222.78    5164 1221.45  5169.4 1219.48  5192.8 1218.84
  5198.3 1221.89  5230.4  1223.8  5252.2  1223.5  5277.5 1226.02  5302.9 1227.43
  5343.9 1230.09  5361.5 1229.87  5367.2 1230.89  5372.7 1233.53  5383.3 1233.38
  5413.9 1237.37  5419.4  1236.5  5437.3 1238.92  5442.8 1237.78  5541.7    1242
#Mann= 5 ,-1 , 0
  4566.3     .05       0  4956.9     .03       0  4975.4     .05       0
  5277.5     .12       0  5302.9     .05       0
Bank Sta=4956.9,4975.4
XS Rating Curve= 0 ,0
Exp/Cntr=0.3,0.1

Type RM Length L Ch R = 1 ,40000   ,500,500,500
BEGIN DESCRIPTION:
SIXMILE CREEK 80.0
END DESCRIPTION:
XS GIS Cut Line= 3
      2784793.35     10210306.42      2785667.22     10210192.24
       2785905.7     10210303.12
#Sta/Elev= 30
  4118.7 1243.09  4201.8 1240.04  4337.5 1236.04  4411.4 1232.57  4520.5 1229.98
  4685.8 1227.06  4722.1 1224.73  4727.2 1225.61  4746.6 1225.09  4766.5 1224.98
  4786.7 1227.36  4816.9 1221.36    4827 1220.03  4847.2 1220.27  4874.9 1215.57
    4880 1216.72  4887.5 1215.76  4968.2 1215.93  4978.3 1214.65    5000 1215.56
    5021 1214.52  5021.5 1214.02  5041.7 1214.52  5053.4 1221.28  5060.2 1223.73
  5075.5  1226.1  5170.5 1230.78  5174.2 1230.75  5231.4 1235.18    5263 1235.73
#Mann= 8 ,-1 , 0
  4118.7     .12       0  4201.8     .05       0  4520.5     .12       0
  4746.6     .05       0    5021     .05       0  5041.7     .05       0
  5170.5     .12       0  5174.2     .05       0
Bank Sta=5021,5041.7
XS Rating Curve= 0 ,0
Exp/Cntr=0.3,0.1

Type RM Length L Ch R = 1 ,39500   ,500,500,500
BEGIN DESCRIPTION:
SIXMILE CREEK 79.0
END DESCRIPTION:
XS GIS Cut Line= 3
      2785255.69     10210753.11      2785478.41     10210636.49
       2785855.7      10210453.1
#Sta/Elev= 30
  4748.6 1240.43  4778.9    1237  4816.3 1234.71    4823 1233.16  4883.6 1229.28
  4895.3 1227.58  4933.3 1225.27  4949.8 1222.82  4955.4 1219.52  4963.1 1216.84
  4971.8 1212.23  4977.5 1210.51  4987.9 1209.97  4988.4 1209.47  5008.2 1209.47
  5008.7 1209.97    5022 1210.44  5039.1 1212.39  5052.6 1213.88  5067.1 1214.12
  5112.2 1216.76  5129.2 1222.33    5186 1226.94  5230.5 1229.23  5337.8 1232.28
  5365.9 1234.34  5382.9  1233.6  5388.4 1234.97  5404.4 1235.09  5419.5 1235.68
#Mann= 5 ,-1 , 0
  4748.6     .12       0  4987.9     .07       0  5008.7     .12       0
  5039.1     .05       0  5404.4     .12       0
Bank Sta=4987.9,5008.7
XS Rating Curve= 0 ,0
Exp/Cntr=0.3,0.1

Type RM Length L Ch R = 1 ,39000   ,500,500,500
BEGIN DESCRIPTION:
SIXMILE CREEK 78.0
END DESCRIPTION:
XS GIS Cut Line= 3
      2785805.69     10211103.08      2785876.88     10210856.97
      2786105.69      10210503.1
#Sta/Elev= 30
  4743.8 1229.31  4794.2 1227.97    4833 1225.72    4848 1224.31  4889.5 1221.21
  4899.9 1220.94    4939 1216.29  4965.2 1214.26  4972.6 1213.45  4977.8 1213.57
  4983.2  1212.2  4999.4 1210.05  5055.7 1208.63  5056.2 1208.13  5076.2 1208.13
  5076.7 1208.63  5096.5 1213.03  5117.6 1213.54  5132.8 1215.87  5138.7  1214.2
  5159.8 1216.21  5169.1 1218.19  5205.3 1220.62  5226.5 1223.41  5283.8 1225.49
    5299 1226.75  5320.1 1226.82  5326.1 1227.68  5344.7 1228.59  5421.4 1236.09
#Mann= 6 ,-1 , 0
  4743.8     .05       0    4848     .12       0  4965.2     .05       0
  5055.7     .05       0  5076.7     .05       0  5344.7     .12       0
Bank Sta=5055.7,5076.7
XS Rating Curve= 0 ,0
Exp/Cntr=0.3,0.1

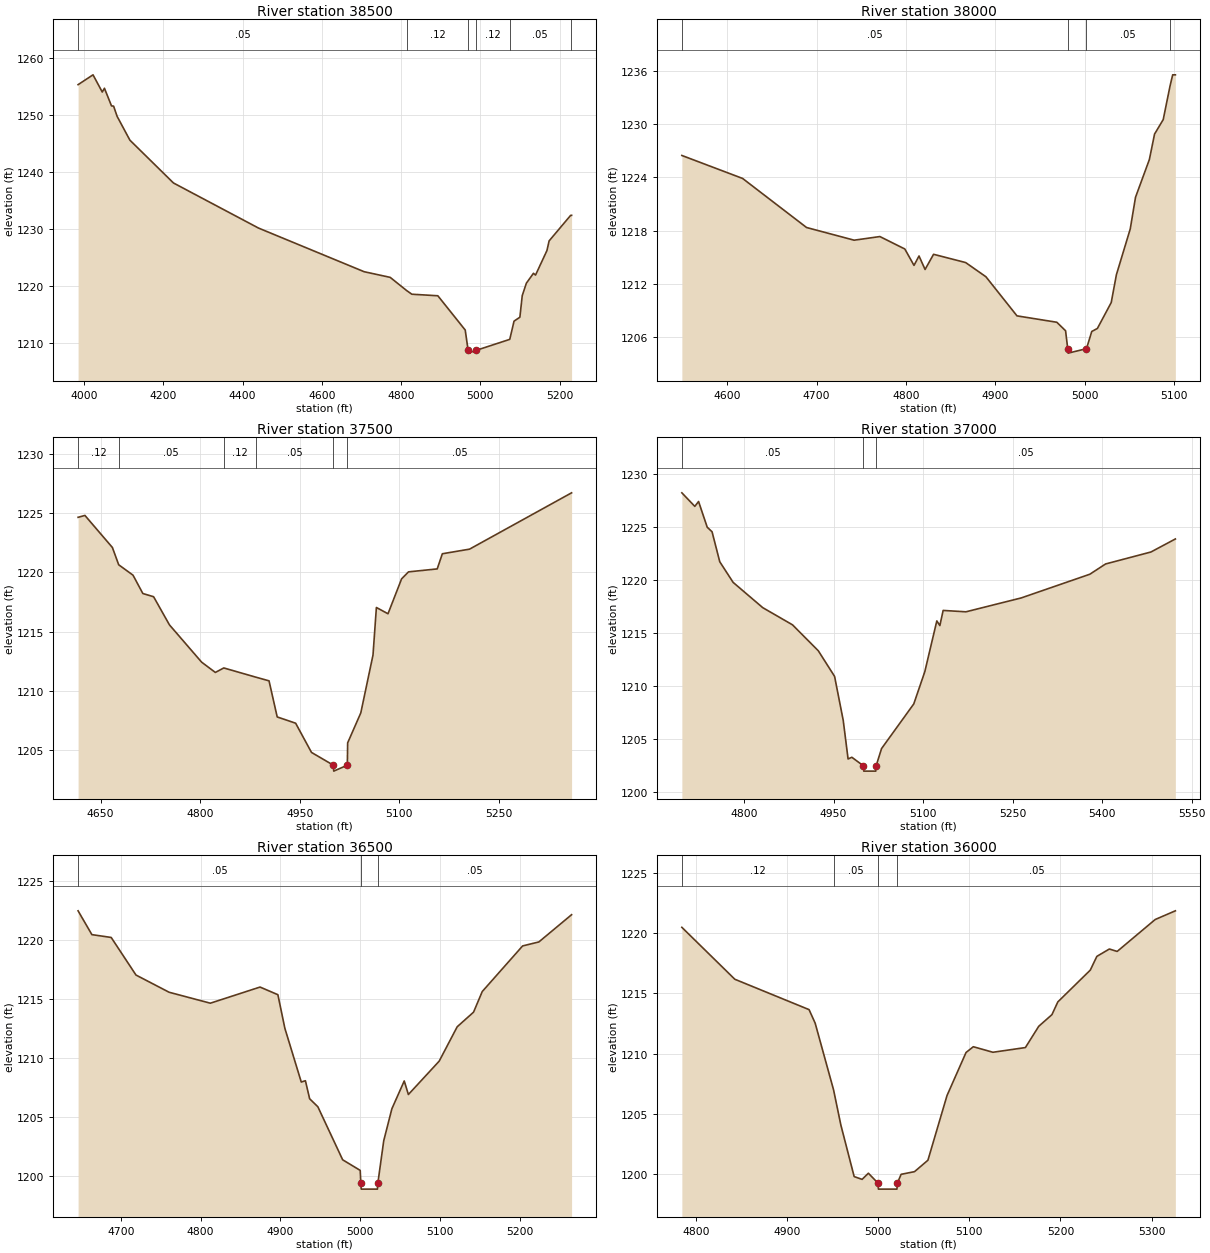
Type RM Length L Ch R = 1 ,38500   ,500,500,500
BEGIN DESCRIPTION:
SIXMILE CREEK 77.0
END DESCRIPTION:
XS GIS Cut Line= 3
      2785955.66     10211703.16      2786366.97      10210774.9
      2786305.68     10210553.11
#Sta/Elev= 30
  3984.7 1255.29  4022.4 1257.01  4045.7    1254  4051.2 1254.66    4069 1251.58
  4074.4 1251.52  4083.2 1249.74  4115.5 1245.57  4225.4 1238.08    4440 1230.19
  4706.6 1222.55  4772.3 1221.56  4813.9 1219.25    4827 1218.61  4892.6 1218.34
  4961.7 1212.34    4969  1208.8  4969.5  1208.3    4990  1208.8  5074.1 1210.71
  5084.9  1213.9  5099.6 1214.58  5105.6 1218.37    5116 1220.54  5133.9 1222.27
  5139.1 1221.96  5167.9 1226.25  5173.4 1227.94  5227.8 1232.42  5230.1 1232.42
#Mann= 6 ,-1 , 0
  3984.7     .05       0  4813.9     .12       0    4969     .07       0
    4990     .12       0  5074.1     .05       0  5227.8     .12       0
Bank Sta=4969,4990
XS Rating Curve= 0 ,0
Exp/Cntr=0.3,0.1

Type RM Length L Ch R = 1 ,38000   ,500,500,500
BEGIN DESCRIPTION:
SIXMILE CREEK 76.0
END DESCRIPTION:
XS GIS Cut Line= 3
      2786605.71     10211303.07      2786818.82     10210905.71
      2786905.72     10210853.09
#Sta/Elev= 30
  4549.1 1226.47  4617.1 1223.88  4688.7 1218.35    4742 1216.92  4770.8 1217.33
  4798.7 1215.93    4809 1214.08  4814.6 1215.14  4821.4 1213.62  4830.9 1215.33
  4866.8  1214.4  4889.5  1212.8  4924.3 1208.39  4968.9 1207.67  4978.7 1206.71
  4981.1 1204.69  4981.6 1204.19  5002.1 1204.69    5008 1206.63  5014.3 1206.97
  5029.8 1209.89  5035.6 1213.03  5051.1 1218.19    5057 1221.76  5072.5 1226.01
  5078.3 1228.88    5088 1230.51  5095.6 1234.28  5098.6 1235.56  5101.6 1235.56
#Mann= 4 ,-1 , 0
  4549.1     .05       0  4981.1     .05       0  5002.1     .05       0
  5095.6     .12       0
Bank Sta=4981.1,5002.1
XS Rating Curve= 0 ,0
Exp/Cntr=0.3,0.1

Type RM Length L Ch R = 1 ,37500   ,500,500,500
BEGIN DESCRIPTION:
SIXMILE CREEK 75.0
END DESCRIPTION:
XS GIS Cut Line= 3
      2786805.73      10211353.1      2787176.76     10211254.14
      2787255.69      10210903.1
#Sta/Elev= 30
    4616 1224.66  4626.3 1224.82  4667.7 1222.11  4677.2 1220.65  4698.8 1219.77
  4713.6 1218.22  4729.8 1217.95  4753.7 1215.57  4802.2 1212.42  4822.9 1211.55
  4835.6 1211.93    4884 1211.15  4903.8 1210.84  4916.1 1207.79  4943.9 1207.26
  4967.8 1204.79  5000.8 1203.71  5001.3 1203.21  5021.8 1203.71  5022.3  1205.6
  5042.1 1208.13  5060.5 1213.02  5065.6 1217.04  5083.1 1216.51  5103.6 1219.46
    5114 1220.05  5157.3  1220.3    5165 1221.58    5206 1221.97  5359.8 1226.73
#Mann= 6 ,-1 , 0
    4616     .12       0  4677.2     .05       0  4835.6     .12       0
    4884     .05       0  5000.8     .03       0  5021.8     .05       0
Bank Sta=5000.8,5021.8
XS Rating Curve= 0 ,0
Exp/Cntr=0.3,0.1

Type RM Length L Ch R = 1 ,37000   ,500,500,500
BEGIN DESCRIPTION:
SIXMILE CREEK 74.0
END DESCRIPTION:
XS GIS Cut Line= 3
      2787405.68     10211753.12       2787593.2     10211513.59
      2787705.68     10211003.14
#Sta/Elev= 30
  4695.8 1228.22  4717.5 1226.94  4723.8  1227.4  4738.3 1224.97  4746.4 1224.54
  4759.3 1221.71  4781.7 1219.76  4831.4 1217.37  4881.2 1215.75  4924.4  1213.3
  4951.7 1210.88  4966.2 1206.72  4974.3 1203.08  4980.6 1203.24  5000.1 1202.43
  5000.6 1201.93  5020.8 1201.93  5021.3 1202.43  5030.4 1204.06  5084.4 1208.28
  5102.9 1211.33    5123 1216.12  5128.1 1215.68  5133.6 1217.11  5171.8 1216.98
  5264.4 1218.29  5379.4 1220.53  5405.8  1221.5  5481.8 1222.63  5522.7 1223.86
#Mann= 3 ,-1 , 0
  4695.8     .05       0  5000.1     .03       0  5021.3     .05       0
Bank Sta=5000.1,5021.3
XS Rating Curve= 0 ,0
Exp/Cntr=0.3,0.1

Type RM Length L Ch R = 1 ,36500   ,500,500,500
BEGIN DESCRIPTION:
SIXMILE CREEK 73.0
END DESCRIPTION:
XS GIS Cut Line= 3
      2787605.65     10211903.12      2787946.88       10211810.
       2788205.7     10211753.11
#Sta/Elev= 30
  4646.3  1222.5  4663.6 1220.48  4687.8 1220.24  4718.9 1217.05  4760.4 1215.59
  4812.1 1214.66  4874.4 1216.03  4896.8 1215.38  4905.5 1212.54  4926.1 1207.97
  4931.3 1208.08  4936.6 1206.55  4946.9 1205.87    4978 1201.37    5000 1200.47
  5000.8 1199.38  5001.3 1198.88  5021.6 1198.88  5022.1 1199.38  5029.5 1202.99
  5039.7  1205.7  5055.2 1208.06  5060.4 1206.91    5099 1209.74  5121.6 1212.66
  5142.1  1213.9    5153 1215.65  5203.6 1219.52    5224 1219.86    5265 1222.17
#Mann= 3 ,-1 , 0
  4646.3     .05       0  5000.8     .03       0  5022.1     .05       0
Bank Sta=5000.8,5022.1
XS Rating Curve= 0 ,0
Exp/Cntr=0.3,0.1

Type RM Length L Ch R = 1 ,36000   ,500,500,500
BEGIN DESCRIPTION:
SIXMILE CREEK 72.0
END DESCRIPTION:
XS GIS Cut Line= 3
      2787855.69     10212403.11      2788040.84     10212293.23
      2788305.67     10212103.12
#Sta/Elev= 30
  4784.7 1220.48  4842.8 1216.17  4924.2 1213.65  4930.9 1212.53  4951.1 1206.99
  4959.1 1204.07  4973.7 1199.79  4982.4 1199.56  4989.3 1200.07  4999.8 1199.25
  5000.3 1198.75  5020.6 1198.75  5021.1 1199.25  5025.2 1199.98  5039.9  1200.2
  5054.6 1201.15  5075.5 1206.51  5096.4 1210.09  5104.4 1210.57  5125.9 1210.11
  5161.5  1210.5  5176.2 1212.27  5190.6 1213.23  5197.1 1214.29  5232.7 1216.93
  5239.9 1218.07  5253.6 1218.68  5262.2 1218.48  5303.9 1221.13    5326 1221.85
#Mann= 4 ,-1 , 0
  4784.7     .12       0  4951.1     .05       0  4999.8     .03       0
  5021.1     .05       0
Bank Sta=4999.8,5021.1
XS Rating Curve= 0 ,0
Exp/Cntr=0.3,0.1

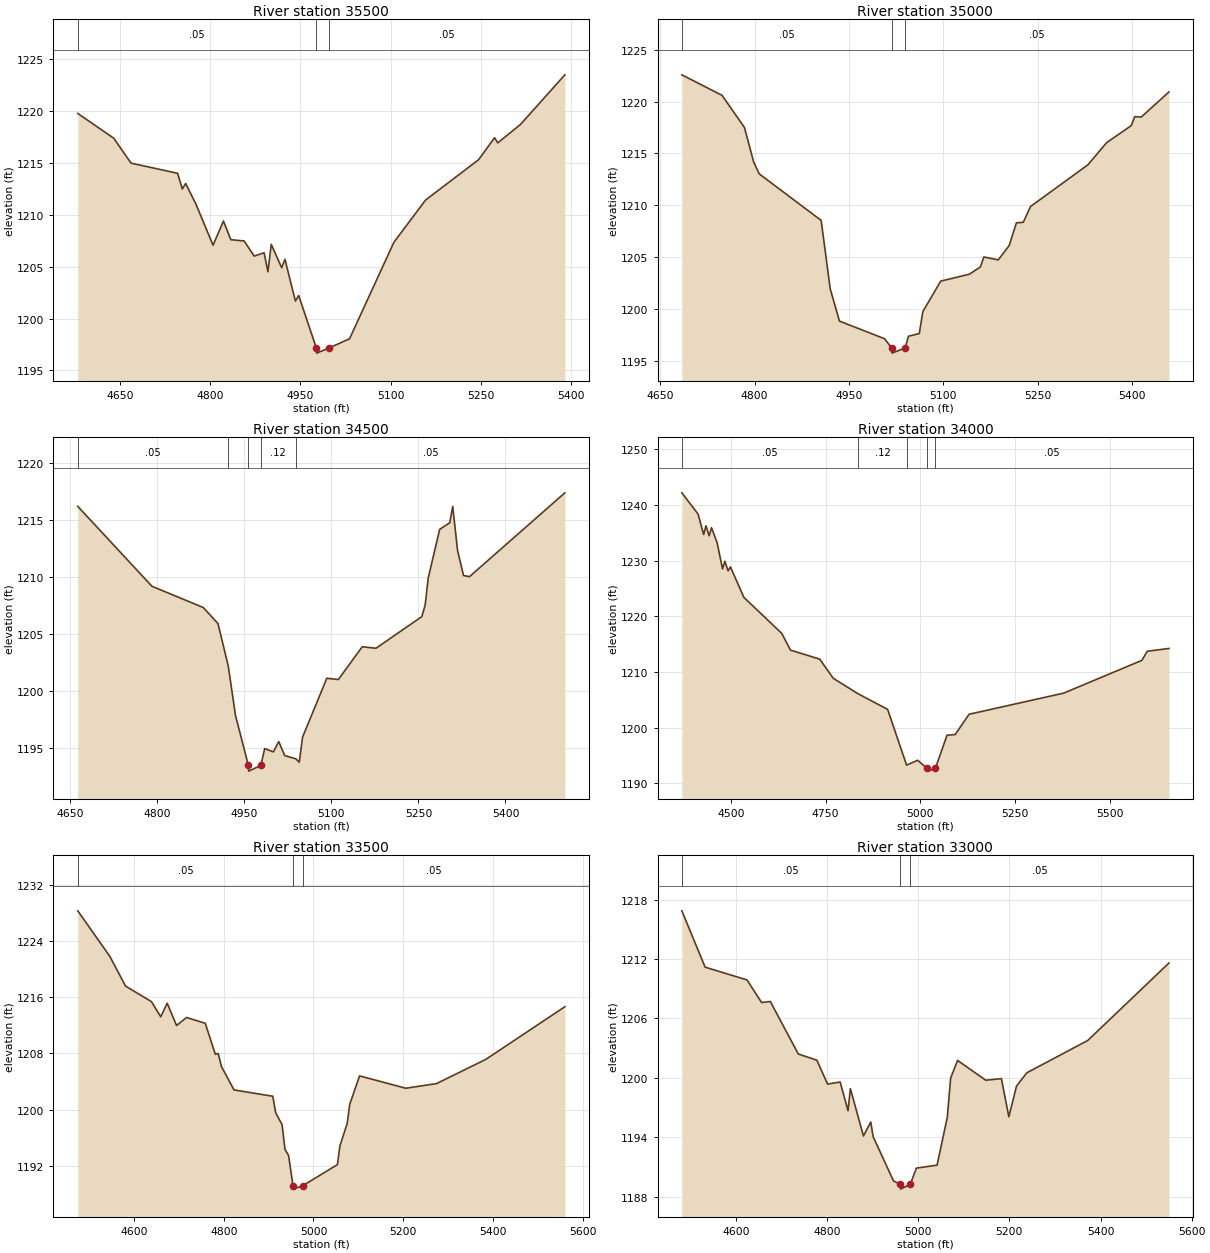
Type RM Length L Ch R = 1 ,35500   ,500,500,500
BEGIN DESCRIPTION:
SIXMILE CREEK 71.0
END DESCRIPTION:
XS GIS Cut Line= 3
      2788255.66     10212953.16      2788434.58     10212573.28
      2788555.69     10212203.09
#Sta/Elev= 30
  4580.1 1219.77  4639.9 1217.38  4668.6 1214.98    4746    1214  4753.8 1212.49
  4759.4 1213.02  4776.6 1211.01  4804.9 1207.07  4822.2  1209.4  4834.4  1207.6
  4856.5 1207.48  4873.3 1206.02  4889.7 1206.34  4896.1 1204.51  4901.6 1207.16
  4918.9  1204.9  4924.4 1205.71  4941.7 1201.69  4947.2 1202.22  4976.5 1197.17
    4977 1196.67  4997.9 1197.17  5031.7 1198.05  5105.4 1207.35    5158 1211.42
  5246.1 1215.31  5272.7 1217.43    5278 1216.93  5315.8 1218.71  5389.5 1223.49
#Mann= 3 ,-1 , 0
  4580.1     .05       0  4976.5     .05       0  4997.9     .05       0
Bank Sta=4976.5,4997.9
XS Rating Curve= 0 ,0
Exp/Cntr=0.3,0.1

Type RM Length L Ch R = 1 ,35000   ,500,500,500
BEGIN DESCRIPTION:
SIXMILE CREEK 70.0
END DESCRIPTION:
XS GIS Cut Line= 3
      2788655.66     10213103.15      2788839.48     10212846.74
      2789255.65     10212653.13
#Sta/Elev= 30
  4684.5 1222.59  4748.4 1220.61    4784 1217.51  4798.8 1214.15  4807.4 1213.04
    4906 1208.54  4920.4 1201.93  4935.1 1198.82  5006.8 1197.12  5018.1 1196.23
  5018.6 1195.73  5039.6 1196.23  5044.8 1197.36    5062 1197.62  5067.7 1199.74
  5096.1 1202.68  5141.8 1203.35  5159.2 1204.05  5164.7 1205.01  5187.6 1204.73
    5205 1206.12  5216.4  1208.3  5227.4 1208.36  5238.9 1209.88  5330.4 1213.92
  5359.8 1216.04  5399.1 1217.69  5404.6 1218.56  5414.9 1218.51    5459 1220.94
#Mann= 3 ,-1 , 0
  4684.5     .05       0  5018.1     .03       0  5039.6     .05       0
Bank Sta=5018.1,5039.6
XS Rating Curve= 0 ,0
Exp/Cntr=0.3,0.1

Type RM Length L Ch R = 1 ,34500   ,500,500,500
BEGIN DESCRIPTION:
SIXMILE CREEK 69.0
END DESCRIPTION:
XS GIS Cut Line= 3
      2788805.65     10213203.11      2789140.59     10213242.11
      2789255.69     10212753.08
#Sta/Elev= 30
  4662.8 1216.23  4790.6 1209.21  4879.1 1207.34  4904.5 1205.93  4922.2 1202.19
  4934.7 1197.84  4956.9 1193.46  4957.4 1192.96  4978.4 1193.46    4985 1194.94
    5000 1194.65  5009.2 1195.56  5019.5 1194.33  5038.7 1194.04  5044.6 1193.75
  5050.3 1195.95  5092.1 1201.12    5112 1201.01  5153.1 1203.89  5176.9 1203.76
  5255.8 1206.54  5261.6 1207.56  5266.8 1209.92  5286.6 1214.21    5304 1214.79
  5309.1 1216.23  5317.4 1212.37  5327.7 1210.15    5338 1210.05  5502.4 1217.42
#Mann= 5 ,-1 , 0
  4662.8     .05       0  4922.2     .12       0  4956.9     .07       0
  4978.4     .12       0  5038.7     .05       0
Bank Sta=4956.9,4978.4
XS Rating Curve= 0 ,0
Exp/Cntr=0.3,0.1

Type RM Length L Ch R = 1 ,34000   ,500,500,500
BEGIN DESCRIPTION:
SIXMILE CREEK 68.0
END DESCRIPTION:
XS GIS Cut Line= 3
      2788955.65     10214003.14      2789459.77     10213626.47
      2789855.66     10213103.14
#Sta/Elev= 30
  4370.7 1242.19  4413.5 1238.37  4428.1  1234.7  4434.3 1236.27  4442.7 1234.47
  4448.9 1235.92  4463.5 1233.29  4478.1 1228.51  4484.3 1229.89  4492.7 1228.18
  4498.9 1228.87  4534.4  1223.4  4634.4 1216.92  4657.4 1213.92  4734.5  1212.3
  4770.2 1208.86  4836.4 1206.05  4913.7 1203.27  4963.8 1193.25    4993 1194.12
  5017.9 1192.67  5018.4 1192.17  5039.8 1192.67  5070.5 1198.62    5092 1198.74
  5128.7 1202.39  5378.4 1206.19  5584.5 1212.07    5599 1213.71  5656.2 1214.22
#Mann= 5 ,-1 , 0
  4370.7     .05       0  4836.4     .12       0  4963.8     .05       0
  5017.9     .03       0  5039.8     .05       0
Bank Sta=5017.9,5039.8
XS Rating Curve= 0 ,0
Exp/Cntr=0.3,0.1

Type RM Length L Ch R = 1 ,33500   ,500,500,500
BEGIN DESCRIPTION:
SIXMILE CREEK 67.0
END DESCRIPTION:
XS GIS Cut Line= 3
      2789405.69     10214453.11      2789733.73     10214042.96
      2790005.69     10213553.09
#Sta/Elev= 30
  4474.8 1228.32    4546 1221.86  4581.3  1217.6  4638.9 1215.39  4659.7 1213.23
  4674.1 1215.16  4694.9 1211.99  4717.3 1213.13  4758.9  1212.3  4781.4 1207.88
  4787.8    1208  4794.9 1206.15    4823 1202.81  4909.4 1201.91  4915.8 1199.57
  4930.2 1197.85  4936.6 1194.32  4944.6 1193.48  4954.4 1189.18  4954.9 1188.68
  4976.4 1189.18  5053.4 1192.17  5059.1 1194.86  5075.2 1198.03  5080.9 1200.76
  5102.8 1204.81  5205.7 1203.05  5274.3 1203.71  5384.1 1207.16  5560.3 1214.66
#Mann= 3 ,-1 , 0
  4474.8     .05       0  4954.4     .05       0  4976.4     .05       0
Bank Sta=4954.4,4976.4
XS Rating Curve= 0 ,0
Exp/Cntr=0.3,0.1

Type RM Length L Ch R = 1 ,33000   ,500,500,500
BEGIN DESCRIPTION:
SIXMILE CREEK 66.0
END DESCRIPTION:
XS GIS Cut Line= 3
      2789555.72      10214503.1      2790063.25       10214397.
      2790305.69      10213903.1
#Sta/Elev= 30
  4481.5 1216.86  4532.5 1211.17  4624.5 1209.88  4656.4  1207.6  4675.6  1207.7
  4736.9  1202.4  4777.7 1201.77  4801.2 1199.36  4828.8 1199.57  4846.1 1196.67
  4851.2  1198.9  4879.9 1194.12    4896 1195.53  4901.1 1194.05    4946 1189.57
  4960.8 1189.25  4961.3 1188.75  4982.8 1189.25    4996 1190.87  5041.4 1191.17
  5063.9 1196.01  5071.2 1199.97  5086.4 1201.75  5148.3 1199.75  5182.6 1199.91
  5198.9 1196.06  5215.8 1199.16  5238.3  1200.5  5371.9 1203.76  5550.2 1211.59
#Mann= 3 ,-1 , 0
  4481.5     .05       0  4960.8     .05       0  4982.8     .05       0
Bank Sta=4960.8,4982.8
XS Rating Curve= 0 ,0
Exp/Cntr=0.3,0.1

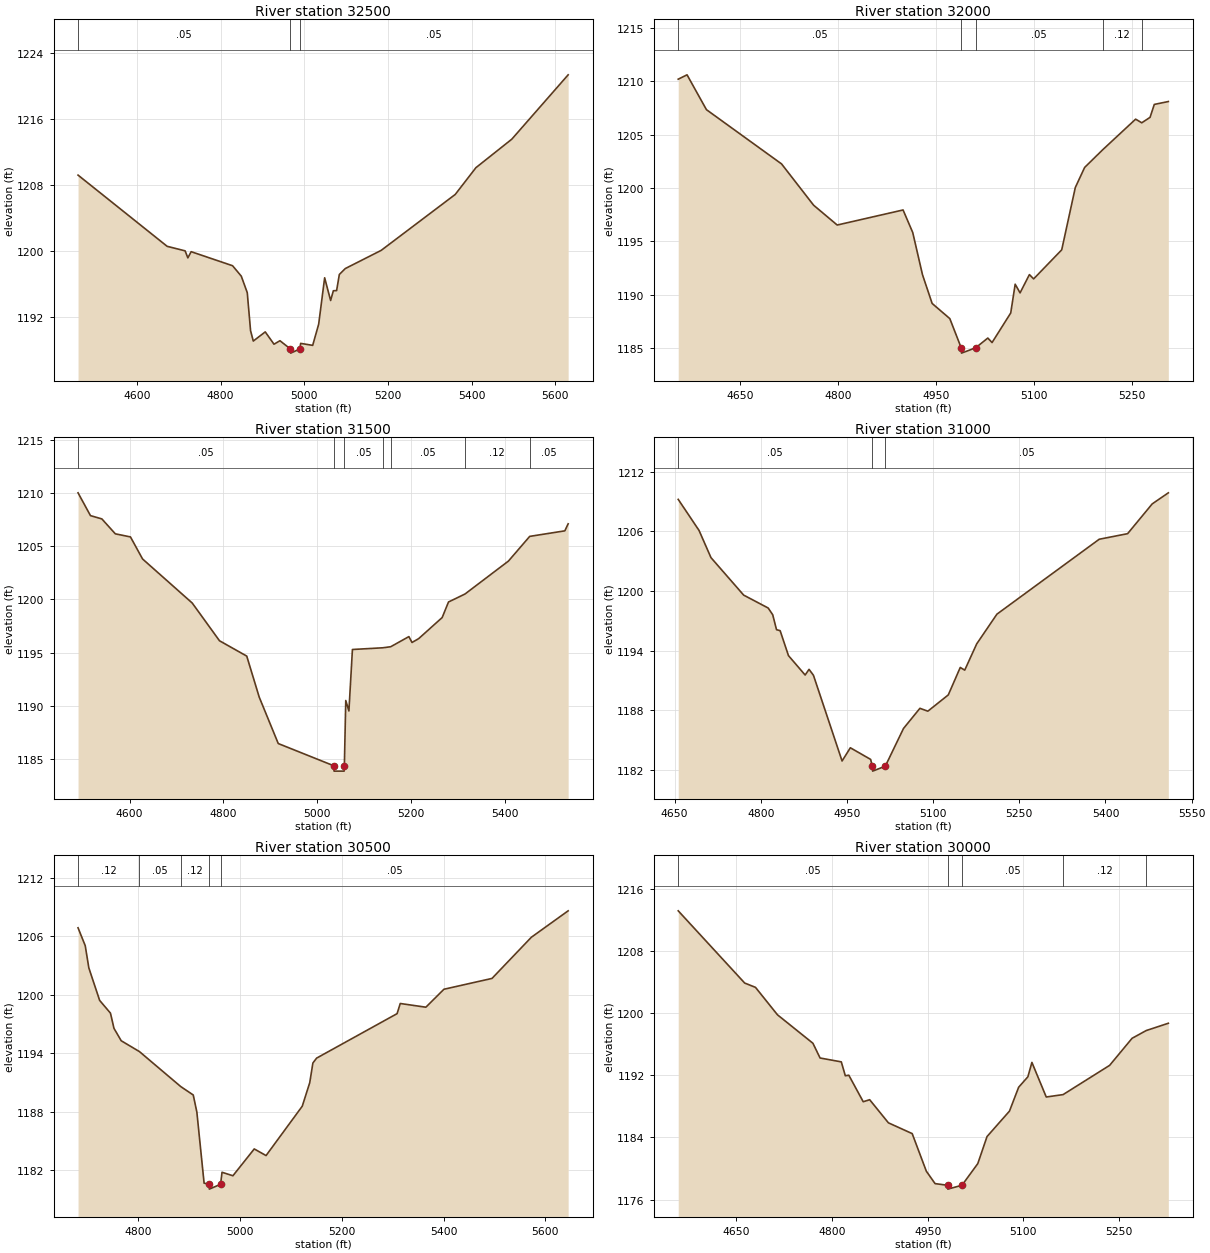
Type RM Length L Ch R = 1 ,32500   ,500,500,500
BEGIN DESCRIPTION:
SIXMILE CREEK 65.0
END DESCRIPTION:
XS GIS Cut Line= 3
      2790205.65     10214903.15      2790550.02      10214486.3
      2790955.69     10214003.11
#Sta/Elev= 30
  4459.3 1209.16  4672.3 1200.54  4715.3 1199.99  4721.8 1199.14  4729.7 1199.89
  4828.7 1198.19  4849.5 1196.93  4863.8 1194.93  4871.7 1190.33  4878.2 1189.07
  4906.8 1190.18  4927.7 1188.69    4942 1189.11  4967.1 1188.11  4967.6 1187.61
  4989.3 1188.11  4991.5 1188.79  5020.2 1188.55  5034.5 1191.11  5048.8 1196.73
  5063.1 1193.98  5069.6 1195.16  5077.4 1195.18  5083.9 1197.13  5098.2 1197.85
    5184 1200.05    5361 1206.82  5410.4 1210.06  5496.2 1213.51  5630.9  1221.3
#Mann= 3 ,-1 , 0
  4459.3     .05       0  4967.1     .03       0  4989.3     .05       0
Bank Sta=4967.1,4989.3
XS Rating Curve= 0 ,0
Exp/Cntr=0.3,0.1

Type RM Length L Ch R = 1 ,32000   ,500,500,500
BEGIN DESCRIPTION:
SIXMILE CREEK 64.0
END DESCRIPTION:
XS GIS Cut Line= 3
      2790455.71      10215153.1      2790820.87     10214899.47
      2791055.69     10214703.11
#Sta/Elev= 30
  4555.4 1210.19  4568.9  1210.6  4598.6 1207.34  4713.7 1202.26  4762.7  1198.4
  4798.9 1196.54  4899.8 1197.95  4914.6 1195.84  4929.5  1191.9  4944.3  1189.2
  4971.4 1187.78  4988.8 1185.05  4989.3 1184.55    5011 1185.05  5029.6 1185.96
  5036.1 1185.54  5064.7 1188.31  5071.5    1191    5079 1190.19  5093.3  1191.9
  5099.8  1191.5  5142.8 1194.22  5163.6 1200.05  5177.9 1201.93  5205.8  1203.6
    5256 1206.45  5265.4 1206.11  5278.1 1206.62  5284.6 1207.83  5306.1  1208.1
#Mann= 5 ,-1 , 0
  4555.4     .05       0  4988.8     .03       0    5011     .05       0
  5205.8     .12       0  5265.4     .05       0
Bank Sta=4988.8,5011
XS Rating Curve= 0 ,0
Exp/Cntr=0.3,0.1

Type RM Length L Ch R = 1 ,31500   ,500,500,500
BEGIN DESCRIPTION:
SIXMILE CREEK 63.0
END DESCRIPTION:
XS GIS Cut Line= 3
      2790505.71     10215453.11      2791007.07     10215360.73
      2791405.67     10215003.13
#Sta/Elev= 30
  4490.2    1210  4516.7 1207.86    4541 1207.55  4569.7 1206.15    4602 1205.86
  4627.8 1203.79  4733.8 1199.65  4791.9 1196.11    4850 1194.67  4876.6 1190.82
  4917.2 1186.46  5035.8 1184.37  5036.3 1183.87  5057.7 1183.87  5058.2 1184.37
  5061.2  1190.5  5067.9 1189.52  5075.4 1195.29  5140.1 1195.45  5157.1 1195.55
  5195.8  1196.5  5202.5 1195.95  5216.7 1196.31  5266.8 1198.29  5280.3 1199.75
  5315.5  1200.5  5408.1 1203.59  5453.5 1205.91  5528.4 1206.43  5535.5 1207.09
#Mann= 7 ,-1 , 0
  4490.2     .05       0  5035.8     .03       0  5058.2     .05       0
  5140.1     .12       0  5157.1     .05       0  5315.5     .12       0
  5453.5     .05       0
Bank Sta=5035.8,5058.2
XS Rating Curve= 0 ,0
Exp/Cntr=0.3,0.1

Type RM Length L Ch R = 1 ,31000   ,500,500,500
BEGIN DESCRIPTION:
SIXMILE CREEK 62.0
END DESCRIPTION:
XS GIS Cut Line= 3
      2791055.69      10216053.1      2791266.27     10215781.47
       2791655.7      10215453.1
#Sta/Elev= 30
  4656.3 1209.21  4692.5 1206.09  4713.3 1203.35  4770.2 1199.58  4812.9 1198.28
  4820.8  1197.6  4827.4  1196.1  4833.7    1196  4848.2 1193.49  4877.2 1191.54
    4884 1192.11  4891.7 1191.51  4941.5 1182.89  4955.9 1184.22  4991.2 1183.05
  4994.2 1182.37  4994.7 1181.87  5016.8 1182.37  5048.4 1186.16    5077 1188.19
  5090.8  1187.9  5126.4 1189.54  5147.2  1192.3    5155 1192.03  5175.8 1194.67
    5211 1197.66  5389.1  1205.2  5438.5 1205.76  5481.4 1208.76  5509.4 1209.87
#Mann= 3 ,-1 , 0
  4656.3     .05       0  4994.2     .05       0  5016.8     .05       0
Bank Sta=4994.2,5016.8
XS Rating Curve= 0 ,0
Exp/Cntr=0.3,0.1

Type RM Length L Ch R = 1 ,30500   ,500,500,500
BEGIN DESCRIPTION:
SIXMILE CREEK 61.0
END DESCRIPTION:
XS GIS Cut Line= 3
      2791405.67     10216353.12      2791627.17      10216125.1
       2792005.7     10215603.09
#Sta/Elev= 30
  4682.1 1206.88  4696.2 1205.05  4703.3 1202.77  4724.5 1199.44  4745.8 1198.13
  4752.7 1196.57  4766.9  1195.3  4802.7 1194.19  4883.9  1190.6  4908.4 1189.74
  4915.5 1187.98  4929.7  1180.7  4939.5 1180.59    4940 1180.09  4962.1 1180.59
  4964.9 1181.82  4986.3 1181.46  5028.2 1184.21  5051.4 1183.53  5122.5 1188.59
  5137.2    1191  5143.4 1193.02  5150.7 1193.52  5308.8 1198.08    5315 1199.12
  5365.3 1198.74  5400.8 1200.58  5495.2 1201.69  5572.5 1205.91  5644.8 1208.62
#Mann= 5 ,-1 , 0
  4682.1     .12       0  4802.7     .05       0  4883.9     .12       0
  4939.5     .03       0  4962.1     .05       0
Bank Sta=4939.5,4962.1
XS Rating Curve= 0 ,0
Exp/Cntr=0.3,0.1

Type RM Length L Ch R = 1 ,30000   ,500,500,500
BEGIN DESCRIPTION:
SIXMILE CREEK 60.0
END DESCRIPTION:
XS GIS Cut Line= 3
      2791755.68     10216903.11       2791948.8     10216506.31
      2792205.66     10216303.13
#Sta/Elev= 30
  4558.7 1213.23  4662.9 1203.92  4679.9 1203.36  4714.4 1199.82    4770 1196.15
  4781.2 1194.25  4814.5 1193.75  4820.8 1191.96  4826.3 1192.03  4848.9 1188.61
    4859 1188.87  4888.4 1185.89  4925.7  1184.5  4947.9 1179.65  4961.6 1178.05
  4981.1 1177.84  4981.6 1177.34  5003.8 1177.84  5028.6 1180.63  5043.1 1184.12
  5078.3  1187.4  5092.7 1190.48  5107.2 1191.83  5113.5 1193.68    5136 1189.22
  5162.4 1189.53  5235.4  1193.3  5270.6 1196.79  5292.8 1197.79  5327.5 1198.73
#Mann= 5 ,-1 , 0
  4558.7     .05       0  4981.1     .05       0  5003.8     .05       0
  5162.4     .12       0  5292.8     .05       0
Bank Sta=4981.1,5003.8
XS Rating Curve= 0 ,0
Exp/Cntr=0.3,0.1