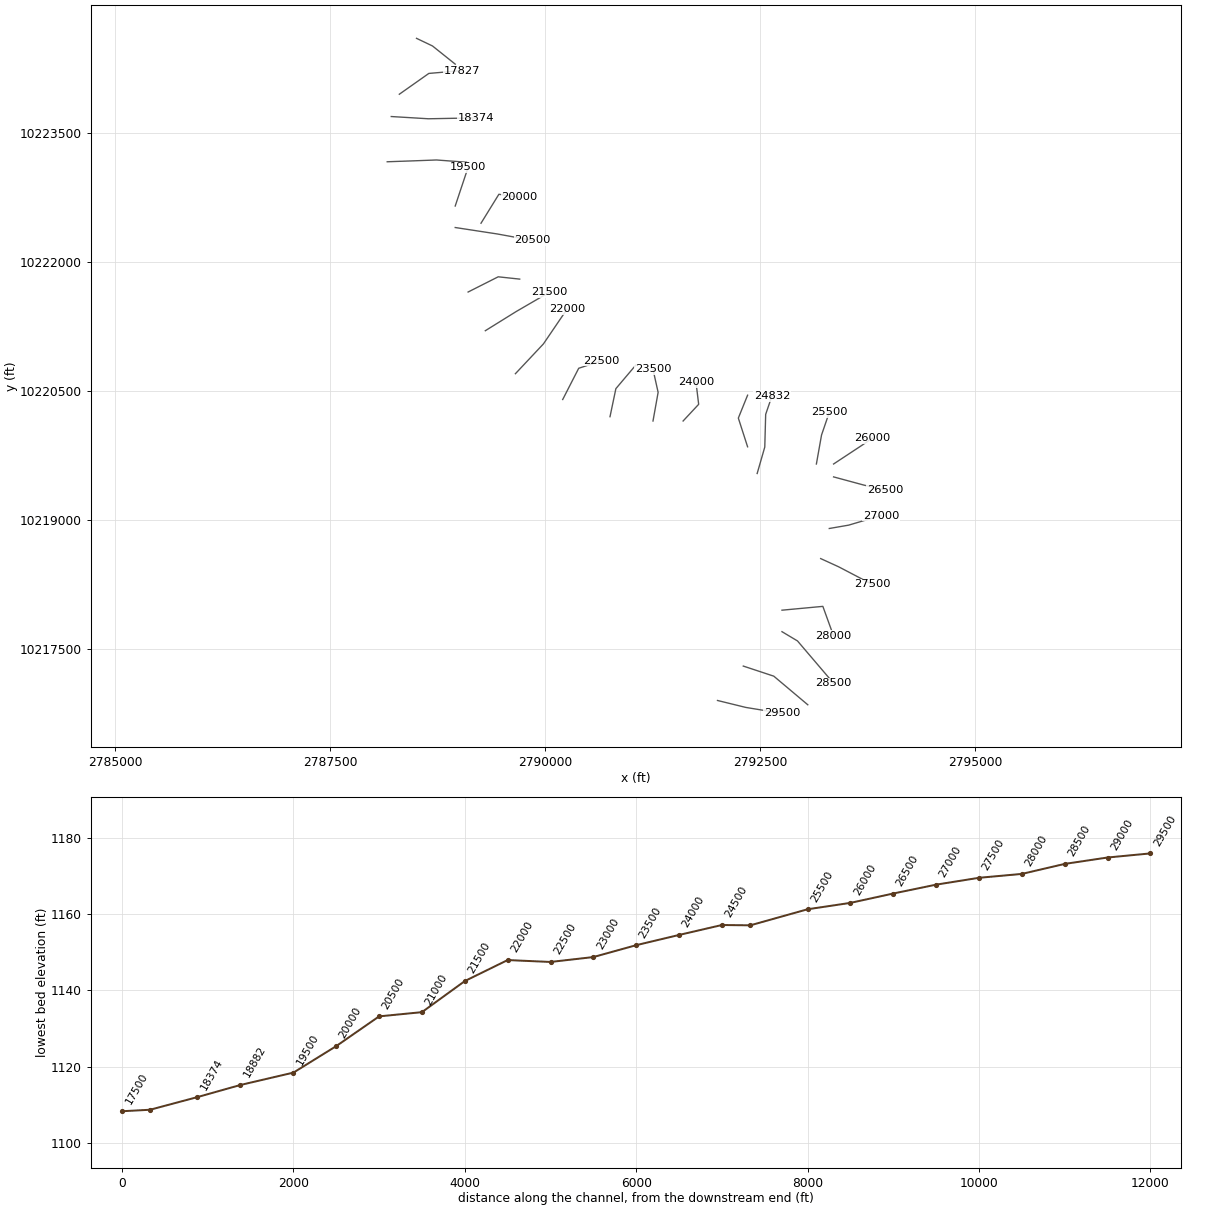
HEC-RAS study SIXMILE CREEK.prj: SIXMILE CREEK Base Level Engineering

--- SIXMILE CREEK.g01 (geometry) --- (continued)

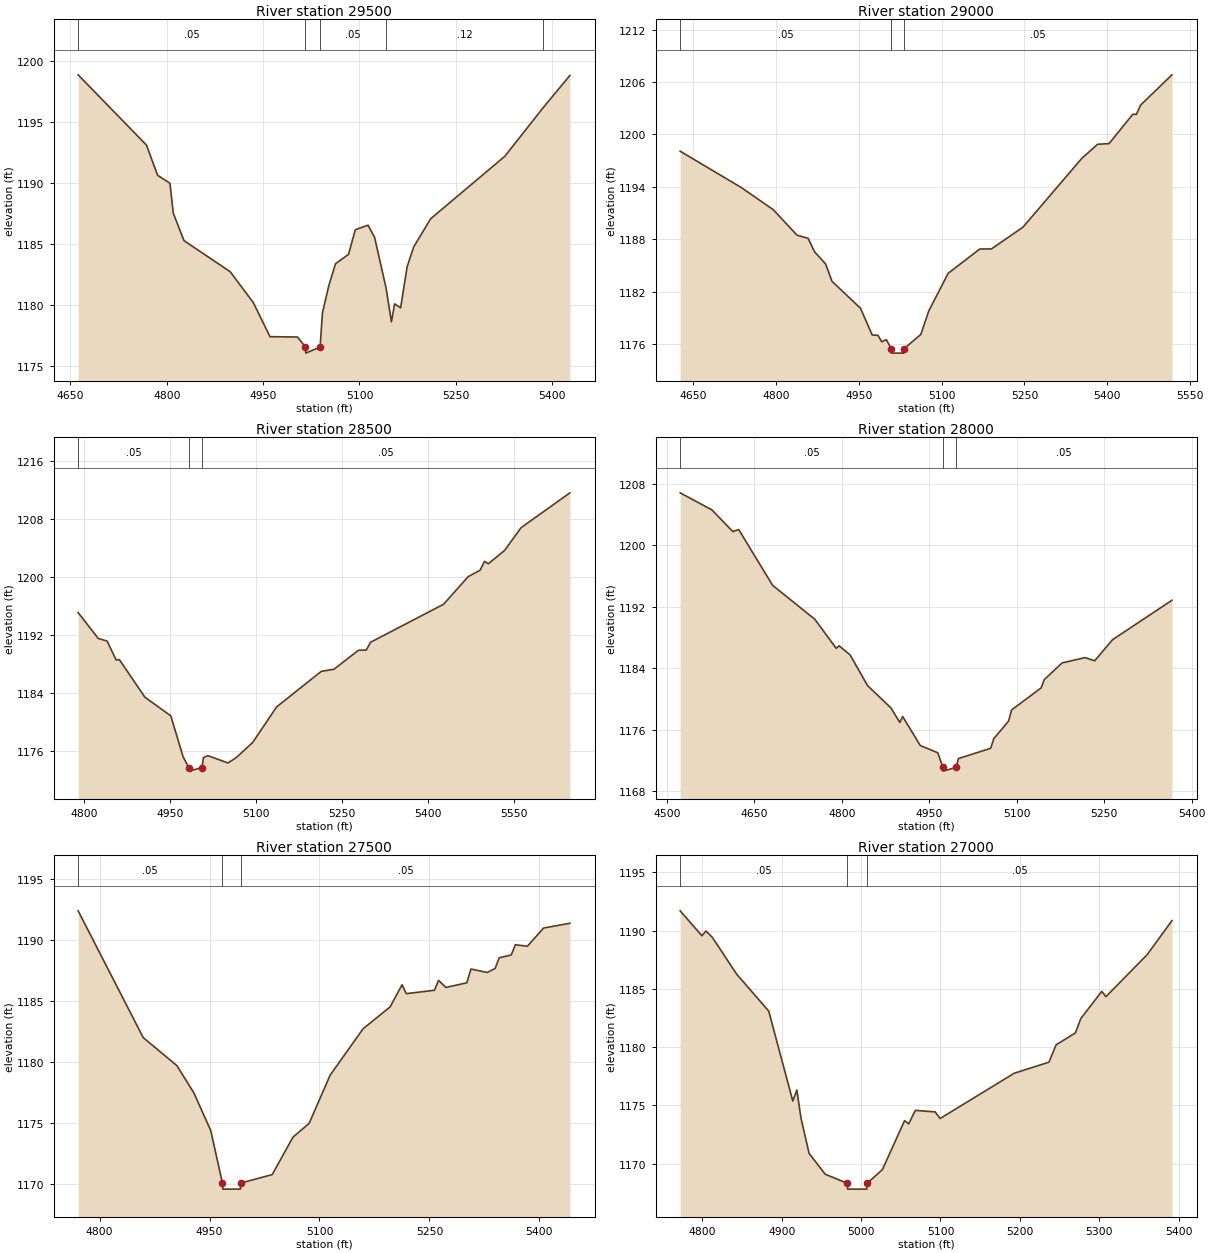
Type RM Length L Ch R = 1 ,29500   ,500,500,500
BEGIN DESCRIPTION:
SIXMILE CREEK 59.0
END DESCRIPTION:
XS GIS Cut Line= 3
      2792005.69     10216903.11      2792333.85     10216822.56
      2792755.67     10216753.11
#Sta/Elev= 30
  4662.1 1198.84  4768.6 1193.07  4785.7 1190.61    4805 1189.95  4810.2 1187.49
  4826.8 1185.25  4898.9 1182.69  4934.9 1180.15  4960.7 1177.37  5003.5 1177.34
  5015.9 1176.52  5016.4 1176.02  5038.7 1176.52  5042.4 1179.33  5052.5  1181.6
  5062.7 1183.35  5082.9 1184.12  5093.5 1186.14  5113.3 1186.51  5123.5 1185.52
  5141.3 1181.37  5149.7 1178.59  5154.7 1180.06    5164 1179.73  5174.1 1183.09
  5184.3 1184.72  5210.8 1187.04  5326.2 1192.16  5385.9 1196.15  5427.5 1198.79
#Mann= 5 ,-1 , 0
  4662.1     .05       0  5015.9     .05       0  5038.7     .05       0
  5141.3     .12       0  5385.9     .05       0
Bank Sta=5015.9,5038.7
XS Rating Curve= 0 ,0
Exp/Cntr=0.3,0.1

Type RM Length L Ch R = 1 ,29000   ,500,500,500
BEGIN DESCRIPTION:
SIXMILE CREEK 58.0
END DESCRIPTION:
XS GIS Cut Line= 3
      2792305.69     10217303.11      2792660.12     10217185.93
      2793055.72     10216853.08
#Sta/Elev= 30
  4626.7 1198.08  4737.7  1193.9  4795.2 1191.38  4838.2 1188.46  4858.4 1188.09
  4869.9 1186.56    4890 1185.16  4901.6 1183.17  4953.2 1180.08  4974.3 1177.02
  4984.8 1176.98  4991.6 1176.24    5000 1176.48  5008.9 1175.44  5009.4 1174.94
  5031.3 1174.94  5031.8 1175.44  5062.4 1177.08  5076.7 1179.76  5111.8 1184.08
  5169.1 1186.87  5190.2 1186.88  5247.1 1189.36  5353.7 1197.25  5382.3 1198.87
  5403.2 1198.95  5446.1 1202.31  5452.6  1202.3  5460.4 1203.37    5517 1206.83
#Mann= 3 ,-1 , 0
  4626.7     .05       0  5008.9     .03       0  5031.8     .05       0
Bank Sta=5008.9,5031.8
XS Rating Curve= 0 ,0
Exp/Cntr=0.3,0.1

Type RM Length L Ch R = 1 ,28500   ,500,500,500
BEGIN DESCRIPTION:
SIXMILE CREEK 57.0
END DESCRIPTION:
XS GIS Cut Line= 3
      2792755.72     10217703.09        2792936.      10217595.4
      2793355.68     10217103.11
#Sta/Elev= 30
    4790 1195.15    4825 1191.57  4840.5 1191.21  4856.1 1188.61  4861.9 1188.64
  4906.4 1183.46  4951.5 1180.89  4972.9 1175.24  4982.8 1173.76  4983.3 1173.26
  5005.7 1173.76  5008.4 1175.13  5016.1 1175.39  5051.2 1174.39  5065.5 1175.13
  5094.1 1177.21  5135.8 1182.12  5213.7 1187.03  5235.7 1187.32  5278.5 1189.94
  5292.1 1189.97  5299.4 1191.04  5426.7 1196.29  5469.6  1200.1  5490.4 1200.99
  5498.1 1202.22  5504.7 1201.88  5533.2 1203.73  5561.8 1206.86  5646.9 1211.67
#Mann= 3 ,-1 , 0
    4790     .05       0  4982.8     .03       0  5005.7     .05       0
Bank Sta=4982.8,5005.7
XS Rating Curve= 0 ,0
Exp/Cntr=0.3,0.1

Type RM Length L Ch R = 1 ,28000   ,500,500,500
BEGIN DESCRIPTION:
SIXMILE CREEK 56.0
END DESCRIPTION:
XS GIS Cut Line= 3
      2792755.67     10217953.11      2793230.91     10217997.45
      2793355.67     10217653.16
#Sta/Elev= 30
  4522.7 1206.79  4577.2 1204.57  4613.1 1201.75  4623.1 1202.02  4681.3 1194.77
  4753.7 1190.36  4790.3 1186.59  4795.4 1186.91    4814 1185.75  4844.1 1181.75
  4884.3 1178.84  4899.4 1176.95  4904.4 1177.72  4934.5 1173.96  4964.6 1173.01
  4973.3 1171.13  4973.8 1170.63  4996.2 1171.13  4999.9 1172.26  5055.3  1173.6
  5060.6 1174.84  5085.9 1177.12  5091.2 1178.58  5141.8 1181.44  5147.2 1182.52
  5177.8 1184.69  5217.3 1185.38  5233.7 1184.97  5264.4 1187.71  5366.2 1192.83
#Mann= 3 ,-1 , 0
  4522.7     .05       0  4973.3     .05       0  4996.2     .05       0
Bank Sta=4973.3,4996.2
XS Rating Curve= 0 ,0
Exp/Cntr=0.3,0.1

Type RM Length L Ch R = 1 ,27500   ,500,500,500
BEGIN DESCRIPTION:
SIXMILE CREEK 55.0
END DESCRIPTION:
XS GIS Cut Line= 3
       2793205.7     10218553.11      2793414.23     10218457.74
      2793805.67     10218253.12
#Sta/Elev= 30
  4770.7 1192.42  4859.5 1182.03  4905.5 1179.73  4928.6  1177.5  4951.6 1174.42
  4967.6 1170.11  4968.1 1169.61  4992.1 1169.61  4992.6 1170.11  5035.5  1170.8
  5063.8 1173.87  5085.9    1175  5114.5 1178.95  5159.6 1182.76  5196.3 1184.54
  5212.7 1186.36  5218.4 1185.63  5256.9 1185.91  5262.5 1186.72  5272.5 1186.14
    5301 1186.52  5306.7 1187.65  5328.9 1187.37  5339.6 1187.69  5345.2 1188.57
  5361.6  1188.8  5367.3 1189.64  5383.7 1189.52  5405.8 1191.01  5441.7  1191.4
#Mann= 3 ,-1 , 0
  4770.7     .05       0  4967.6     .05       0  4992.6     .05       0
Bank Sta=4967.6,4992.6
XS Rating Curve= 0 ,0
Exp/Cntr=0.3,0.1

Type RM Length L Ch R = 1 ,27000   ,500,500,500
BEGIN DESCRIPTION:
SIXMILE CREEK 54.0
END DESCRIPTION:
XS GIS Cut Line= 3
      2793305.67     10218903.11      2793530.24     10218941.91
      2793905.72     10219053.12
#Sta/Elev= 30
  4772.1  1191.7  4799.5 1189.56  4804.6 1189.97  4812.7 1189.42  4843.2 1186.27
  4883.7 1183.09    4914 1175.37  4919.1 1176.32  4924.3 1173.91  4934.5 1170.88
  4954.8 1169.09  4982.6 1168.31  4983.1 1167.81  5007.2 1167.81  5007.7 1168.31
  5026.8 1169.48  5054.8 1173.69    5060 1173.41  5068.3 1174.57  5093.3 1174.44
  5099.5 1173.87    5193 1177.76  5236.7 1178.71  5245.6 1180.19    5270 1181.22
  5276.8 1182.45  5303.2 1184.79  5308.4 1184.33  5360.3 1187.93  5391.6 1190.86
#Mann= 3 ,-1 , 0
  4772.1     .05       0  4982.6     .03       0  5007.7     .05       0
Bank Sta=4982.6,5007.7
XS Rating Curve= 0 ,0
Exp/Cntr=0.3,0.1

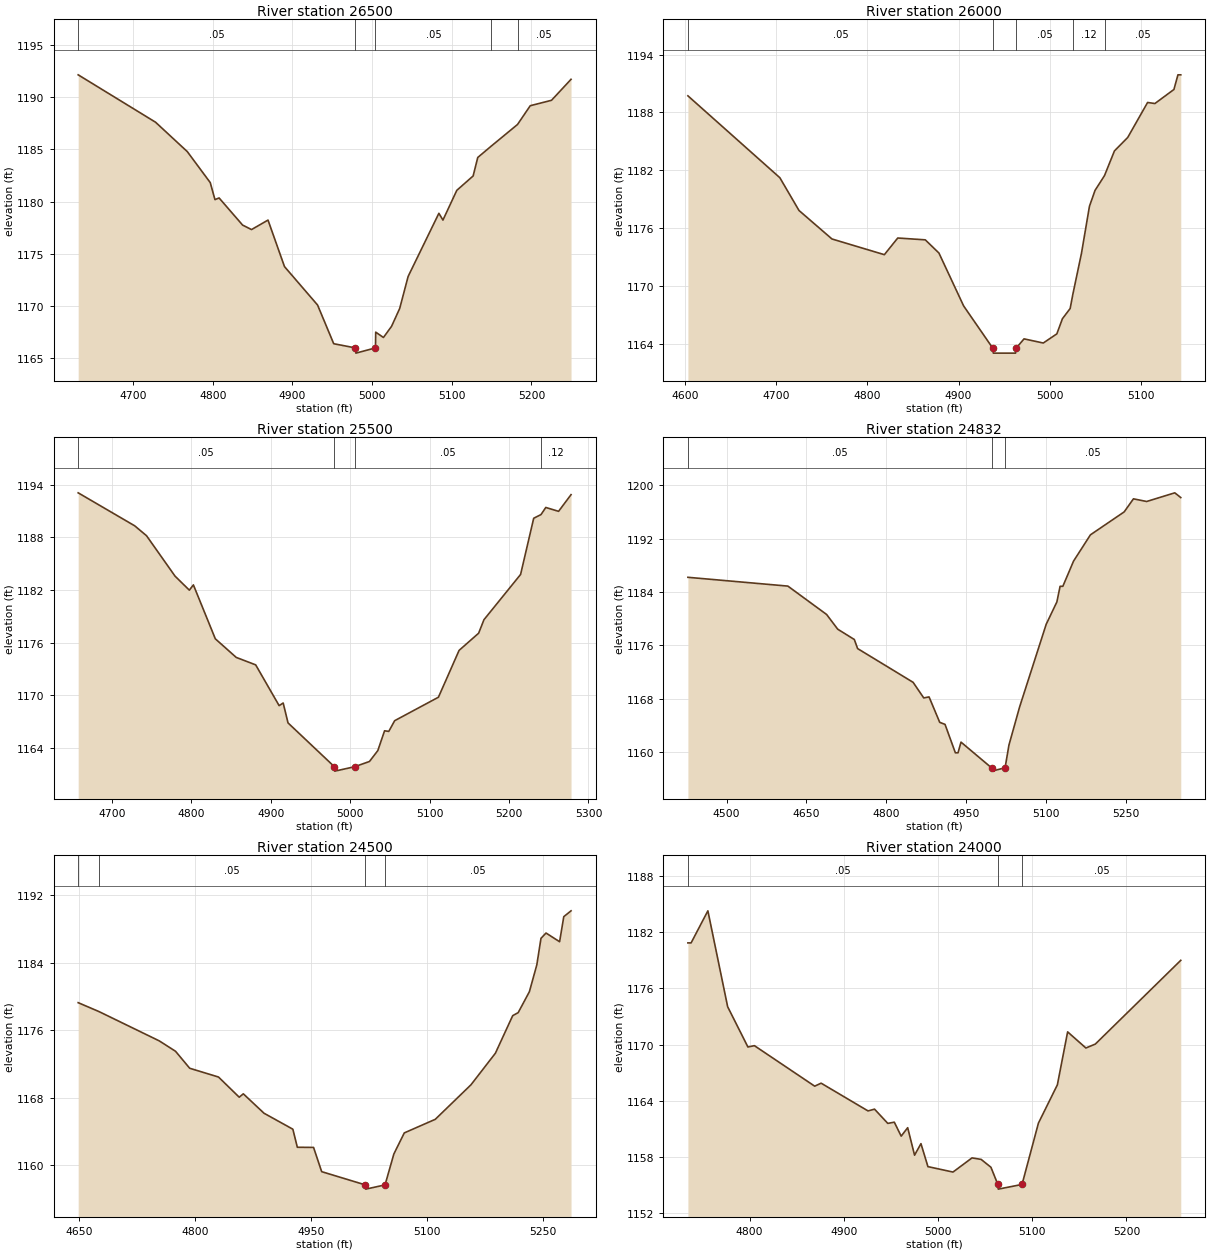
Type RM Length L Ch R = 1 ,26500   ,500,500,500
BEGIN DESCRIPTION:
SIXMILE CREEK 53.0
END DESCRIPTION:
XS GIS Cut Line= 3
      2793355.65     10219503.12      2793711.75      10219406.8
      2793955.71     10219353.11
#Sta/Elev= 30
  4631.1 1192.15  4728.2 1187.61  4768.1 1184.79  4796.9 1181.82  4802.8 1180.19
    4808 1180.35  4837.5 1177.75  4848.7 1177.32  4869.4 1178.23  4890.1 1173.77
  4931.6 1170.09  4951.9 1166.38  4979.2 1165.98  4979.7 1165.48  5004.3 1165.98
  5004.6 1167.49  5014.3 1166.98  5024.5 1168.05  5034.7 1169.76  5045.3 1172.83
  5083.9 1178.88    5089 1178.23  5106.4 1181.08  5126.9 1182.46  5132.7 1184.23
  5149.5 1185.31  5182.6 1187.39  5198.6 1189.19  5225.3 1189.71  5249.8 1191.72
#Mann= 5 ,-1 , 0
  4631.1     .05       0  4979.2     .03       0  5004.3     .05       0
  5149.5     .12       0  5182.6     .05       0
Bank Sta=4979.2,5004.3
XS Rating Curve= 0 ,0
Exp/Cntr=0.3,0.1

Type RM Length L Ch R = 1 ,26000   ,500,500,500
BEGIN DESCRIPTION:
SIXMILE CREEK 52.0
END DESCRIPTION:
XS GIS Cut Line= 3
      2793355.67      10219653.1       2793687.1     10219871.64
      2793805.71     10219953.13
#Sta/Elev= 30
    4603 1189.73  4703.9 1181.23  4724.9 1177.83  4761.1 1174.87  4818.6 1173.24
  4833.3 1174.97  4863.5 1174.78  4878.5 1173.41  4905.6 1167.92  4937.7 1163.52
  4938.2 1163.02  4962.6 1163.02  4963.1 1163.52  4971.9  1164.5    4993 1164.07
  5007.9 1165.02    5014 1166.59  5022.5 1167.65  5025.4  1169.1  5034.9 1173.37
  5043.7 1178.27  5049.8 1179.91  5060.2 1181.45  5071.1 1184.01  5085.7 1185.41
  5107.5 1189.04  5115.5 1188.93  5136.4 1190.39  5140.8 1191.91  5143.9 1191.91
#Mann= 5 ,-1 , 0
    4603     .05       0  4937.7     .05       0  4963.1     .05       0
  5025.4     .12       0  5060.2     .05       0
Bank Sta=4937.7,4963.1
XS Rating Curve= 0 ,0
Exp/Cntr=0.3,0.1

Type RM Length L Ch R = 1 ,25500   ,668,668,668
BEGIN DESCRIPTION:
SIXMILE CREEK 51.0
END DESCRIPTION:
XS GIS Cut Line= 3
      2793155.69     10219653.14      2793215.62     10219990.05
       2793305.7     10220253.16
#Sta/Elev= 30
  4657.8 1193.08  4728.9 1189.32  4743.8 1188.19  4779.7 1183.58  4797.7 1181.98
  4802.8 1182.58  4830.4 1176.43  4856.7 1174.31  4881.2 1173.46  4910.7 1168.81
  4915.8 1169.11  4921.9 1166.84  4980.3 1161.84  4980.8 1161.34  5005.7 1161.84
  5024.4 1162.44  5034.9 1163.68  5043.4 1165.94  5048.7 1165.87  5056.1 1167.09
  5111.2 1169.77  5137.2 1175.11  5161.8 1177.07  5168.5 1178.61  5214.6 1183.77
  5231.1 1190.18  5240.3  1190.6  5246.3 1191.41  5262.4 1190.97  5278.1 1192.87
#Mann= 4 ,-1 , 0
  4657.8     .05       0  4980.3     .05       0  5005.7     .05       0
  5240.3     .12       0
Bank Sta=4980.3,5005.7
XS Rating Curve= 0 ,0
Exp/Cntr=0.3,0.1

Type RM Length L Ch R = 1 ,24832   ,332,332,332
BEGIN DESCRIPTION:
Mapping XS c1aa224d
END DESCRIPTION:
XS GIS Cut Line= 4
      2792467.01      10219542.7      2792555.56     10219850.03
      2792565.98     10220230.23      2792638.89     10220443.75
#Sta/Elev= 30
  4427.4 1186.19  4615.2 1184.87    4688 1180.61  4708.8 1178.41    4740 1176.86
  4746.2  1175.5  4850.4 1170.44  4870.4  1168.1  4880.4 1168.25  4900.4 1164.44
  4910.4 1164.13  4929.8 1159.87  4934.8 1159.87  4940.4 1161.47  4997.7 1157.62
  4998.2 1157.12  5023.2 1157.62  5030.4 1161.01  5050.4 1166.73  5100.4 1179.14
  5120.5  1182.5  5126.5 1184.84  5131.7 1184.84  5151.8 1188.62  5183.5 1192.56
  5246.9    1196  5264.3 1197.96  5289.1 1197.56    5342 1198.86  5353.2 1198.15
#Mann= 3 ,-1 , 0
  4427.4     .05       0  4997.7     .05       0  5023.2     .05       0
Bank Sta=4997.7,5023.2
XS Rating Curve= 0 ,0
Exp/Cntr=0.3,0.1

Type RM Length L Ch R = 1 ,24500   ,500,500,500
BEGIN DESCRIPTION:
SIXMILE CREEK 49.0
END DESCRIPTION:
XS GIS Cut Line= 3
      2792355.67     10219853.15      2792248.11     10220187.16
      2792355.69     10220453.12
#Sta/Elev= 30
  4649.1 1179.29  4675.9 1178.24  4754.1 1174.76  4775.1 1173.53  4793.4 1171.52
  4830.7 1170.48  4857.5 1168.09  4862.8 1168.49  4889.6 1166.19  4926.9  1164.3
  4932.7 1162.16  4953.7 1162.14  4964.2 1159.27  5020.7  1157.7  5021.2  1157.2
  5046.2  1157.7  5057.6 1161.36  5071.1 1163.86  5111.2 1165.47  5157.4 1169.56
    5189  1173.3  5211.4 1177.75  5218.5 1178.11    5233 1180.59  5242.6 1183.77
    5248 1186.91  5254.5 1187.54  5272.1 1186.51  5277.5 1189.48  5286.9 1190.17
#Mann= 4 ,-1 , 0
  4649.1     .12       0  4675.9     .05       0  5020.7     .05       0
  5046.2     .05       0
Bank Sta=5020.7,5046.2
XS Rating Curve= 0 ,0
Exp/Cntr=0.3,0.1

Type RM Length L Ch R = 1 ,24000   ,500,500,500
BEGIN DESCRIPTION:
SIXMILE CREEK 48.0
END DESCRIPTION:
XS GIS Cut Line= 3
       2791605.7     10220153.13      2791786.77     10220347.31
      2791755.68     10220603.12
#Sta/Elev= 30
  4734.5 1180.85  4737.9 1180.85  4755.7 1184.27  4776.7 1174.04  4798.2 1169.75
  4805.1 1169.89  4869.1 1165.57  4875.9 1165.89  4925.7 1162.93  4932.6 1163.12
  4946.7  1161.6  4953.6 1161.73  4960.9 1160.24  4967.8 1161.14  4975.1 1158.21
  4981.9 1159.44  4989.3 1156.99  5015.9 1156.41  5036.1 1157.92  5045.8 1157.76
  5056.2 1156.92  5063.5 1155.09    5064 1154.59  5089.2 1155.09  5106.6 1161.63
  5126.7 1165.71  5137.6 1171.36    5157 1169.64    5167 1170.06  5257.7 1178.99
#Mann= 3 ,-1 , 0
  4734.5     .05       0  5063.5     .03       0  5089.2     .05       0
Bank Sta=5063.5,5089.2
XS Rating Curve= 0 ,0
Exp/Cntr=0.3,0.1

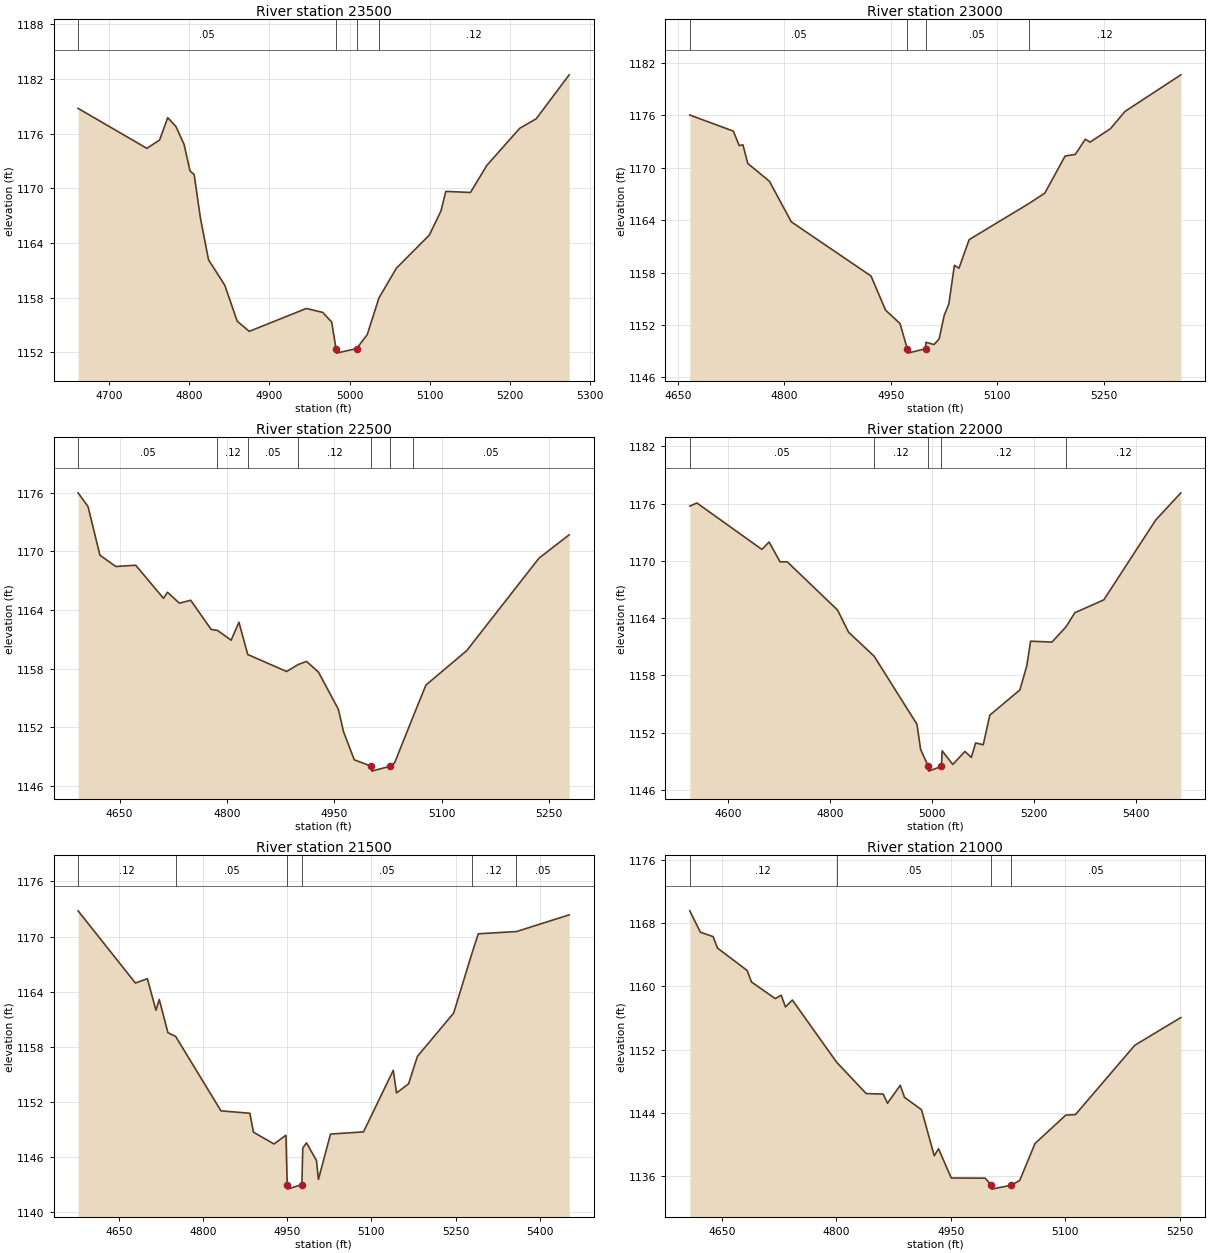
Type RM Length L Ch R = 1 ,23500   ,500,500,500
BEGIN DESCRIPTION:
SIXMILE CREEK 47.0
END DESCRIPTION:
XS GIS Cut Line= 3
      2791255.69     10220153.13      2791315.33     10220486.23
      2791255.68     10220753.15
#Sta/Elev= 30
  4661.6 1178.76  4747.3 1174.37  4763.2 1175.29  4773.3 1177.74  4783.5 1176.77
  4793.7  1174.8  4801.1 1171.88  4806.2 1171.51    4814 1166.74  4824.1 1162.15
  4844.4 1159.35  4859.9  1155.4  4874.9 1154.29    4946  1156.8  4966.4 1156.37
  4977.6 1155.31    4983  1152.4  4983.5  1151.9  5008.7  1152.4  5021.9 1153.93
  5036.4 1157.94  5058.3 1161.23  5099.3 1164.86  5113.8 1167.51  5119.8 1169.65
  5150.5 1169.53    5171 1172.51    5212 1176.58  5232.5 1177.62  5273.5 1182.44
#Mann= 4 ,-1 , 0
  4661.6     .05       0    4983     .05       0  5008.7     .05       0
  5036.4     .12       0
Bank Sta=4983,5008.7
XS Rating Curve= 0 ,0
Exp/Cntr=0.3,0.1

Type RM Length L Ch R = 1 ,23000   ,500,500,500
BEGIN DESCRIPTION:
SIXMILE CREEK 46.0
END DESCRIPTION:
XS GIS Cut Line= 3
      2790755.69     10220203.16      2790824.01     10220529.38
      2791055.68     10220803.11
#Sta/Elev= 30
  4666.7 1176.03    4728 1174.19  4736.4 1172.53  4741.6 1172.62  4748.4 1170.49
    4779 1168.44  4809.7 1163.81  4922.1  1157.6  4942.5 1153.71  4962.9 1152.16
  4973.2 1149.28  4973.7 1148.78    4999 1149.28  4999.4 1150.02  5010.9 1149.76
    5018 1150.41  5025.2 1153.11  5031.7 1154.41  5039.5 1158.83    5046  1158.5
  5060.3 1161.77  5144.5  1165.9  5166.9 1167.09  5195.5 1171.34  5209.8 1171.52
    5224 1173.26  5230.6 1172.93  5259.2 1174.45    5280 1176.45  5358.6 1180.63
#Mann= 4 ,-1 , 0
  4666.7     .05       0  4973.2     .05       0    4999     .05       0
  5144.5     .12       0
Bank Sta=4973.2,4999
XS Rating Curve= 0 ,0
Exp/Cntr=0.3,0.1

Type RM Length L Ch R = 1 ,22500   ,500,500,500
BEGIN DESCRIPTION:
SIXMILE CREEK 45.0
END DESCRIPTION:
XS GIS Cut Line= 3
      2790205.67     10220403.09      2790391.74     10220766.31
      2790655.73     10220853.13
#Sta/Elev= 30
  4591.9 1176.01  4605.8  1174.6  4622.4 1169.62  4644.6 1168.46  4672.4 1168.59
  4711.2  1165.2  4716.8 1165.82  4733.4  1164.7  4749.2    1165  4777.8 1162.01
  4786.6 1161.91  4805.7 1160.91  4816.6 1162.75  4828.9 1159.44  4883.2  1157.7
  4899.5 1158.42    4911 1158.73  4927.6 1157.65  4955.5 1153.83  4962.7 1151.53
  4977.7 1148.65  5001.7 1147.99  5002.2 1147.49  5027.6 1147.99  5034.1 1148.34
  5060.2 1153.13  5077.8 1156.31  5134.8 1159.84  5235.7 1169.31  5277.9 1171.71
#Mann= 7 ,-1 , 0
  4591.9     .05       0  4786.6     .12       0  4828.9     .05       0
  4899.5     .12       0  5001.7     .07       0  5027.6     .12       0
  5060.2     .05       0
Bank Sta=5001.7,5027.6
XS Rating Curve= 0 ,0
Exp/Cntr=0.3,0.1

Type RM Length L Ch R = 1 ,22000   ,500,500,500
BEGIN DESCRIPTION:
SIXMILE CREEK 44.0
END DESCRIPTION:
XS GIS Cut Line= 3
      2789655.69     10220703.11      2789981.58     10221049.92
      2790255.66     10221453.08
#Sta/Elev= 30
  4524.1 1175.73    4538 1176.06  4665.5  1171.2  4679.7 1171.97  4701.1  1169.9
  4715.3  1169.9    4814 1164.85  4835.5 1162.54  4885.9 1160.01  4969.8 1152.89
  4976.9 1150.27    4992 1148.49  4992.5 1147.99  5017.9 1148.49  5019.1 1150.12
  5040.1 1148.69  5063.9 1150.05  5076.4 1149.43  5084.9 1150.94  5099.8 1150.75
  5112.7 1153.85  5171.7 1156.49  5185.2    1159  5192.7 1161.59  5234.6  1161.5
  5262.3  1163.1  5279.5 1164.57  5336.4 1165.92  5438.1 1174.27  5487.5 1177.12
#Mann= 5 ,-1 , 0
  4524.1     .05       0  4885.9     .12       0    4992     .07       0
  5017.9     .12       0  5262.3     .12       0
Bank Sta=4992,5017.9
XS Rating Curve= 0 ,0
Exp/Cntr=0.3,0.1

Type RM Length L Ch R = 1 ,21500   ,500,500,500
BEGIN DESCRIPTION:
SIXMILE CREEK 43.0
END DESCRIPTION:
XS GIS Cut Line= 3
      2789305.72     10221203.13      2789664.64     10221426.02
      2790055.68     10221653.11
#Sta/Elev= 30
  4577.5  1172.8  4679.6 1164.93  4700.9  1165.4  4716.2 1161.97  4722.1 1163.14
  4737.5 1159.52  4751.3 1159.11    4832    1151  4883.5 1150.74  4889.8 1148.68
  4926.4 1147.39  4947.7 1148.34    4950 1142.97  4950.5 1142.47  4976.1 1142.97
  4977.7 1146.93  4984.3 1147.52  5002.1 1145.59  5005.6 1143.53  5027.1 1148.47
  5085.9 1148.71  5138.9 1155.42  5144.7 1152.95  5166.2 1153.95  5181.9 1156.94
  5246.5 1161.66    5279 1168.16  5290.3  1170.3  5358.3 1170.54  5452.2 1172.36
#Mann= 6 ,-1 , 0
  4577.5     .12       0  4751.3     .05       0    4950     .05       0
  4976.1     .05       0    5279     .12       0  5358.3     .05       0
Bank Sta=4950,4976.1
XS Rating Curve= 0 ,0
Exp/Cntr=0.3,0.1

Type RM Length L Ch R = 1 ,21000   ,500,500,500
BEGIN DESCRIPTION:
SIXMILE CREEK 42.0
END DESCRIPTION:
XS GIS Cut Line= 3
       2789105.7     10221653.12      2789455.54     10221829.97
       2789705.7     10221803.11
#Sta/Elev= 30
    4608 1169.59  4621.9 1166.88  4638.6 1166.32  4644.2 1164.88  4683.2 1162.02
  4688.8 1160.57    4720 1158.46  4727.8 1158.89  4733.4  1157.4  4742.4 1158.28
  4800.4  1150.4  4839.2 1146.42  4861.5 1146.35  4867.1 1145.19  4883.8 1147.47
  4889.4 1145.94  4911.7 1144.37  4928.4 1138.53    4934 1139.42  4950.7 1135.71
  4995.2 1135.69  5003.2  1134.8  5003.7  1134.3  5029.3  1134.8  5040.4  1135.4
  5060.5 1140.09  5100.7 1143.68  5113.4 1143.75  5191.2 1152.54  5251.6 1156.06
#Mann= 4 ,-1 , 0
    4608     .12       0  4800.4     .05       0  5003.2     .05       0
  5029.3     .05       0
Bank Sta=5003.2,5029.3
XS Rating Curve= 0 ,0
Exp/Cntr=0.3,0.1

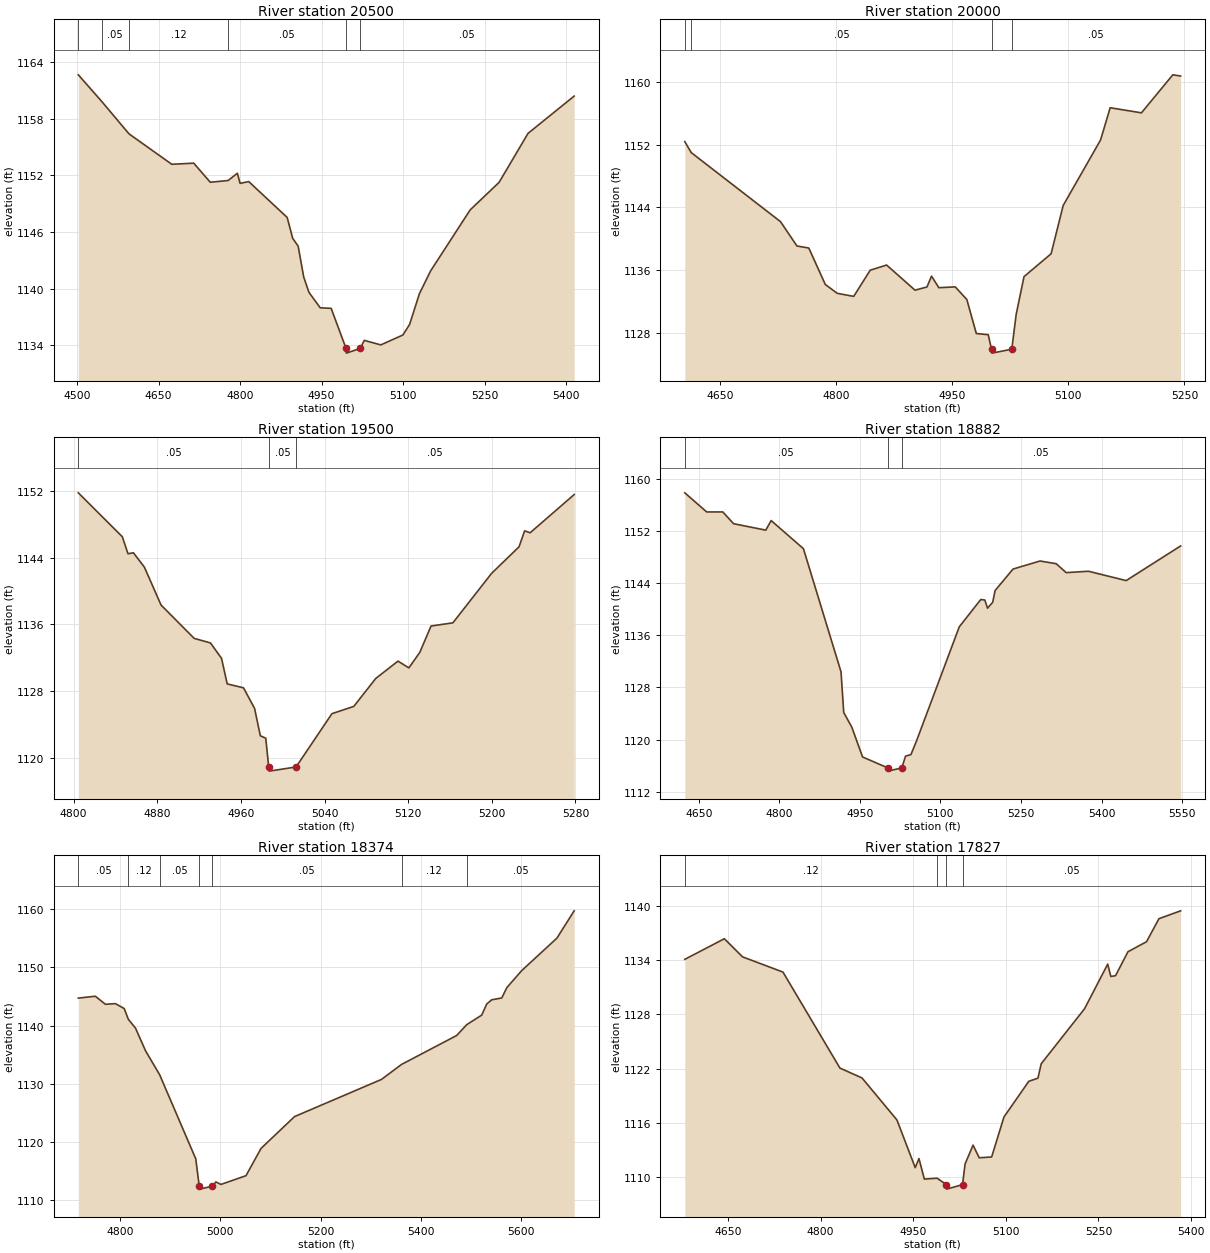
Type RM Length L Ch R = 1 ,20500   ,500,500,500
BEGIN DESCRIPTION:
SIXMILE CREEK 41.0
END DESCRIPTION:
XS GIS Cut Line= 3
      2788955.71     10222403.11      2789447.67     10222327.71
       2789855.7     10222253.11
#Sta/Elev= 30
  4502.3 1162.65  4545.1 1159.85  4595.6  1156.4  4674.3 1153.18  4714.7  1153.3
  4745.1 1151.28  4777.9 1151.46    4795 1152.23    4800 1151.16  4815.9 1151.35
  4886.7 1147.55  4896.8 1145.34  4906.9 1144.51  4917.1 1141.24  4926.7 1139.63
  4947.4 1137.99  4967.6 1137.93    4995 1133.69  4995.5 1133.19  5021.2 1133.69
  5028.5 1134.54    5059 1134.06  5099.6 1135.11  5111.9 1136.22  5130.1 1139.49
  5150.5 1141.88  5223.4 1148.35  5276.7 1151.27  5329.9 1156.45  5414.8  1160.4
#Mann= 6 ,-1 , 0
  4502.3     .12       0  4545.1     .05       0  4595.6     .12       0
  4777.9     .05       0    4995     .05       0  5021.2     .05       0
Bank Sta=4995,5021.2
XS Rating Curve= 0 ,0
Exp/Cntr=0.3,0.1

Type RM Length L Ch R = 1 ,20000   ,500,500,500
BEGIN DESCRIPTION:
SIXMILE CREEK 40.0
END DESCRIPTION:
XS GIS Cut Line= 3
      2789255.68      10222453.1      2789463.43     10222789.64
      2789705.69     10222753.11
#Sta/Elev= 30
  4604.5 1152.37  4612.8 1150.97  4728.1 1142.16  4749.4 1139.05  4764.7 1138.79
    4786 1134.14  4801.4 1133.01  4822.7 1132.62    4844 1135.96  4865.2 1136.62
  4901.9 1133.41  4917.3 1133.82  4923.2  1135.2  4932.7 1133.73  4953.9 1133.83
  4968.8 1132.23  4981.1 1127.88  4996.5 1127.73  5000.7 1125.88  5001.2 1125.38
  5026.9 1125.88  5032.6 1130.34  5042.7 1135.14  5077.7 1138.06  5093.3 1144.22
  5141.6 1152.58    5154 1156.69  5194.4 1156.04  5234.9 1160.89    5245 1160.74
#Mann= 4 ,-1 , 0
  4604.5     .12       0  4612.8     .05       0  5000.7     .05       0
  5026.9     .05       0
Bank Sta=5000.7,5026.9
XS Rating Curve= 0 ,0
Exp/Cntr=0.3,0.1

Type RM Length L Ch R = 1 ,19500   ,618,618,618
BEGIN DESCRIPTION:
SIXMILE CREEK 39.0
END DESCRIPTION:
XS GIS Cut Line= 3
      2788955.69     10222653.14      2789017.37     10222838.66
      2789105.68      10223103.1
#Sta/Elev= 30
  4804.5 1151.78  4846.6 1146.51    4852 1144.48  4857.2 1144.59  4867.7 1142.87
  4883.6 1138.33  4915.3 1134.33  4930.9 1133.78  4941.5 1131.93  4946.9 1128.87
  4962.5  1128.4  4973.1 1125.93  4978.6 1122.65  4983.8 1122.36  4986.6 1118.91
  4987.1 1118.41  5012.8 1118.91  5047.1  1125.3    5068 1126.17    5089 1129.52
  5110.3  1131.6  5120.7 1130.79  5131.2 1132.66  5141.9 1135.81  5162.8 1136.19
  5199.8 1142.12  5226.1 1145.31  5231.4 1147.22  5236.7 1146.99  5278.8 1151.57
#Mann= 3 ,-1 , 0
  4804.5     .05       0  4986.6     .05       0  5012.8     .05       0
Bank Sta=4986.6,5012.8
XS Rating Curve= 0 ,0
Exp/Cntr=0.3,0.1

Type RM Length L Ch R = 1 ,18882   ,508,508,508
BEGIN DESCRIPTION:
Mapping XS 541ec96c
END DESCRIPTION:
XS GIS Cut Line= 4
      2788164.94     10223167.73      2788461.81     10223178.15
      2788737.86     10223188.57      2789086.79     10223162.53
#Sta/Elev= 30
  4624.1 1157.81  4664.9 1154.88  4694.9 1154.88  4714.9 1153.08  4774.9 1152.09
  4784.9 1153.56    4845 1149.25    4915 1130.37    4920 1124.15    4935 1121.91
  4955.1 1117.33  5001.9 1115.66  5002.4 1115.16  5028.2 1115.66  5035.1 1117.46
  5045.1 1117.69  5055.1 1119.69  5135.2 1137.28  5175.2 1141.46  5182.8 1141.38
  5187.8 1140.13  5197.4 1141.04  5201.9 1142.84  5235.3 1146.13  5285.5 1147.36
  5315.6 1146.95  5334.2 1145.58  5375.7 1145.79  5445.9 1144.36  5547.3 1149.67
#Mann= 3 ,-1 , 0
  4624.1     .05       0  5001.9     .05       0  5028.2     .05       0
Bank Sta=5001.9,5028.2
XS Rating Curve= 0 ,0
Exp/Cntr=0.3,0.1

Type RM Length L Ch R = 1 ,18374   ,547,547,547
BEGIN DESCRIPTION:
Mapping XS bfd8b8e7
END DESCRIPTION:
XS GIS Cut Line= 3
      2788211.83     10223693.77      2788644.11     10223667.73
      2789200.05     10223678.13
#Sta/Elev= 30
  4716.6 1144.73  4750.5 1145.05  4770.6 1143.67  4790.6 1143.78  4808.2 1142.93
  4816.3  1141.1  4830.7 1139.57  4850.7 1135.68  4878.9 1131.56  4950.9 1117.13
  4957.8 1112.44  4958.3 1111.94  4984.1 1112.44    4991 1113.18    5001 1112.74
  5051.1 1114.25  5081.1 1118.93  5147.9 1124.39  5321.3 1130.77  5361.3 1133.34
  5471.3 1138.31  5491.4 1140.17  5521.3 1141.81  5531.3 1143.72  5541.3 1144.44
  5561.3 1144.75  5571.3 1146.52  5601.3 1149.47  5671.3 1155.02  5705.7 1159.71
#Mann= 7 ,-1 , 0
  4716.6     .05       0  4816.3     .12       0  4878.9     .05       0
  4957.8     .05       0  4984.1     .05       0  5361.3     .12       0
  5491.4     .05       0
Bank Sta=4957.8,4984.1
XS Rating Curve= 0 ,0
Exp/Cntr=0.3,0.1

Type RM Length L Ch R = 1 ,17827   ,327,327,327
BEGIN DESCRIPTION:
SIXMILE CREEK 36.0
END DESCRIPTION:
XS GIS Cut Line= 3
      2788305.66     10223953.09        2788649.       10224195.
      2789030.67     10224228.11
#Sta/Elev= 30
    4580 1134.09  4644.1 1136.37  4673.6 1134.36    4739 1132.68  4831.3 1122.05
    4867 1120.96  4923.6 1116.31  4953.2 1111.03  4959.3 1112.03    4968 1109.76
  4988.7 1109.86  5003.6 1109.15  5004.1 1108.65  5029.9 1109.15  5033.9 1111.42
  5046.9 1113.52  5056.9 1112.12    5077 1112.21    5097 1116.64  5137.2 1120.59
    5152 1120.93  5157.3 1122.53  5227.5 1128.62    5265 1133.56  5270.1 1132.19
  5277.7 1132.28  5297.8 1134.93  5327.9 1136.04    5348 1138.59  5383.1 1139.46
#Mann= 4 ,-1 , 0
    4580     .12       0  4988.7     .05       0  5003.6     .05       0
  5029.9     .05       0
Bank Sta=5003.6,5029.9
XS Rating Curve= 0 ,0
Exp/Cntr=0.3,0.1

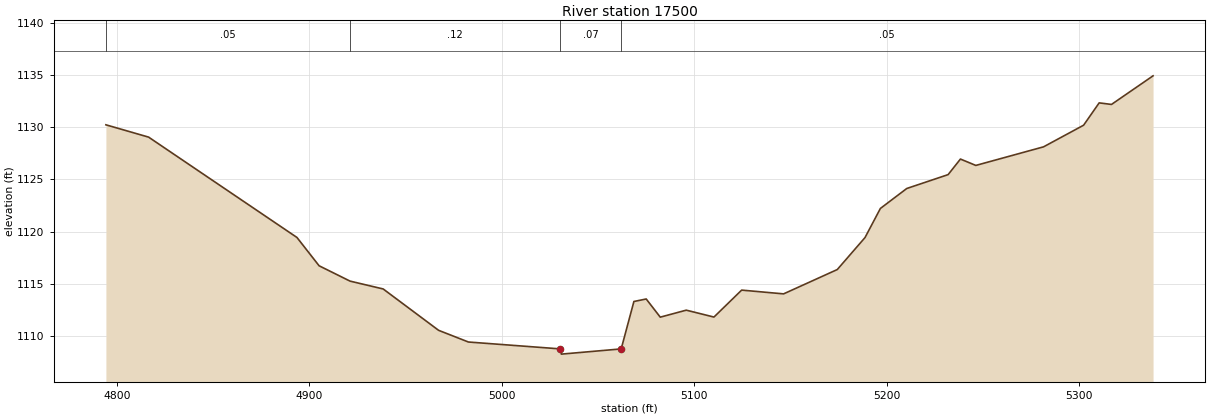
Type RM Length L Ch R = 1 ,17500   ,500,500,500
BEGIN DESCRIPTION:
SIXMILE CREEK 35.0
END DESCRIPTION:
XS GIS Cut Line= 3
      2788505.68     10224603.11      2788691.28     10224514.42
      2788955.71     10224303.09
#Sta/Elev= 30
  4794.3 1130.22  4816.5 1129.04  4893.6 1119.43  4905.1 1116.72  4921.2 1115.25
  4938.4  1114.5  4967.2 1110.54  4982.7 1109.42  5030.5 1108.76    5031 1108.26
  5062.1 1108.76  5068.7  1113.3  5075.1 1113.54  5082.4  1111.8  5095.9 1112.47
  5110.3 1111.81  5124.7 1114.39  5146.5 1114.03  5174.4 1116.36  5188.8 1119.42
  5196.8 1122.21  5210.5 1124.12    5232 1125.45  5238.4 1126.94  5246.4 1126.33
  5281.6 1128.11  5302.4 1130.18  5310.5 1132.32  5316.9 1132.17  5338.5 1134.91
#Mann= 4 ,-1 , 0
  4794.3     .05       0  4921.2     .12       0  5030.5     .07       0
  5062.1     .05       0
Bank Sta=5030.5,5062.1
XS Rating Curve= 0 ,0
Exp/Cntr=0.3,0.1