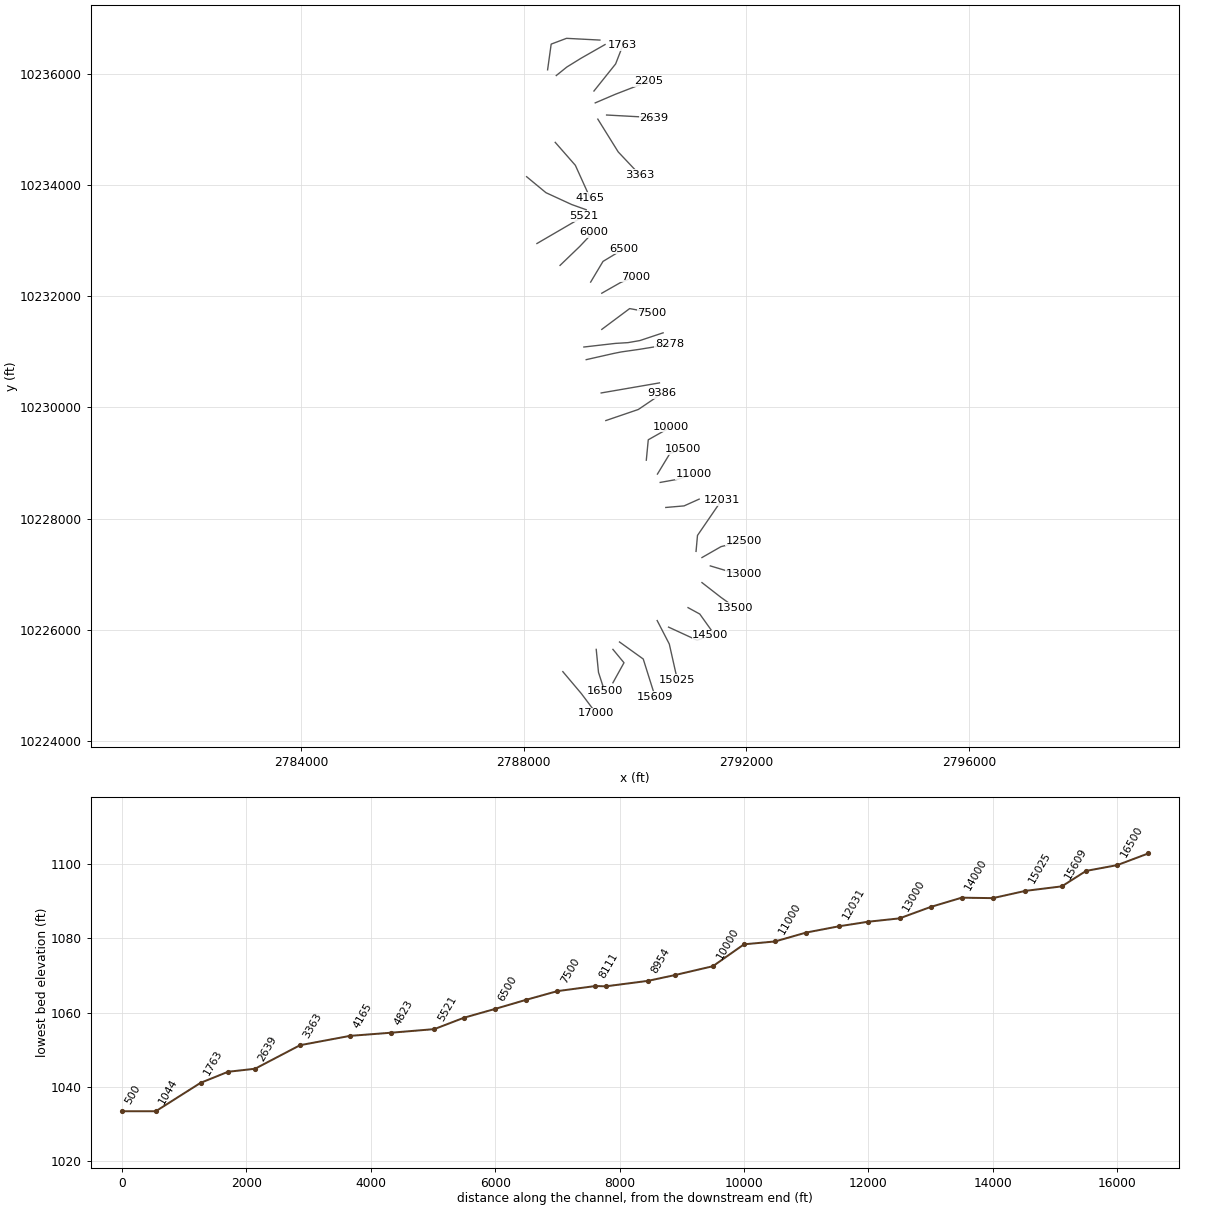
HEC-RAS study SIXMILE CREEK.prj: SIXMILE CREEK Base Level Engineering

--- SIXMILE CREEK.g01 (geometry) --- (continued)

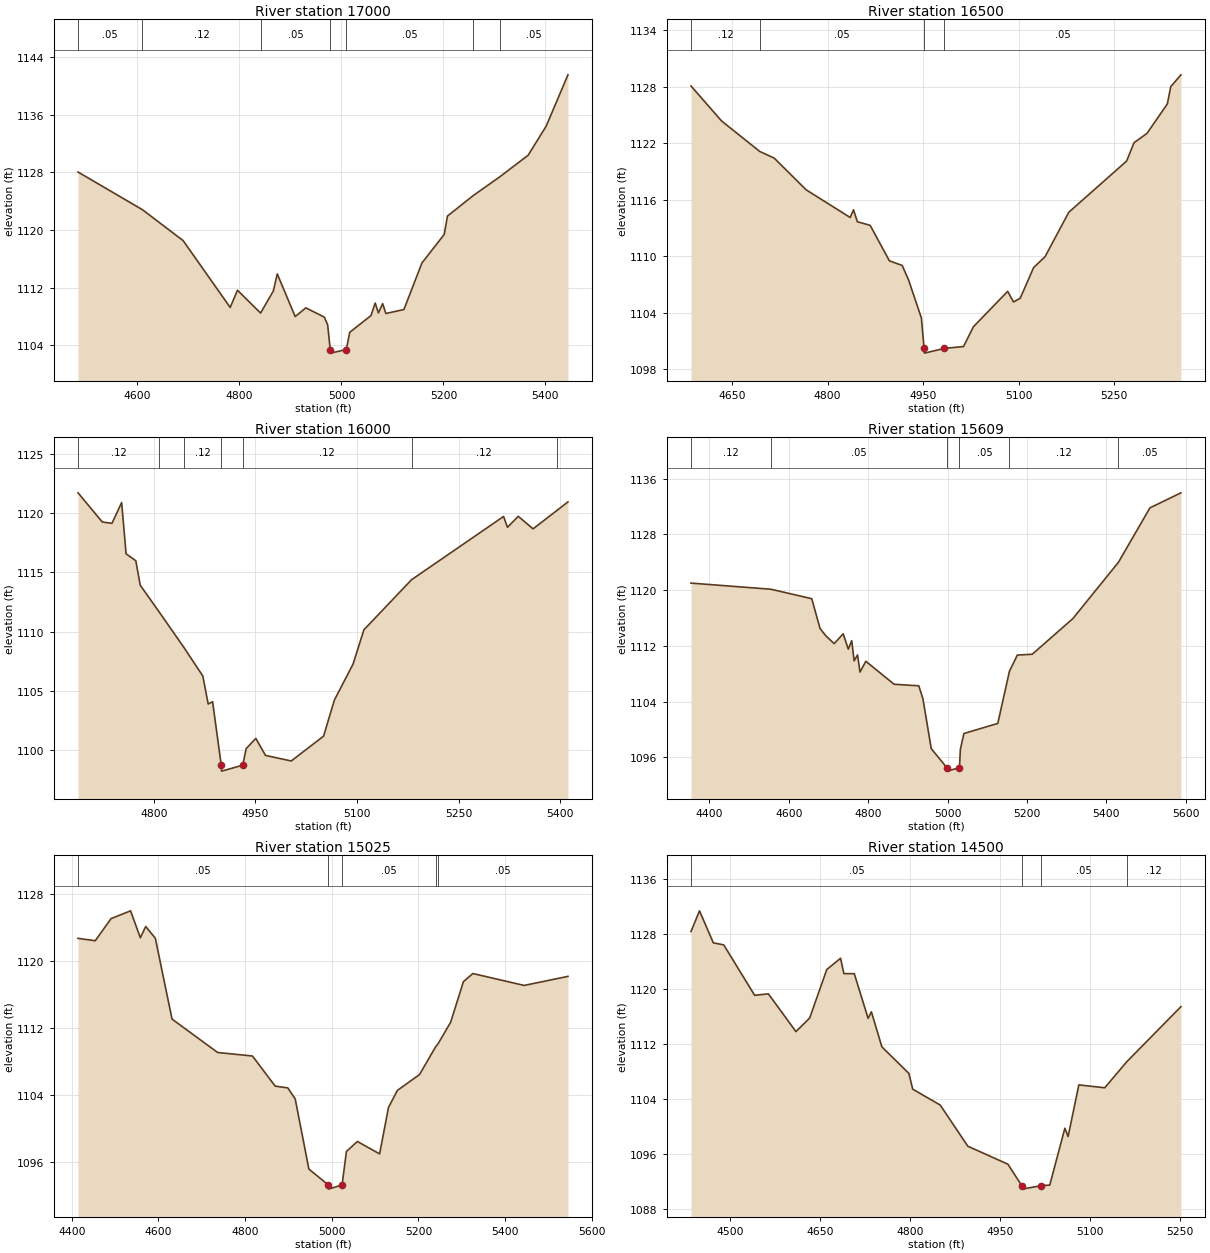
Type RM Length L Ch R = 1 ,17000   ,500,500,500
BEGIN DESCRIPTION:
SIXMILE CREEK 34.0
END DESCRIPTION:
XS GIS Cut Line= 3
      2788705.68     10225253.12      2789038.73      10224858.2
      2789305.66     10224503.15
#Sta/Elev= 30
  4483.4 1128.06  4609.8 1122.82  4689.5 1118.53  4781.8 1109.24  4796.1 1111.63
  4841.4 1108.46  4866.4 1111.53  4874.1  1113.9  4909.3 1107.97  4930.1 1109.18
  4966.4  1107.9    4973  1106.8    4978 1103.39  4978.5 1102.89  5009.6 1103.39
  5016.3 1105.79  5057.9 1108.11  5066.2 1109.85  5072.5 1108.48  5080.8 1109.77
  5087.1  1108.4  5122.5 1108.95  5157.9 1115.43  5201.6 1119.39  5207.9 1121.94
  5258.3 1124.78  5310.4 1127.39  5366.1 1130.39  5401.6 1134.45  5444.2 1141.57
#Mann= 7 ,-1 , 0
  4483.4     .05       0  4609.8     .12       0  4841.4     .05       0
    4978     .03       0  5009.6     .05       0  5258.3     .12       0
  5310.4     .05       0
Bank Sta=4978,5009.6
XS Rating Curve= 0 ,0
Exp/Cntr=0.3,0.1

Type RM Length L Ch R = 1 ,16500   ,500,500,500
BEGIN DESCRIPTION:
SIXMILE CREEK 33.0
END DESCRIPTION:
XS GIS Cut Line= 3
      2789305.69     10225653.07       2789346.5     10225240.48
      2789455.68     10224903.11
#Sta/Elev= 30
  4585.4  1128.1  4633.4 1124.38  4693.4 1121.14    4716 1120.44  4766.2 1117.07
  4835.4 1114.13  4840.5 1114.95  4846.6 1113.68  4866.7  1113.3  4896.9 1109.53
    4917 1109.04    4927  1107.5  4947.1 1103.47  4951.4 1100.23  4951.9 1099.73
  4983.1 1100.23  5013.3 1100.43  5028.8 1102.53  5082.6 1106.29  5091.8 1105.16
  5102.3 1105.56  5123.4 1108.82  5141.3 1109.97  5178.6 1114.69  5269.3 1120.12
    5281 1122.07  5301.3 1123.06  5333.3 1126.19  5338.6 1128.02  5354.6 1129.28
#Mann= 4 ,-1 , 0
  4585.4     .12       0  4693.4     .05       0  4951.4     .05       0
  4983.1     .05       0
Bank Sta=4951.4,4983.1
XS Rating Curve= 0 ,0
Exp/Cntr=0.3,0.1

Type RM Length L Ch R = 1 ,16000   ,391,391,391
BEGIN DESCRIPTION:
SIXMILE CREEK 32.0
END DESCRIPTION:
XS GIS Cut Line= 3
      2789605.71     10225653.09      2789804.74     10225412.95
       2789605.7     10225053.13
#Sta/Elev= 30
  4688.1 1121.74  4723.9 1119.27  4738.2 1119.16  4752.5 1120.92    4759 1116.58
  4773.4 1115.99  4779.9 1113.92  4807.3  1111.7  4844.4 1108.65  4872.3 1106.23
  4880.2 1103.86  4886.7 1104.06  4899.5 1098.68    4900 1098.18  4931.2 1098.68
  4936.2 1100.08  4950.5 1100.95  4964.8 1099.51  5002.8 1099.04  5050.5 1101.14
  5066.5  1104.2    5094 1107.24    5110 1110.14  5180.3 1114.38  5316.2 1119.74
  5321.9 1118.82  5337.9 1119.75  5359.7 1118.69  5395.2 1120.26  5411.2 1120.97
#Mann= 7 ,-1 , 0
  4688.1     .12       0  4807.3     .05       0  4844.4     .12       0
  4899.5     .03       0  4931.2     .12       0  5180.3     .12       0
  5395.2     .05       0
Bank Sta=4899.5,4931.2
XS Rating Curve= 0 ,0
Exp/Cntr=0.3,0.1

Type RM Length L Ch R = 1 ,15609   ,584,584,584
BEGIN DESCRIPTION:
Mapping XS 870f8ae5
END DESCRIPTION:
XS GIS Cut Line= 3
      2789724.01       10225786.      2790150.61     10225479.96
      2790363.94     10224802.89
#Sta/Elev= 30
  4353.4    1121    4555 1120.12  4657.8 1118.76  4678.7 1114.48  4693.4 1113.43
  4714.3 1112.31    4737 1113.72  4749.9 1111.52  4758.5 1112.74  4764.6 1109.84
  4773.2 1110.69  4779.4 1108.23  4794.1 1109.78  4865.3 1106.48  4927.5 1106.26
    4938 1104.39    4959 1097.24  4998.3 1094.51  4998.8 1094.01  5030.1 1094.51
  5032.4 1097.15  5041.3 1099.41  5126.7 1100.86  5156.1 1108.35    5176 1110.67
  5213.6 1110.79    5316 1115.91  5430.8 1123.99  5510.2  1131.8  5588.3 1133.96
#Mann= 6 ,-1 , 0
  4353.4     .12       0    4555     .05       0  4998.3     .05       0
  5030.1     .05       0  5156.1     .12       0  5430.8     .05       0
Bank Sta=4998.3,5030.1
XS Rating Curve= 0 ,0
Exp/Cntr=0.3,0.1

Type RM Length L Ch R = 1 ,15025   ,525,525,525
BEGIN DESCRIPTION:
Mapping XS 1f3f16b6
END DESCRIPTION:
XS GIS Cut Line= 3
      2790401.04     10226170.85      2790618.97     10225748.91
      2790762.73     10225108.95
#Sta/Elev= 30
  4414.4 1122.75  4454.2 1122.47  4490.6 1125.11  4535.7 1126.04  4558.2 1122.82
  4570.6 1124.17  4592.8 1122.77  4631.4 1113.11  4736.6 1109.12    4817  1108.7
  4869.5  1105.1  4898.7 1104.89  4915.7 1103.57  4947.2  1095.2    4992  1093.3
  4992.5  1092.8  5023.9  1093.3  5033.8 1097.29  5059.2 1098.49  5110.5 1097.01
    5131 1102.56  5151.5 1104.59  5202.7 1106.49  5239.9 1109.81    5245 1110.13
  5274.5 1112.74  5303.9 1117.58  5325.7 1118.55  5444.1 1117.13  5545.2 1118.21
#Mann= 5 ,-1 , 0
  4414.4     .05       0    4992     .03       0  5023.9     .05       0
  5239.9     .12       0    5245     .05       0
Bank Sta=4992,5023.9
XS Rating Curve= 0 ,0
Exp/Cntr=0.3,0.1

Type RM Length L Ch R = 1 ,14500   ,500,500,500
BEGIN DESCRIPTION:
SIXMILE CREEK 29.0
END DESCRIPTION:
XS GIS Cut Line= 3
      2790605.72      10226053.1      2791118.76     10225816.91
      2791355.67     10225903.11
#Sta/Elev= 30
  4435.2 1128.36  4449.4 1131.37  4472.4 1126.71  4489.8 1126.41  4541.3 1119.07
  4564.2 1119.28  4610.2 1113.78  4633.1 1115.76  4661.6 1122.82  4684.6 1124.46
  4690.1 1122.23  4707.5 1122.21  4730.5 1115.71    4736 1116.66  4753.5 1111.56
  4798.5 1107.69  4804.9  1105.4  4850.8 1103.08  4896.8 1097.09  4963.6 1094.47
  4986.8 1091.34  4987.3 1090.84  5018.7 1091.34  5033.4 1091.43  5058.6 1099.71
    5064  1098.5  5081.9 1106.02  5125.1  1105.6  5161.8 1109.39  5252.1 1117.41
#Mann= 4 ,-1 , 0
  4435.2     .05       0  4986.8     .03       0  5018.7     .05       0
  5161.8     .12       0
Bank Sta=4986.8,5018.7
XS Rating Curve= 0 ,0
Exp/Cntr=0.3,0.1

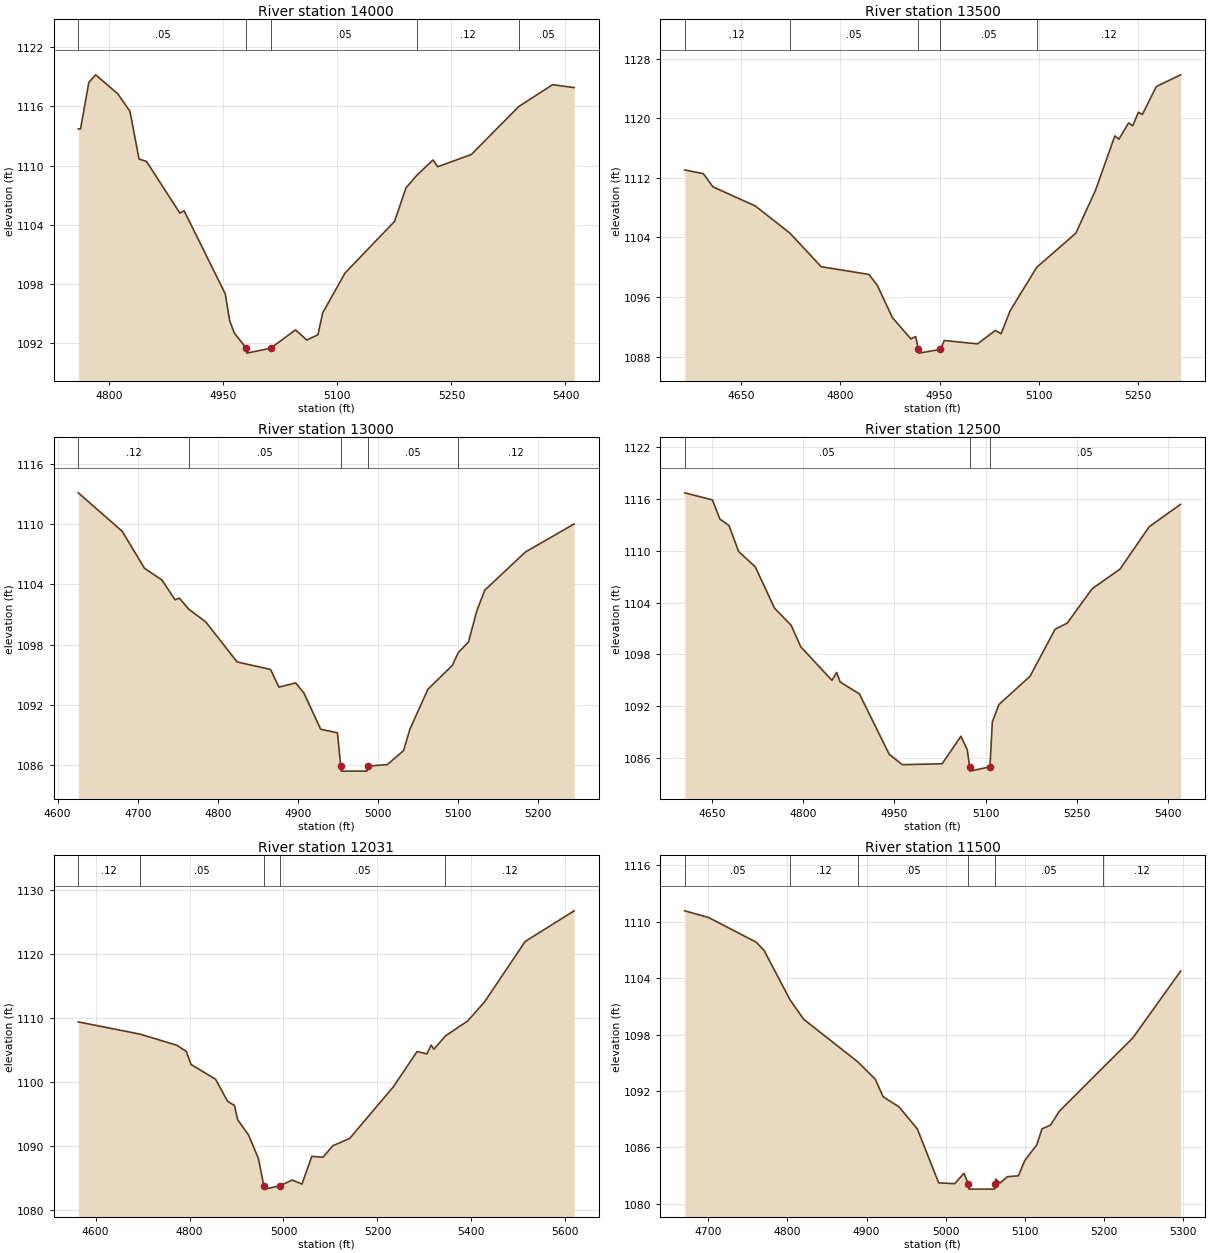
Type RM Length L Ch R = 1 ,14000   ,500,500,500
BEGIN DESCRIPTION:
SIXMILE CREEK 28.0
END DESCRIPTION:
XS GIS Cut Line= 3
      2790955.66     10226403.13      2791166.68     10226287.96
      2791405.68     10225953.11
#Sta/Elev= 30
  4759.6 1113.72  4762.5 1113.72  4773.4 1118.45  4782.4 1119.21  4811.4 1117.29
  4827.5  1115.5  4839.4 1110.67  4849.3 1110.41    4893 1105.18  4898.7 1105.41
  4952.8 1096.97  4958.5 1094.28  4964.7 1092.99  4980.5 1091.46    4981 1090.96
  5012.4 1091.46  5045.1 1093.32  5059.9 1092.29  5074.6 1092.82  5080.8 1095.05
  5110.3  1099.1  5175.4 1104.34  5190.2 1107.72  5204.3 1108.99  5225.8 1110.57
    5232 1109.88  5276.2 1111.12  5338.7    1116  5383.1 1118.21  5411.4 1117.91
#Mann= 5 ,-1 , 0
  4759.6     .05       0  4980.5     .03       0  5012.4     .05       0
  5204.3     .12       0  5338.7     .05       0
Bank Sta=4980.5,5012.4
XS Rating Curve= 0 ,0
Exp/Cntr=0.3,0.1

Type RM Length L Ch R = 1 ,13500   ,500,500,500
BEGIN DESCRIPTION:
SIXMILE CREEK 27.0
END DESCRIPTION:
XS GIS Cut Line= 3
      2791205.71     10226853.09      2791549.45     10226585.85
      2791805.67     10226403.12
#Sta/Elev= 30
  4564.6 1113.04  4592.6 1112.55  4607.1 1110.78  4671.3 1108.21  4723.6 1104.57
  4770.9 1100.06  4843.2 1099.02    4856 1097.54  4878.6 1093.24  4906.6 1090.37
  4913.9 1090.68    4918 1088.96  4918.6 1088.46  4951.4 1088.96  4957.2 1090.16
  5007.4  1089.7  5034.5 1091.51  5043.1 1091.06  5056.8 1094.15    5097 1099.98
  5156.1 1104.55  5185.7 1110.26  5215.2 1117.62  5221.3 1117.17    5236 1119.35
  5242.2 1118.97  5250.8 1120.78  5256.9  1120.5  5277.9 1124.24  5314.7 1125.81
#Mann= 5 ,-1 , 0
  4564.6     .12       0  4723.6     .05       0    4918     .05       0
  4951.4     .05       0    5097     .12       0
Bank Sta=4918,4951.4
XS Rating Curve= 0 ,0
Exp/Cntr=0.3,0.1

Type RM Length L Ch R = 1 ,13000   ,500,500,500
BEGIN DESCRIPTION:
SIXMILE CREEK 26.0
END DESCRIPTION:
XS GIS Cut Line= 3
      2791355.65     10227153.12      2791714.06     10227045.56
      2791955.66     10227003.12
#Sta/Elev= 30
  4625.8 1113.12  4680.6 1109.29  4708.5  1105.6  4730.2 1104.44  4746.7 1102.46
    4752 1102.63  4763.9 1101.52    4785 1100.26  4824.2 1096.27    4866 1095.52
  4876.4 1093.76  4897.3 1094.18  4907.7 1093.16  4928.6 1089.56  4949.5 1089.21
  4953.7 1085.89  4954.3 1085.39  4986.5 1085.39  4987.1 1085.89  5011.8 1086.04
  5032.1 1087.43  5040.1 1089.57  5062.6 1093.55    5093 1095.92  5100.6 1097.21
  5113.3 1098.26  5123.5 1101.32  5133.6 1103.42  5184.4 1107.22  5245.3 1110.02
#Mann= 5 ,-1 , 0
  4625.8     .12       0  4763.9     .05       0  4953.7     .03       0
  4987.1     .05       0  5100.6     .12       0
Bank Sta=4953.7,4987.1
XS Rating Curve= 0 ,0
Exp/Cntr=0.3,0.1

Type RM Length L Ch R = 1 ,12500   ,469,469,469
BEGIN DESCRIPTION:
SIXMILE CREEK 25.0
END DESCRIPTION:
XS GIS Cut Line= 3
      2791205.65     10227303.09      2791548.18      10227499.2
      2791955.64      10227603.1
#Sta/Elev= 30
  4605.3 1116.71  4650.7 1115.89    4663 1113.67    4678 1112.93  4693.8 1109.92
  4721.2 1108.14  4752.8 1103.36  4780.2 1101.37    4796 1098.88  4847.3    1095
    4855 1095.91  4860.8 1094.81  4892.4 1093.43  4941.4 1086.44  4962.9 1085.24
  5028.4 1085.34  5059.3 1088.53  5069.7 1086.97  5073.6 1084.99  5074.2 1084.49
    5107 1084.99  5110.9 1090.18  5121.7  1092.2  5172.9 1095.47  5214.1 1100.92
    5234 1101.62  5274.9  1105.6  5320.9 1107.88  5368.9 1112.79  5420.5 1115.38
#Mann= 3 ,-1 , 0
  4605.3     .05       0  5073.6     .05       0    5107     .05       0
Bank Sta=5073.6,5107
XS Rating Curve= 0 ,0
Exp/Cntr=0.3,0.1

Type RM Length L Ch R = 1 ,12031   ,531,531,531
BEGIN DESCRIPTION:
Mapping XS 98561f4d
END DESCRIPTION:
XS GIS Cut Line= 3
       2791099.4     10227414.24      2791125.44     10227700.72
      2791559.45     10228334.37
#Sta/Elev= 30
  4563.2 1109.36  4694.6 1107.45  4772.9 1105.72    4793 1104.76  4803.2 1102.72
  4855.3 1100.42    4881 1096.98  4895.9 1096.31  4902.2 1094.13  4925.7  1091.7
  4946.6 1088.07  4958.2 1083.77  4958.8 1083.27  4991.8 1083.77  5018.4 1084.69
  5039.4 1084.06  5060.3 1088.39  5084.1 1088.24  5105.1 1090.04  5140.9 1091.18
  5233.7 1099.21  5284.5 1104.74  5305.4 1104.36  5314.3 1105.73  5320.3  1105.1
  5344.9 1107.18  5392.1  1109.5    5428 1112.47  5514.6 1121.91  5618.9 1126.69
#Mann= 5 ,-1 , 0
  4563.2     .12       0  4694.6     .05       0  4958.2     .03       0
  4991.8     .05       0  5344.9     .12       0
Bank Sta=4958.2,4991.8
XS Rating Curve= 0 ,0
Exp/Cntr=0.3,0.1

Type RM Length L Ch R = 1 ,11500   ,500,500,500
BEGIN DESCRIPTION:
SIXMILE CREEK 23.0
END DESCRIPTION:
XS GIS Cut Line= 3
      2790555.71     10228203.11       2790884.4     10228231.33
      2791155.71     10228353.12
#Sta/Elev= 30
  4670.1 1111.17  4700.2 1110.46  4760.4 1107.84  4770.4 1106.96  4803.2 1101.71
  4820.6 1099.63  4889.1  1095.1    4911 1093.27    4921  1091.4  4941.1 1090.32
  4964.3 1087.97  4991.3 1082.24  5011.7 1082.15  5023.3 1083.26    5029 1082.07
  5029.6 1081.57  5062.1 1081.57  5062.8 1082.07  5063.5 1082.63    5069 1082.22
  5078.1 1082.89  5092.2 1082.99  5100.1 1084.59  5115.4 1086.28    5122 1087.98
  5132.9 1088.39    5144 1089.86  5199.3 1094.51  5236.7 1097.63  5297.4 1104.76
#Mann= 6 ,-1 , 0
  4670.1     .05       0  4803.2     .12       0  4889.1     .05       0
    5029     .03       0  5062.8     .05       0  5199.3     .12       0
Bank Sta=5029,5062.8
XS Rating Curve= 0 ,0
Exp/Cntr=0.3,0.1

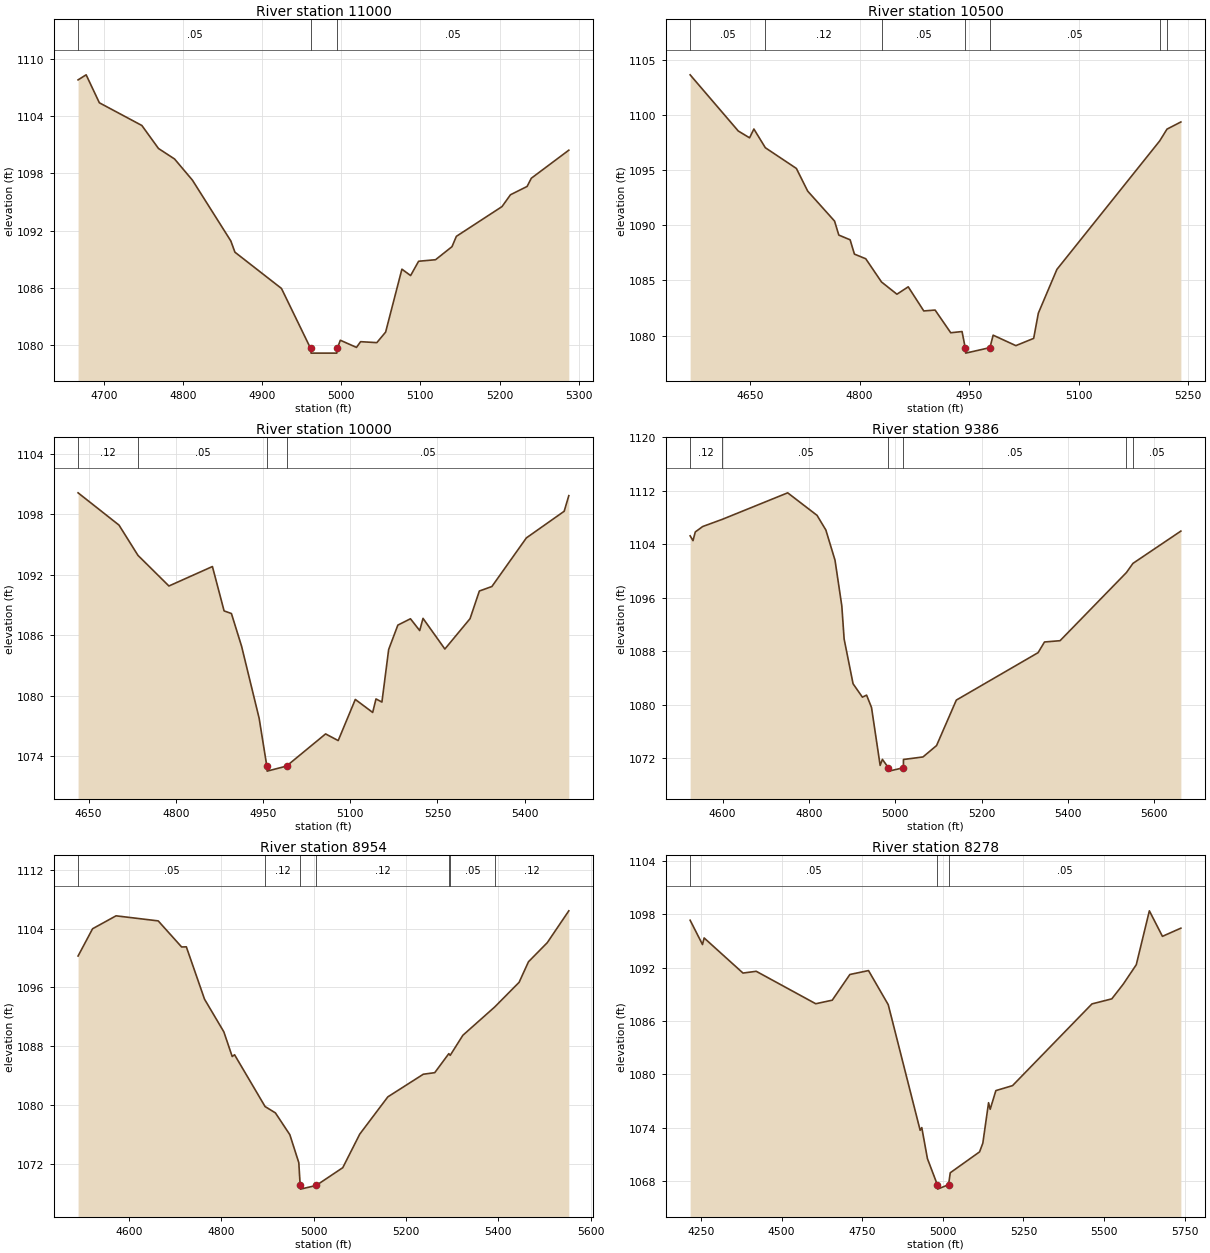
Type RM Length L Ch R = 1 ,11000   ,500,500,500
BEGIN DESCRIPTION:
SIXMILE CREEK 22.0
END DESCRIPTION:
XS GIS Cut Line= 3
      2790455.69     10228653.11      2790783.06     10228711.84
      2791055.69     10228803.11
#Sta/Elev= 30
  4667.4 1107.81  4677.6 1108.34  4694.3 1105.41    4748 1103.03    4769 1100.62
  4789.3 1099.52  4811.9  1097.3  4860.4 1090.93  4865.6 1089.75  4924.4 1085.95
  4961.2 1079.67  4961.8 1079.17  4994.3 1079.17    4995 1079.67  4998.8 1080.52
  5019.2 1079.77  5024.4 1080.37  5044.9 1080.27    5056 1081.37  5076.6 1087.97
  5087.6  1087.3  5097.7  1088.8  5119.1 1088.96  5139.9 1090.33  5145.4 1091.41
  5203.1 1094.53  5213.8 1095.77  5234.8 1096.64  5240.1  1097.5  5287.5 1100.44
#Mann= 3 ,-1 , 0
  4667.4     .05       0  4961.2     .03       0    4995     .05       0
Bank Sta=4961.2,4995
XS Rating Curve= 0 ,0
Exp/Cntr=0.3,0.1

Type RM Length L Ch R = 1 ,10500   ,500,500,500
BEGIN DESCRIPTION:
SIXMILE CREEK 21.0
END DESCRIPTION:
XS GIS Cut Line= 3
      2790405.69     10228803.12       2790629.5     10229172.74
      2790855.65      10229253.1
#Sta/Elev= 30
  4567.9 1103.67  4633.8 1098.57  4649.3 1097.95  4655.2 1098.75  4670.9 1097.05
  4713.4 1095.17  4728.9 1093.11  4765.7 1090.39  4771.5 1089.12    4787 1088.69
  4792.9 1087.39  4808.4 1086.97    4830 1084.86  4851.1 1083.75  4866.6 1084.42
  4887.9 1082.23  4903.4 1082.31  4924.8 1080.25  4940.3 1080.36  4944.6  1078.9
  4945.3  1078.4  4978.5  1078.9  4982.9 1080.03    5014 1079.08  5038.4 1079.74
  5044.8 1082.03  5070.2    1086    5211 1097.67    5221 1098.74    5240 1099.39
#Mann= 7 ,-1 , 0
  4567.9     .05       0  4670.9     .12       0    4830     .05       0
  4944.6     .03       0  4978.5     .05       0    5211     .12       0
    5221     .05       0
Bank Sta=4944.6,4978.5
XS Rating Curve= 0 ,0
Exp/Cntr=0.3,0.1

Type RM Length L Ch R = 1 ,10000   ,614,614,614
BEGIN DESCRIPTION:
SIXMILE CREEK 20.0
END DESCRIPTION:
XS GIS Cut Line= 3
      2790205.68     10229053.07       2790240.9     10229419.48
      2790655.73     10229653.14
#Sta/Elev= 30
  4631.9  1100.1  4702.3  1096.9  4734.9  1093.9  4788.2 1090.86    4863 1092.79
  4883.1 1088.39  4895.7 1088.13  4913.2 1084.88  4943.4 1077.74  4956.6    1073
  4957.2  1072.5  4990.5    1073  5057.7 1076.19  5079.4 1075.53  5108.8 1079.61
  5138.7 1078.32  5144.4 1079.66  5154.6 1079.35  5166.2 1084.56    5182 1086.98
  5203.7 1087.61  5219.6 1086.44  5225.3 1087.65  5262.9 1084.61  5306.2 1087.62
  5322.2 1090.36  5343.8 1090.81  5403.1 1095.63  5468.1 1098.27  5476.1 1099.82
#Mann= 4 ,-1 , 0
  4631.9     .12       0  4734.9     .05       0  4956.6     .05       0
  4990.5     .05       0
Bank Sta=4956.6,4990.5
XS Rating Curve= 0 ,0
Exp/Cntr=0.3,0.1

Type RM Length L Ch R = 1 ,9386    ,432,432,432
BEGIN DESCRIPTION:
Mapping XS 3726ef44
END DESCRIPTION:
XS GIS Cut Line= 3
      2789478.19     10229764.69      2790062.51      10229964.1
      2790492.19     10230255.18
#Sta/Elev= 30
    4525 1105.28  4531.6 1104.56  4536.9 1105.86    4554 1106.67  4599.6 1107.75
  4750.9 1111.71  4818.9 1108.34  4839.3 1106.15  4860.5 1101.63  4876.2 1094.82
  4881.6 1089.85  4902.3 1083.16  4923.9 1081.16  4933.6 1081.46    4945 1079.62
    4965 1070.96  4970.2 1071.86  4984.2  1070.6  4984.9  1070.1  5018.9  1070.6
    5019 1071.84  5064.2 1072.22  5095.6 1073.92  5141.4 1080.72  5330.7 1087.81
  5345.6 1089.41  5381.6  1089.6  5535.3 1099.79  5550.4 1101.16  5661.4 1105.99
#Mann= 6 ,-1 , 0
    4525     .12       0  4599.6     .05       0  4984.2     .05       0
  5018.9     .05       0  5535.3     .12       0  5550.4     .05       0
Bank Sta=4984.2,5018.9
XS Rating Curve= 0 ,0
Exp/Cntr=0.3,0.1

Type RM Length L Ch R = 1 ,8954    ,676,676,676
BEGIN DESCRIPTION:
Mapping XS 0bb0826b
END DESCRIPTION:
XS GIS Cut Line= 2
      2789394.71     10230260.87      2790441.74     10230441.55
#Sta/Elev= 30
  4489.9 1100.28  4521.3 1103.99  4572.1 1105.75  4663.4 1105.06  4714.1 1101.51
  4724.3 1101.53  4763.7  1094.4  4805.5 1089.96  4823.6  1086.6  4828.7 1086.84
  4894.8 1079.79  4917.1 1078.93  4948.4 1075.96  4967.8 1072.15  4970.8 1069.05
  4971.5 1068.55  5005.5 1069.05    5063 1071.47  5099.8 1076.04  5160.6 1081.11
  5237.4 1084.19  5262.1  1084.4  5292.6 1086.99  5295.6 1086.76    5323 1089.49
  5392.1 1093.35  5444.8  1096.7  5465.1  1099.5  5505.7 1102.09  5552.4 1106.43
#Mann= 7 ,-1 , 0
  4489.9     .05       0  4894.8     .12       0  4970.8     .03       0
  5005.5     .12       0  5292.6     .12       0  5295.6     .05       0
  5392.1     .12       0
Bank Sta=4970.8,5005.5
XS Rating Curve= 0 ,0
Exp/Cntr=0.3,0.1

Type RM Length L Ch R = 1 ,8278    ,167,167,167
BEGIN DESCRIPTION:
Mapping XS 1da0f500
END DESCRIPTION:
XS GIS Cut Line= 5
      2789125.84     10230859.08      2789617.34     10230970.37
      2789756.46     10230998.19      2790081.06     10231044.56
      2790622.16     10231132.43
#Sta/Elev= 30
  4216.3 1097.32  4254.6 1094.59  4259.7 1095.33  4380.2 1091.38  4421.2 1091.58
  4605.8 1087.93    4657 1088.33  4711.7 1091.22  4769.5 1091.66  4830.7 1087.82
  4929.6  1073.7  4934.7    1074  4952.2 1070.51  4982.9 1067.58  4983.7 1067.08
  5017.7 1067.58    5023 1068.92  5113.9 1071.27    5124 1072.25  5141.8  1076.8
  5146.8 1076.06  5164.4 1078.16  5216.1 1078.72  5462.4 1087.91    5524 1088.48
  5559.4 1090.13  5599.9 1092.32  5640.5 1098.38    5681 1095.51  5738.2 1096.43
#Mann= 3 ,-1 , 0
  4216.3     .05       0  4982.9     .03       0  5017.7     .05       0
Bank Sta=4982.9,5017.7
XS Rating Curve= 0 ,0
Exp/Cntr=0.3,0.1

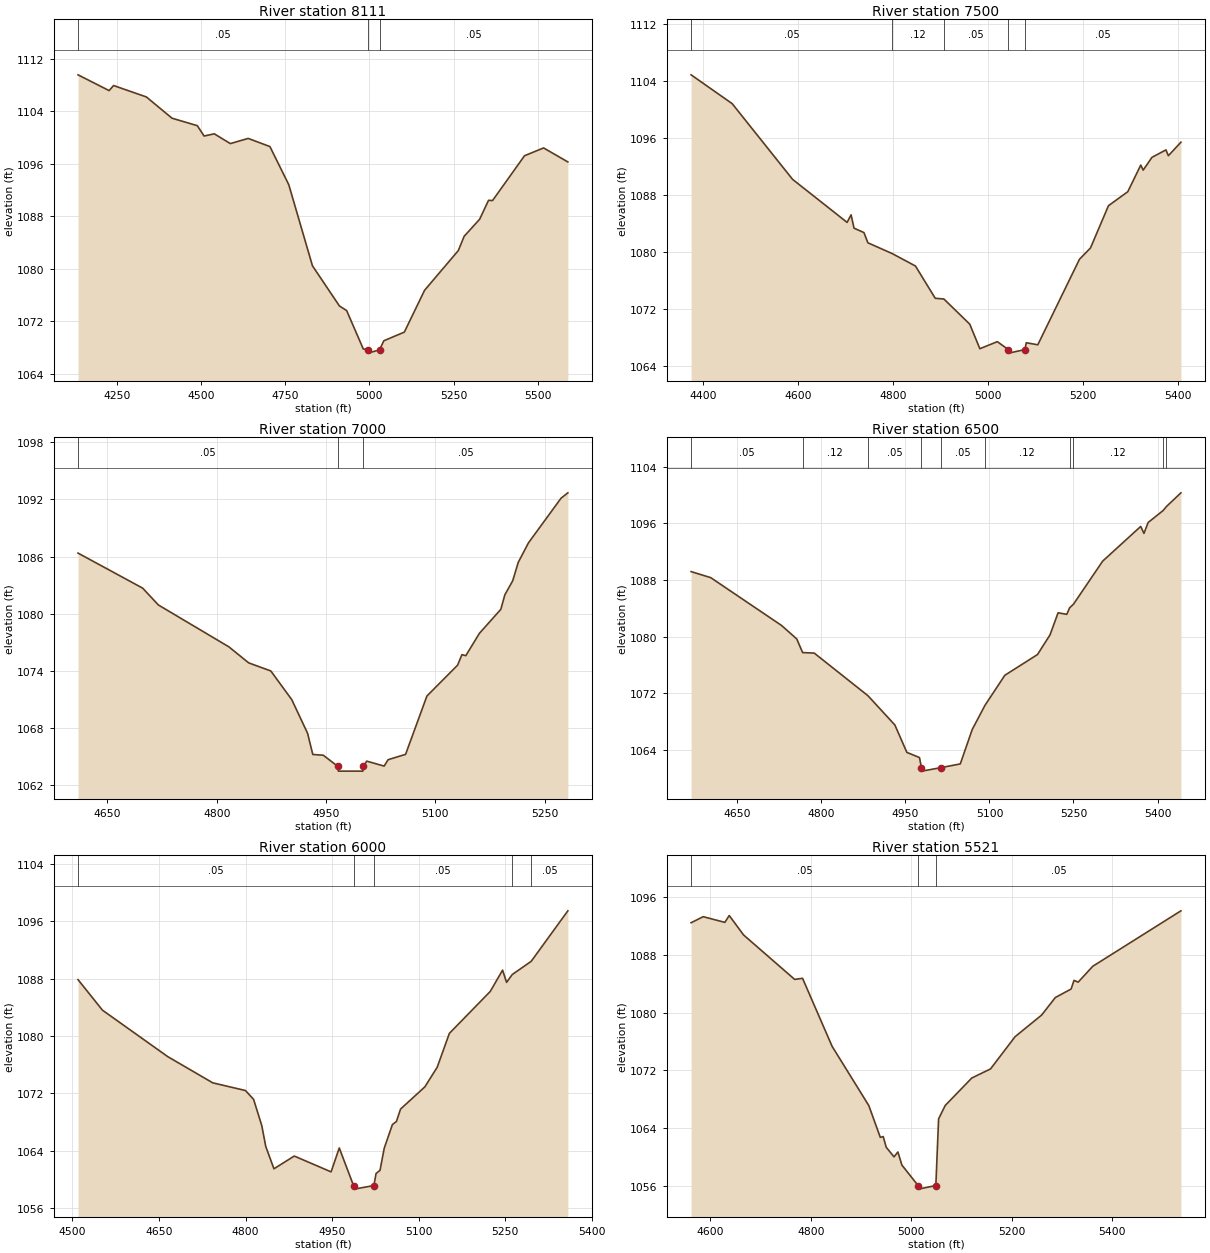
Type RM Length L Ch R = 1 ,8111    ,611,611,611
BEGIN DESCRIPTION:
Mapping XS 27b8713c
END DESCRIPTION:
XS GIS Cut Line= 5
      2789084.06      10231086.3       2789649.8     10231151.22
      2789877.02     10231165.13      2790090.33     10231202.23
      2790507.65     10231341.33
#Sta/Elev= 30
  4135.3 1109.53  4227.5 1107.13  4240.8  1107.9  4338.2 1106.16  4414.1 1102.93
  4489.2 1101.79  4509.4 1100.21  4539.6 1100.55  4587.3 1099.06  4640.2 1099.85
  4704.7 1098.61  4760.7  1092.8  4830.9 1080.46    4911 1074.34  4932.4 1073.64
  4981.8 1067.79  4995.3 1067.66    4996 1067.16  5030.1 1067.66  5042.7 1069.04
  5103.6 1070.36  5163.7 1076.73  5263.8 1082.78    5281 1084.94  5327.1 1087.55
  5353.4 1090.42  5365.4 1090.39  5460.2 1097.21  5516.8  1098.4  5588.8 1096.27
#Mann= 3 ,-1 , 0
  4135.3     .05       0  4995.3     .03       0  5030.1     .05       0
Bank Sta=4995.3,5030.1
XS Rating Curve= 0 ,0
Exp/Cntr=0.3,0.1

Type RM Length L Ch R = 1 ,7500    ,500,500,500
BEGIN DESCRIPTION:
SIXMILE CREEK 15.0
END DESCRIPTION:
XS GIS Cut Line= 3
      2789405.72     10231403.14      2789906.52      10231776.9
      2790305.66     10231703.12
#Sta/Elev= 30
  4375.1 1104.87  4461.6 1100.82  4588.7 1090.19  4703.4 1084.15  4711.8 1085.21
    4718 1083.34  4738.8 1082.72  4747.2 1081.28    4798 1079.78  4847.3 1078.02
  4888.9 1073.49  4907.1 1073.39  4961.5 1069.86  4982.8 1066.41  5019.5  1067.4
  5042.7 1066.29  5043.5 1065.79  5077.6 1066.29  5080.5 1067.25  5104.7 1066.96
  5192.4 1078.97  5215.6 1080.56  5253.4 1086.49  5294.1 1088.46  5321.4  1092.2
  5326.5 1091.49  5344.9 1093.28  5374.4 1094.33  5379.5 1093.51  5405.9 1095.41
#Mann= 5 ,-1 , 0
  4375.1     .05       0    4798     .12       0  4907.1     .05       0
  5042.7     .05       0  5077.6     .05       0
Bank Sta=5042.7,5077.6
XS Rating Curve= 0 ,0
Exp/Cntr=0.3,0.1

Type RM Length L Ch R = 1 ,7000    ,500,500,500
BEGIN DESCRIPTION:
SIXMILE CREEK 14.0
END DESCRIPTION:
XS GIS Cut Line= 3
      2789405.66      10232053.1        2789745.     10232246.12
       2790005.7     10232353.12
#Sta/Elev= 30
  4609.6 1086.36  4698.3 1082.68  4719.9 1080.91  4816.5 1076.52  4843.8 1074.83
  4874.2 1073.98  4902.9 1070.97  4924.6 1067.44  4931.8 1065.21  4946.2 1065.13
  4966.1 1063.96  4966.9 1063.46  5000.5 1063.46  5001.3 1063.96  5005.7 1064.51
  5029.7 1063.99  5035.1 1064.66  5059.1 1065.22  5088.4 1071.35  5130.5 1074.59
  5136.4 1075.69  5141.8 1075.59  5160.4 1077.93  5189.8 1080.45  5195.3 1081.97
  5206.1 1083.45  5213.7 1085.38  5227.7 1087.43  5272.5 1092.13  5281.8 1092.69
#Mann= 3 ,-1 , 0
  4609.6     .05       0  4966.1     .03       0  5001.3     .05       0
Bank Sta=4966.1,5001.3
XS Rating Curve= 0 ,0
Exp/Cntr=0.3,0.1

Type RM Length L Ch R = 1 ,6500    ,500,500,500
BEGIN DESCRIPTION:
SIXMILE CREEK 13.0
END DESCRIPTION:
XS GIS Cut Line= 3
       2789205.7     10232253.14       2789427.6     10232624.61
      2789805.71     10232853.13
#Sta/Elev= 30
  4567.3 1089.19  4602.3 1088.34  4728.8 1081.58    4756 1079.67  4766.4 1077.75
  4787.1 1077.68    4883 1071.66  4931.1 1067.52  4952.5 1063.65    4975 1062.92
  4978.6  1061.5  4979.4    1061  5013.8  1061.5  5047.9 1062.02  5069.2 1066.88
    5092  1070.3  5127.4 1074.54  5185.7 1077.47  5208.1 1080.25  5222.5 1083.37
    5238 1083.15    5243 1084.06    5250 1084.59  5302.1 1090.67    5370 1095.57
  5375.8 1094.59  5383.3 1096.13  5409.9 1097.81  5415.9 1098.38  5441.8 1100.32
#Mann= 10 ,-1 , 0
  4567.3     .05       0  4766.4     .12       0    4883     .05       0
  4978.6     .03       0  5013.8     .05       0    5092     .12       0
    5243     .05       0    5250     .12       0  5409.9     .05       0
  5415.9     .12       0
Bank Sta=4978.6,5013.8
XS Rating Curve= 0 ,0
Exp/Cntr=0.3,0.1

Type RM Length L Ch R = 1 ,6000    ,479,479,479
BEGIN DESCRIPTION:
SIXMILE CREEK 12.0
END DESCRIPTION:
XS GIS Cut Line= 3
      2788655.67      10232553.1       2789009.1     10232892.92
      2789255.71     10233153.14
#Sta/Elev= 30
  4509.7 1087.88    4552 1083.62  4665.2 1077.13  4743.2 1073.47  4799.8  1072.4
  4813.9 1071.17  4828.1 1067.51    4835 1064.59  4849.2 1061.47  4884.4 1063.25
  4948.2 1061.04  4962.4 1064.38  4987.1 1059.13  4987.9 1058.63  5022.4 1059.13
  5026.1  1060.8    5033 1061.26  5040.3 1064.34  5054.5 1067.65  5061.4 1068.07
  5068.6 1069.81  5110.7 1072.91  5132.1 1075.65  5153.2 1080.38    5224 1086.23
  5245.4 1089.21  5252.3  1087.5  5262.2  1088.6    5295 1090.44  5358.5 1097.49
#Mann= 5 ,-1 , 0
  4509.7     .05       0  4987.1     .03       0  5022.4     .05       0
  5262.2     .12       0    5295     .05       0
Bank Sta=4987.1,5022.4
XS Rating Curve= 0 ,0
Exp/Cntr=0.3,0.1

Type RM Length L Ch R = 1 ,5521    ,698,698,698
BEGIN DESCRIPTION:
Mapping XS ce4e43ef
END DESCRIPTION:
XS GIS Cut Line= 2
      2788240.12     10232945.81      2789082.38     10233436.36
#Sta/Elev= 30
  4561.8 1092.45  4585.9 1093.29  4628.9  1092.5  4637.7 1093.45  4666.2 1090.76
  4767.9  1084.6  4783.6 1084.75  4842.4 1075.33  4915.4 1067.13  4938.3 1062.72
  4944.1 1062.83  4950.1 1061.35  4965.6 1060.02  4973.3  1060.7  4981.3 1058.88
  5013.5 1056.05  5014.3 1055.55  5048.8 1056.05  5054.3 1065.28  5067.4 1067.13
  5120.3 1070.94  5157.6  1072.2  5206.4 1076.66  5259.3 1079.66  5286.6 1082.09
    5318 1083.27  5323.8 1084.47    5332 1084.22  5361.1 1086.42  5536.5  1094.1
#Mann= 3 ,-1 , 0
  4561.8     .05       0  5013.5     .05       0  5048.8     .05       0
Bank Sta=5013.5,5048.8
XS Rating Curve= 0 ,0
Exp/Cntr=0.3,0.1

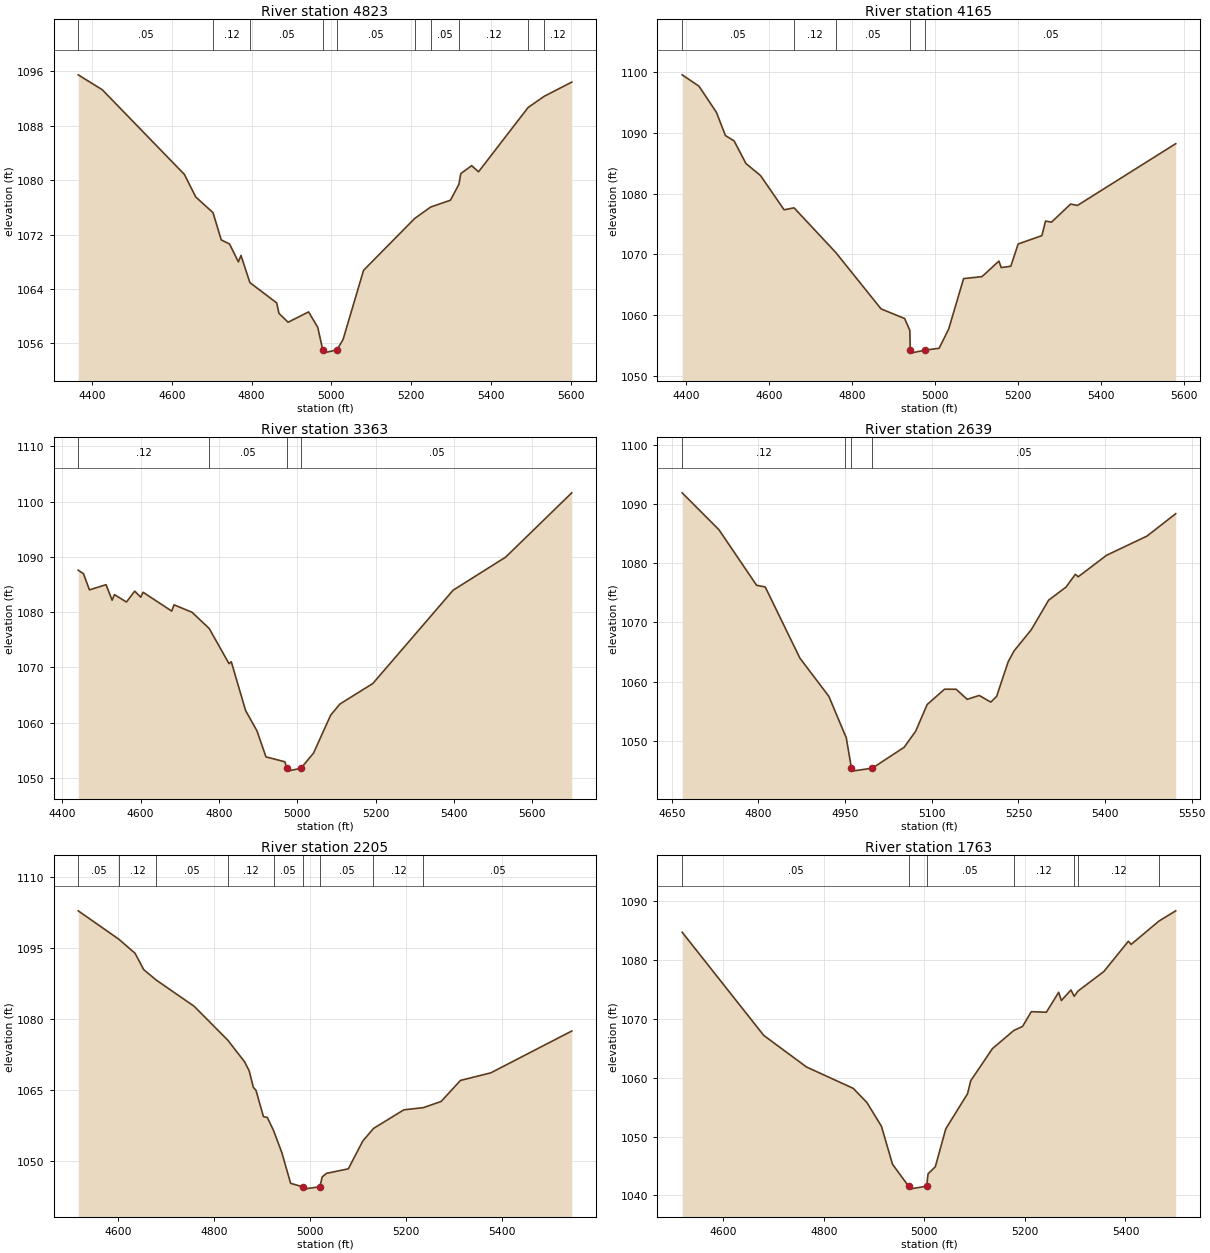
Type RM Length L Ch R = 1 ,4823    ,658,658,658
BEGIN DESCRIPTION:
Mapping XS 607c3412
END DESCRIPTION:
XS GIS Cut Line= 4
      2788054.62     10234146.82       2788402.4     10233859.32
      2788866.12     10233646.02       2789125.8     10233553.27
#Sta/Elev= 30
  4365.5 1095.48  4425.8 1093.29  4631.6 1080.85  4660.2 1077.53  4703.5 1075.22
  4724.1 1071.22  4744.9 1070.62  4767.1 1067.99  4773.6 1068.94    4796 1064.94
  4863.2 1061.96  4868.7 1060.43  4891.7 1059.12  4943.1 1060.64  4966.1 1058.36
  4978.5 1055.08  4979.4 1054.58  5014.4 1055.08  5029.5 1056.58  5080.9 1066.75
  5209.1 1074.37  5249.2 1076.05  5298.7 1077.05  5320.1 1079.41  5324.6 1080.96
  5351.9 1082.13  5369.2 1081.23  5493.3 1090.67  5533.4 1092.31  5602.9 1094.41
#Mann= 10 ,-1 , 0
  4365.5     .05       0  4703.5     .12       0    4796     .05       0
  4978.5     .05       0  5014.4     .05       0  5209.1     .12       0
  5249.2     .05       0  5320.1     .12       0  5493.3     .05       0
  5533.4     .12       0
Bank Sta=4978.5,5014.4
XS Rating Curve= 0 ,0
Exp/Cntr=0.3,0.1

Type RM Length L Ch R = 1 ,4165    ,802,802,802
BEGIN DESCRIPTION:
Mapping XS b970104c
END DESCRIPTION:
XS GIS Cut Line= 3
      2788569.31     10234763.61      2788931.04     10234350.87
      2789195.02     10233767.32
#Sta/Elev= 30
  4390.9  1099.6  4431.4 1097.73  4473.4 1093.43  4495.2 1089.59  4516.1 1088.71
  4544.6 1084.98  4579.7    1083  4636.6 1077.35  4660.5 1077.68  4761.3  1070.3
  4870.2 1061.02    4927 1059.43  4939.5 1057.48  4940.5 1054.23  4941.3 1053.73
  4976.4 1054.23  5010.1 1054.53  5033.2 1057.71    5069 1066.01  5113.5 1066.34
  5154.2  1068.9  5159.7 1067.83  5182.8 1068.05  5200.5 1071.72  5257.7 1073.09
  5266.5  1075.5  5280.8 1075.31    5327  1078.3  5343.4 1078.07  5580.2 1088.25
#Mann= 5 ,-1 , 0
  4390.9     .05       0  4660.5     .12       0  4761.3     .05       0
  4940.5     .05       0  4976.4     .05       0
Bank Sta=4940.5,4976.4
XS Rating Curve= 0 ,0
Exp/Cntr=0.3,0.1

Type RM Length L Ch R = 1 ,3363    ,724,724,724
BEGIN DESCRIPTION:
Mapping XS bcd506c5
END DESCRIPTION:
XS GIS Cut Line= 3
      2789334.49     10235180.89      2789700.81       10234592.
      2790090.31     10234179.31
#Sta/Elev= 30
  4440.4 1087.58  4453.8 1086.95  4469.1 1084.02  4511.6 1084.96    4527 1082.15
  4532.9 1083.16  4563.6 1081.82  4584.8 1083.79  4600.2 1082.69  4606.1 1083.59
  4679.3 1080.18  4685.2 1081.31  4731.2 1079.97  4775.1 1077.03  4825.7 1070.66
  4831.5 1071.02  4868.1 1062.18  4897.1 1058.51  4920.1  1053.8  4968.5 1052.91
  4973.3 1051.72  4974.1 1051.22  5009.3 1051.72  5041.7 1054.49  5085.5 1061.36
    5109 1063.36  5193.2 1067.08  5398.3 1083.96  5532.6 1089.95  5701.4 1101.58
#Mann= 4 ,-1 , 0
  4440.4     .12       0  4775.1     .05       0  4973.3     .03       0
  5009.3     .05       0
Bank Sta=4973.3,5009.3
XS Rating Curve= 0 ,0
Exp/Cntr=0.3,0.1

Type RM Length L Ch R = 1 ,2639    ,434,434,434
BEGIN DESCRIPTION:
Mapping XS 95a701f9
END DESCRIPTION:
XS GIS Cut Line= 2
       2789492.1     10235255.12      2790345.34     10235208.74
#Sta/Elev= 30
  4667.9 1091.91  4731.6 1085.67  4796.8 1076.28  4811.7    1076  4871.8 1063.96
  4921.9 1057.51  4949.6 1051.06  4951.9 1050.56    4961 1045.37  4961.9 1044.87
  4997.1 1045.37  5052.1 1048.89  5072.1  1051.6  5092.1 1056.13  5122.2 1058.72
  5142.2 1058.71  5161.4 1057.01  5182.2 1057.66  5202.3 1056.54  5212.3  1057.5
  5232.3 1063.34  5242.3 1065.16  5272.4 1068.78  5302.4 1073.77  5332.5 1075.98
  5348.6 1078.13  5353.6 1077.72  5402.6 1081.35  5472.7  1084.6  5522.4 1088.38
#Mann= 4 ,-1 , 0
  4667.9     .12       0  4949.6     .05       0    4961     .03       0
  4997.1     .05       0
Bank Sta=4961,4997.1
XS Rating Curve= 0 ,0
Exp/Cntr=0.3,0.1

Type RM Length L Ch R = 1 ,2205    ,442,442,442
BEGIN DESCRIPTION:
Mapping XS f6b667e3
END DESCRIPTION:
XS GIS Cut Line= 3
       2789288.1     10235473.06      2789645.16     10235626.09
      2790242.03     10235857.43
#Sta/Elev= 30
    4517 1102.85  4601.7 1096.85  4635.4 1093.89  4653.6 1090.42  4679.3 1088.25
  4758.7 1082.68  4828.7 1075.53  4863.9 1070.93  4873.4 1069.03    4882 1065.55
  4887.5 1064.93    4903 1059.39  4911.2 1059.18    4924 1056.47  4941.2 1051.83
  4959.7 1045.29  4984.5 1044.56  4985.4 1044.06  5020.6 1044.56  5025.6 1046.66
  5034.7  1047.4    5080 1048.35    5110 1054.21  5132.3 1056.87  5195.6 1060.81
  5236.5 1061.28  5273.4 1062.58  5313.6 1067.02    5377 1068.63  5545.6 1077.46
#Mann= 9 ,-1 , 0
    4517     .05       0  4601.7     .12       0  4679.3     .05       0
  4828.7     .12       0    4924     .05       0  4984.5     .03       0
  5020.6     .05       0  5132.3     .12       0  5236.5     .05       0
Bank Sta=4984.5,5020.6
XS Rating Curve= 0 ,0
Exp/Cntr=0.3,0.1

Type RM Length L Ch R = 1 ,1763    ,719,719,719
BEGIN DESCRIPTION:
Mapping XS 98d58079
END DESCRIPTION:
XS GIS Cut Line= 3
      2789264.93     10235686.39      2789654.44     10236173.27
      2789784.26     10236507.11
#Sta/Elev= 30
  4518.2 1084.74  4680.5  1067.2  4765.6 1061.83  4858.5  1058.2  4885.7 1055.79
  4914.5 1051.77  4936.6  1045.3  4968.5 1041.57  4969.3 1041.07  5004.6 1041.57
  5007.3 1043.67  5021.7 1044.87  5042.6 1051.33  5085.8 1057.28  5092.2  1059.5
  5135.4 1064.96    5178 1068.05  5195.2 1068.72  5212.7 1071.24  5242.6 1071.14
  5267.1 1074.53  5272.5 1073.13  5291.6 1074.93    5298 1073.84  5305.5 1074.74
  5356.8 1078.05  5405.8 1083.21  5411.2 1082.67  5466.6 1086.64  5499.9 1088.38
#Mann= 7 ,-1 , 0
  4518.2     .05       0  4968.5     .03       0  5004.6     .05       0
    5178     .12       0    5298     .05       0  5305.5     .12       0
  5466.6     .05       0
Bank Sta=4968.5,5004.6
XS Rating Curve= 0 ,0
Exp/Cntr=0.3,0.1

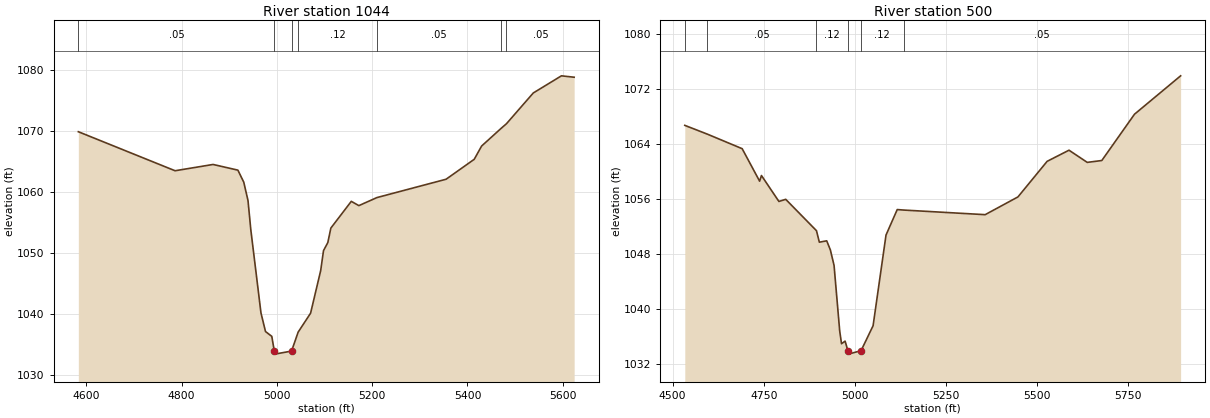
Type RM Length L Ch R = 1 ,1044    ,544,544,544
BEGIN DESCRIPTION:
Mapping XS 56647d8d
END DESCRIPTION:
XS GIS Cut Line= 4
       2788587.9     10235964.61      2788778.01     10236117.63
      2789033.06     10236275.29      2789464.35     10236521.08
#Sta/Elev= 30
  4583.5 1069.84  4786.5 1063.45  4866.2 1064.48  4918.3 1063.55  4930.6 1061.58
  4939.5 1058.57  4945.4 1053.79  4966.7 1040.18  4976.2 1037.13  4989.4 1036.34
  4994.7 1033.93  4995.6 1033.43  5030.9 1033.93  5044.7 1037.03  5070.8 1040.13
    5092 1047.11  5097.9 1050.37    5107  1051.7  5113.3 1054.06  5156.2 1058.44
  5172.1 1057.74    5210 1059.06  5355.1 1062.06  5414.1 1065.32  5429.7  1067.5
  5470.3 1070.37  5481.8 1071.15    5538 1076.18  5597.1 1078.99  5623.8 1078.76
#Mann= 7 ,-1 , 0
  4583.5     .05       0  4994.7     .05       0  5030.9     .05       0
  5044.7     .12       0    5210     .05       0  5470.3     .12       0
  5481.8     .05       0
Bank Sta=4994.7,5030.9
XS Rating Curve= 0 ,0
Exp/Cntr=0.3,0.1

Type RM Length L Ch R = 1 ,500     ,0,0,0
BEGIN DESCRIPTION:
SIXMILE CREEK 1.0
END DESCRIPTION:
XS GIS Cut Line= 4
      2788432.03     10236067.03      2788496.32     10236529.28
       2788772.3     10236632.97      2789371.87     10236601.78
#Sta/Elev= 30
  4533.3 1066.68    4595 1065.41  4690.9 1063.29  4738.8 1058.57  4743.9 1059.39
  4791.8 1055.62  4810.5 1055.93    4895 1051.37  4902.9  1049.7  4923.1  1049.9
  4933.2 1048.57  4943.3 1046.32  4958.8 1036.79  4963.8 1034.94  4973.6 1035.32
  4981.3 1033.93  4982.2 1033.43  5017.5 1033.93  5050.5 1037.56    5086 1050.74
  5116.8 1054.44  5134.4 1054.37  5358.3  1053.7  5448.4 1056.28  5528.5 1061.45
  5588.6 1063.07  5638.7  1061.3  5678.7 1061.57  5768.5  1068.3  5895.2 1073.88
#Mann= 6 ,-1 , 0
  4533.3     .05       0    4595     .05       0    4895     .12       0
  4981.3     .07       0  5017.5     .12       0  5134.4     .05       0
Bank Sta=4981.3,5017.5
XS Rating Curve= 0 ,0
Exp/Cntr=0.3,0.1

Chan Stop Cuts=-1
Use User Specified Reach Order=0
Composite Channel Slope=5