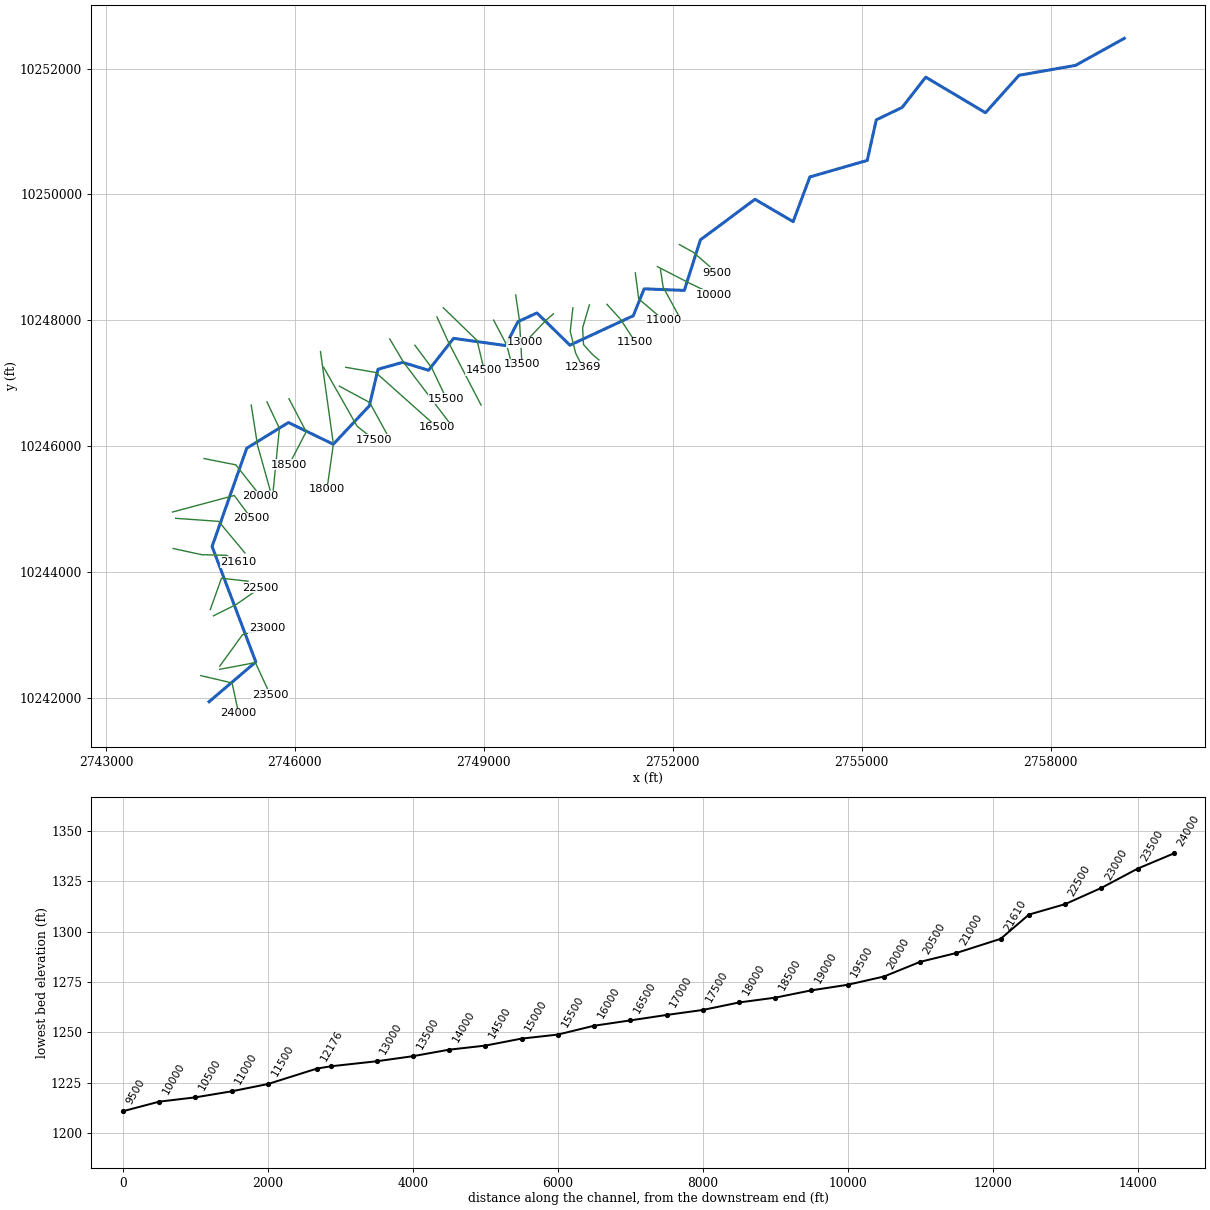
--- SOUTH WILLOW CREEK.prj (project) ---

Proj Title=SOUTH WILLOW CREEK Base Level Engineering
Current Plan=p01
Default Exp/Contr=0.3,0.1
English Units
Geom File=g01
Flow File=f01
Plan File=p01
BEGIN DESCRIPTION:
SOUTH WILLOW CREEK
END DESCRIPTION:

--- SOUTH WILLOW CREEK.p01 (plan) ---

Plan Title=Multiple Run
Short Identifier=Multiple
Geom File=g01
Flow File=f01
Subcritical Flow
K Sum by GR= 0
Std Step Tol= 0.01
Critical Tol= 0.01
Num of Std Step Trials= 20
Max Error Tol= 0.3
Flow Tol Ratio= 0.001
Split Flow NTrial= 30
Split Flow Tol= 0.02
Split Flow Ratio= 0.02
Log Output Level= 0
Friction Slope Method= 1
Unsteady Friction Slope Method= 2
Unsteady Bridges Friction Slope Method= 1
Parabolic Critical Depth
Global Vel Dist=  1 , 1 , 1
Global Log Level= 0
CheckData=True
Encroach Param= -1, 0, 0, 0
BEGIN DESCRIPTION:
Multiple Run
END DESCRIPTION:

--- SOUTH WILLOW CREEK.f01 (steady flow) ---

Flow Title=Multiple
Number of Profiles=7
Profile Names=10-year,25-year,50-year,1pct_min,100-year,1pct_plu,500-year
River Rch & RM= SOUTH WILLOW CRE,Reach-1,24000
     376     598     759     445     995    2225    1347
River Rch & RM= SOUTH WILLOW CRE,Reach-1,17500
     651    1078    1341     949    1787    3365    2408
River Rch & RM= SOUTH WILLOW CRE,Reach-1,12369
     810    1358    1787    1061    2407    5460    3246
River Rch & RM= SOUTH WILLOW CRE,Reach-1,10500
    1175    2031    2610    1777    3561    7134    4809
River Rch & RM= SOUTH WILLOW CRE,Reach-1,2500
    1337    2333    3076    2101    4226    8499    5719
Boundary for River Rch & Prof#=SOUTH WILLOW CRE,Reach-1,1
Up Type=0
Dn Type=3
Dn Slope=0.005
Boundary for River Rch & Prof#=SOUTH WILLOW CRE,Reach-1,2
Up Type=0
Dn Type=3
Dn Slope=0.005
Boundary for River Rch & Prof#=SOUTH WILLOW CRE,Reach-1,3
Up Type=0
Dn Type=3
Dn Slope=0.005
Boundary for River Rch & Prof#=SOUTH WILLOW CRE,Reach-1,4
Up Type=0
Dn Type=3
Dn Slope=0.005
Boundary for River Rch & Prof#=SOUTH WILLOW CRE,Reach-1,5
Up Type=0
Dn Type=3
Dn Slope=0.005
Boundary for River Rch & Prof#=SOUTH WILLOW CRE,Reach-1,6
Up Type=0
Dn Type=3
Dn Slope=0.005
Boundary for River Rch & Prof#=SOUTH WILLOW CRE,Reach-1,7
Up Type=0
Dn Type=3
Dn Slope=0.005

--- SOUTH WILLOW CREEK.g01 (geometry) ---

Geom Title=Existing Conditions

River Reach=SOUTH WILLOW CRE,Reach-1
Reach XY= 30
      2744637.25     10241939.00      2745378.75     10242571.00
      2744684.00     10244405.00      2745234.50     10245967.00
      2745897.25     10246375.00      2746609.50     10246030.00
      2747181.75     10246641.00      2747319.25     10247222.00
      2747709.75     10247331.00      2748122.25     10247206.00
      2748519.25     10247713.00      2749345.00     10247599.00
      2749542.00     10247978.00      2749843.50     10248117.00
      2750367.00     10247605.00      2751373.00     10248072.00
      2751546.25     10248500.00      2752183.50     10248475.00
      2752439.25     10249278.00      2753305.75     10249923.00
      2753912.25     10249568.00      2754177.50     10250278.00
      2755089.00     10250541.00      2755232.50     10251186.00
      2755642.25     10251382.00      2756017.75     10251864.00
      2756966.75     10251299.00      2757500.25     10251894.00
      2758397.00     10252051.00      2759171.75     10252481.00

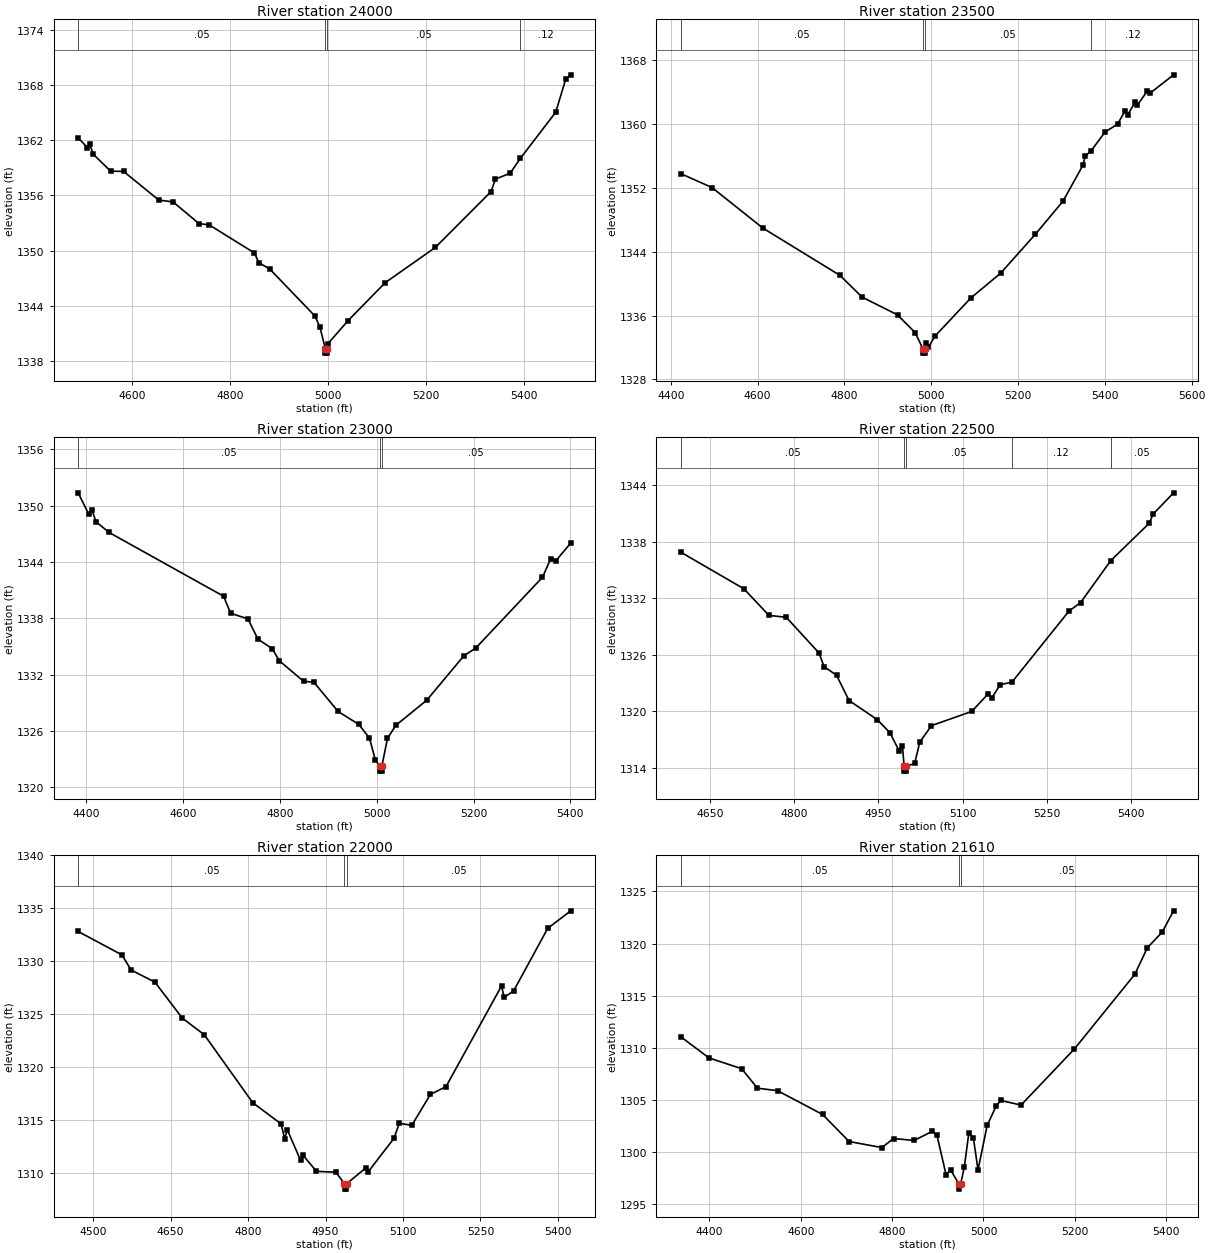
Type RM Length L Ch R = 1,24000,500,500,500
BEGIN DESCRIPTION:
SOUTH WILLOW CREEK 48.0
END DESCRIPTION:
XS GIS Cut Line= 3
      2744505.66     10242353.12      2745002.07     10242236.57
      2745105.68     10241753.14
#Sta/Elev= 30
  4490.1 1362.25  4508.8 1361.19  4513.9 1361.52  4520.9 1360.46  4556.3 1358.62
  4582.6 1358.60  4654.5 1355.48  4683.6 1355.28  4736.6 1352.92  4757.2 1352.79
  4849.6 1349.73  4858.4 1348.68  4880.5 1348.00  4972.9 1342.88  4983.2 1341.65
  4993.9 1339.35  4994.2 1338.85  4997.7 1338.85  4997.9 1339.35  4999.3 1339.87
  5040.2 1342.37  5116.0 1346.50  5218.3 1350.33  5331.7 1356.39  5341.0 1357.76
  5370.9 1358.40  5391.8 1360.02  5463.8 1365.03  5484.2 1368.62  5494.4 1369.09
#Mann=4,-1,0
  4490.1    0.05       0  4993.9    0.05       0  4997.9    0.05       0
  5391.8    0.12       0
Bank Sta=4993.9,4997.9
Exp/Cntr=0.3,0.1

Type RM Length L Ch R = 1,23500,500,500,500
BEGIN DESCRIPTION:
SOUTH WILLOW CREEK 47.0
END DESCRIPTION:
XS GIS Cut Line= 3
      2744805.71     10242453.12      2745372.07     10242560.25
      2745605.70     10242053.07
#Sta/Elev= 30
  4423.6 1353.78  4494.8 1352.06  4611.9 1346.98  4790.0 1341.03  4840.8 1338.31
  4922.3 1336.09  4963.0 1333.86  4981.3 1331.79  4981.6 1331.29  4985.1 1331.29
  4985.3 1331.79  4988.5 1332.52  4993.6 1332.02  5007.9 1333.38  5091.4 1338.21
  5160.2 1341.33  5240.1 1346.21  5303.5 1350.34  5349.2 1354.82  5354.9 1355.99
  5368.8 1356.70  5400.9 1359.04  5429.3 1360.00  5446.8 1361.70  5452.3 1361.12
  5469.7 1362.79  5475.2 1362.41  5498.2 1364.19  5503.7 1363.87  5558.4 1366.19
#Mann=4,-1,0
  4423.6    0.05       0  4981.3    0.03       0  4985.3    0.05       0
  5368.8    0.12       0
Bank Sta=4981.3,4985.3
Exp/Cntr=0.3,0.1

Type RM Length L Ch R = 1,23000,500,500,500
BEGIN DESCRIPTION:
SOUTH WILLOW CREEK 46.0
END DESCRIPTION:
XS GIS Cut Line= 3
      2744805.66     10242503.08      2745167.46     10243002.99
      2745555.66     10243103.10
#Sta/Elev= 30
  4382.9 1351.38  4405.0 1349.08  4411.2 1349.57  4419.7 1348.30  4446.7 1347.16
  4683.4 1340.36  4698.1 1338.54  4733.7 1337.95  4754.5 1335.78  4783.9 1334.78
  4798.6 1333.48  4848.9 1331.29  4869.8 1331.21  4920.1 1328.08  4963.1 1326.69
  4985.0 1325.23  4997.0 1322.92  5006.5 1322.22  5006.7 1321.72  5010.2 1321.72
  5010.5 1322.22  5022.2 1325.22  5039.5 1326.60  5103.6 1329.29  5179.8 1334.00
  5204.7 1334.84  5342.5 1342.38  5359.6 1344.37  5369.9 1344.12  5400.9 1346.03
#Mann=3,-1,0
  4382.9    0.05       0  5006.5    0.05       0  5010.5    0.05       0
Bank Sta=5006.5,5010.5
Exp/Cntr=0.3,0.1

Type RM Length L Ch R = 1,22500,500,500,500
BEGIN DESCRIPTION:
SOUTH WILLOW CREEK 45.0
END DESCRIPTION:
XS GIS Cut Line= 3
      2744705.69     10243303.12      2745064.77     10243482.51
      2745455.66     10243753.09
#Sta/Elev= 30
  4598.6 1336.90  4710.4 1333.03  4755.1 1330.20  4785.9 1330.00  4844.5 1326.19
  4853.0 1324.77  4875.4 1323.84  4897.7 1321.16  4948.1 1319.12  4970.4 1317.74
  4987.2 1315.77  4992.8 1316.33  4995.7 1314.16  4996.0 1313.66  4999.5 1313.66
  4999.7 1314.16  5014.6 1314.49  5023.4 1316.72  5044.3 1318.49  5116.0 1320.00
  5145.7 1321.89  5151.8 1321.43  5166.6 1322.83  5187.8 1323.12  5288.9 1330.64
  5309.9 1331.57  5363.4 1336.01  5432.2 1340.00  5438.9 1340.96  5475.4 1343.22
#Mann=5,-1,0
  4598.6    0.05       0  4995.7    0.03       0  4999.7    0.05       0
  5187.8    0.12       0  5363.4    0.05       0
Bank Sta=4995.7,4999.7
Exp/Cntr=0.3,0.1

Type RM Length L Ch R = 1,22000,390,390,390
BEGIN DESCRIPTION:
SOUTH WILLOW CREEK 44.0
END DESCRIPTION:
XS GIS Cut Line= 3
      2744655.70     10243403.15      2744833.58     10243901.34
      2745255.64     10243853.12
#Sta/Elev= 30
  4471.0 1332.81  4555.9 1330.59  4573.4 1329.17  4619.6 1328.02  4672.7 1324.62
  4715.2 1323.05  4809.2 1316.62  4863.8 1314.63  4870.8 1313.23  4876.1 1314.06
  4901.6 1311.19  4906.9 1311.64  4932.4 1310.14  4970.0 1310.06  4986.7 1308.96
  4986.9 1308.46  4990.4 1308.46  4990.7 1308.96  5027.9 1310.46  5032.9 1310.12
  5082.6 1313.26  5092.7 1314.67  5117.2 1314.50  5153.1 1317.41  5183.3 1318.15
  5290.8 1327.66  5295.9 1326.58  5314.1 1327.18  5380.2 1333.10  5424.8 1334.76
#Mann=3,-1,0
  4471.0    0.05       0  4986.7    0.05       0  4990.7    0.05       0
Bank Sta=4986.7,4990.7
Exp/Cntr=0.3,0.1

Type RM Length L Ch R = 1,21610,610,610,610
BEGIN DESCRIPTION:
Mapping XS 96b32f79
END DESCRIPTION:
XS GIS Cut Line= 4
      2744065.94     10244373.29      2744520.78     10244274.82
      2744909.94     10244265.44      2745106.37     10244157.87
#Sta/Elev= 30
  4337.8 1311.03  4398.9 1309.02  4470.5 1307.98  4505.2 1306.11  4549.3 1305.87
  4647.7 1303.59  4705.9 1300.99  4777.5 1300.41  4803.1 1301.28  4848.1 1301.09
  4888.1 1301.97  4898.1 1301.61  4918.1 1297.82  4928.1 1298.26  4946.1 1296.92
  4946.4 1296.42  4950.1 1296.92  4958.1 1298.54  4968.1 1301.84  4978.1 1301.31
  4988.1 1298.26  5008.1 1302.53  5028.1 1304.42  5038.1 1304.93  5082.4 1304.49
  5199.0 1309.87  5331.4 1317.04  5358.9 1319.59  5391.1 1321.08  5416.4 1323.14
#Mann=3,-1,0
  4337.8    0.05       0  4946.1    0.03       0  4950.1    0.05       0
Bank Sta=4946.1,4950.1
Exp/Cntr=0.3,0.1

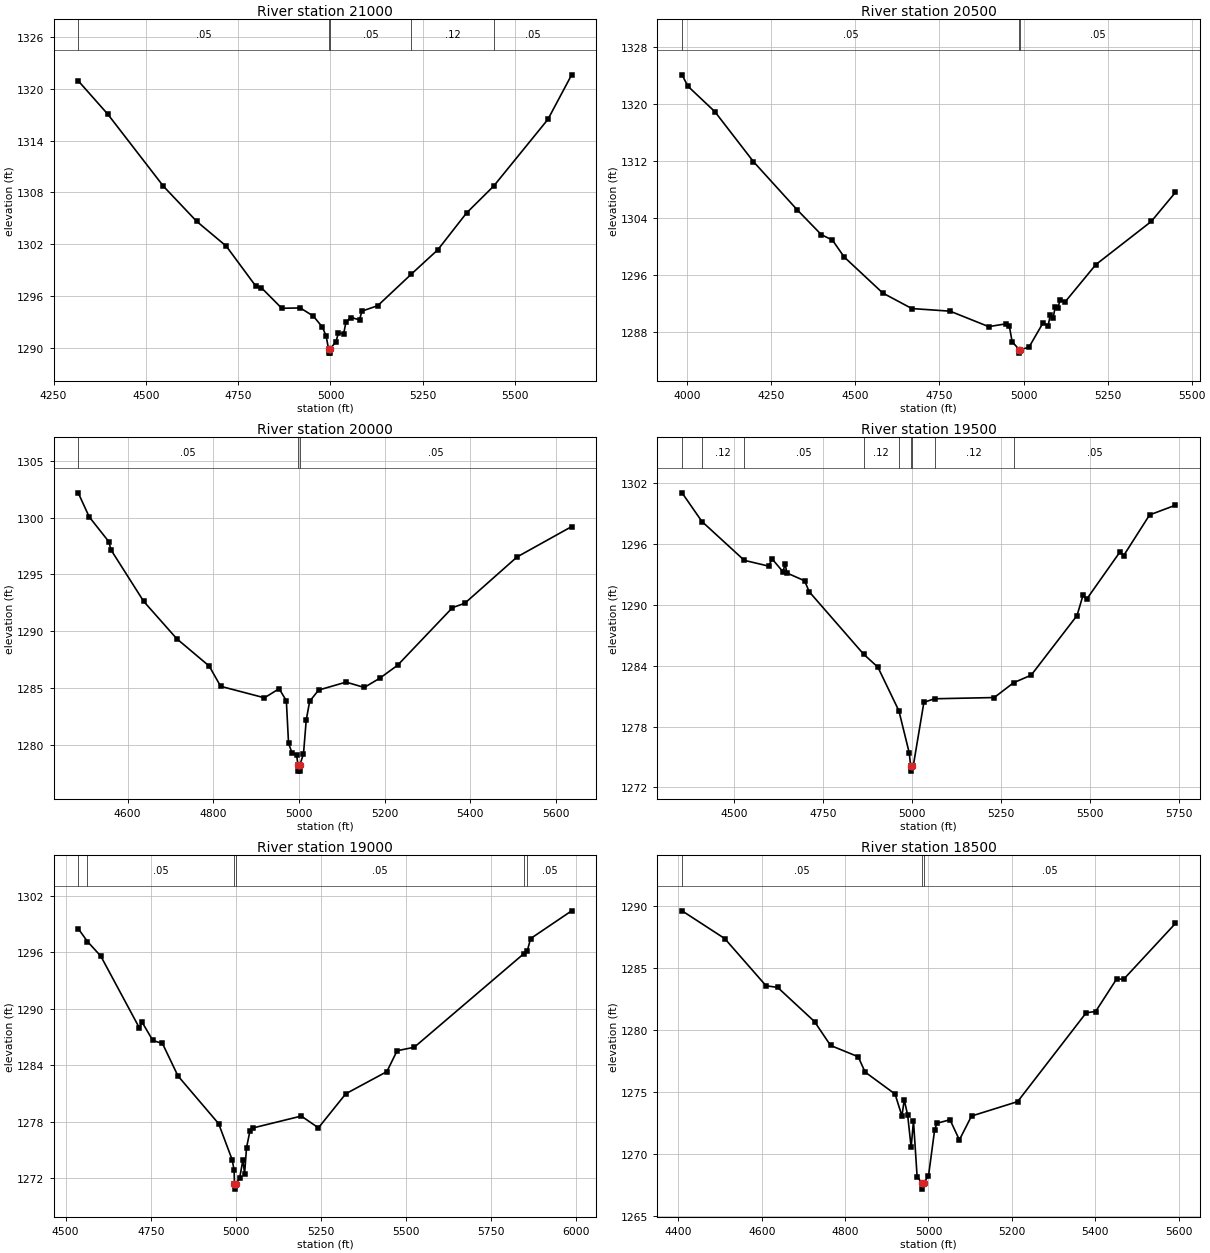
Type RM Length L Ch R = 1,21000,500,500,500
BEGIN DESCRIPTION:
SOUTH WILLOW CREEK 42.0
END DESCRIPTION:
XS GIS Cut Line= 3
      2744105.65     10244853.11      2744787.25     10244804.84
      2745205.67     10244303.13
#Sta/Elev= 30
  4316.7 1320.91  4396.9 1317.04  4547.3 1308.72  4637.5 1304.65  4717.7 1301.78
  4797.9 1297.14  4812.6 1296.98  4868.1 1294.59  4918.2 1294.63  4953.5 1293.69
  4978.4 1292.40  4988.4 1291.35  4994.7 1289.90  4995.0 1289.40  4998.5 1289.40
  4998.7 1289.90  5014.9 1290.69  5021.4 1291.75  5035.7 1291.63  5042.2 1293.04
  5056.5 1293.52  5078.7 1293.25  5085.2 1294.26  5128.1 1294.89  5218.5 1298.52
  5290.8 1301.36  5368.9 1305.63  5442.0 1308.72  5588.9 1316.44  5653.3 1321.60
#Mann=5,-1,0
  4316.7    0.05       0  4994.7    0.03       0  4998.7    0.05       0
  5218.5    0.12       0  5442.0    0.05       0
Bank Sta=4994.7,4998.7
Exp/Cntr=0.3,0.1

Type RM Length L Ch R = 1,20500,500,500,500
BEGIN DESCRIPTION:
SOUTH WILLOW CREEK 41.0
END DESCRIPTION:
XS GIS Cut Line= 3
      2744055.67     10244953.11      2745036.43     10245216.06
      2745305.67     10244853.13
#Sta/Elev= 30
  3984.6 1324.07  4002.0 1322.47  4082.1 1318.90  4196.9 1311.88  4326.3 1305.15
  4398.7 1301.63  4431.8 1300.86  4466.7 1298.49  4581.5 1293.43  4667.9 1291.25
  4781.8 1290.88  4896.5 1288.71  4947.5 1289.10  4957.8 1288.79  4966.1 1286.61
  4986.9 1285.49  4987.1 1284.99  4990.9 1285.49  5016.1 1285.81  5058.6 1289.28
  5073.2 1288.83  5079.4 1290.28  5087.8 1289.87  5094.1 1291.43  5102.5 1291.29
  5108.7 1292.50  5123.3 1292.16  5215.3 1297.43  5379.9 1303.48  5451.9 1307.57
#Mann=3,-1,0
  3984.6    0.05       0  4986.9    0.03       0  4990.9    0.05       0
Bank Sta=4986.9,4990.9
Exp/Cntr=0.3,0.1

Type RM Length L Ch R = 1,20000,500,500,500
BEGIN DESCRIPTION:
SOUTH WILLOW CREEK 40.0
END DESCRIPTION:
XS GIS Cut Line= 3
      2744555.71     10245803.11      2745061.13     10245702.70
      2745455.68     10245203.12
#Sta/Elev= 30
  4484.7 1302.18  4510.3 1300.07  4556.0 1297.89  4561.4 1297.15  4637.6 1292.63
  4714.9 1289.34  4790.5 1286.94  4817.2 1285.16  4919.5 1284.15  4953.7 1284.95
  4970.6 1283.89  4975.7 1280.15  4984.3 1279.26  4994.4 1279.16  4997.8 1278.20
  4998.0 1277.70  5001.5 1277.70  5001.8 1278.20  5010.6 1279.22  5017.0 1282.19
  5025.0 1283.84  5045.9 1284.83  5110.0 1285.53  5152.4 1285.06  5188.6 1285.87
  5230.2 1287.01  5358.4 1292.08  5387.3 1292.47  5509.2 1296.54  5636.6 1299.21
#Mann=3,-1,0
  4484.7    0.05       0  4997.8    0.03       0  5001.8    0.05       0
Bank Sta=4997.8,5001.8
Exp/Cntr=0.3,0.1

Type RM Length L Ch R = 1,19500,500,500,500
BEGIN DESCRIPTION:
SOUTH WILLOW CREEK 39.0
END DESCRIPTION:
XS GIS Cut Line= 3
      2745305.69     10246653.09      2745405.74     10246015.80
      2745605.68     10245303.11
#Sta/Elev= 30
  4354.9 1301.06  4410.7 1298.23  4529.6 1294.40  4597.8 1293.83  4607.9 1294.53
  4638.3 1293.27  4644.2 1294.07  4649.3 1293.15  4699.0 1292.38  4711.9 1291.30
  4864.9 1285.13  4904.7 1283.86  4963.7 1279.55  4992.6 1275.42  4996.8 1274.10
  4997.1 1273.60  5000.8 1274.10  5004.0 1274.10  5033.9 1280.39  5063.7 1280.74
  5231.3 1280.86  5285.6 1282.32  5335.1 1283.07  5463.8 1288.95  5480.5 1290.94
  5490.9 1290.57  5584.4 1295.23  5594.8 1294.87  5667.5 1298.88  5740.2 1299.84
#Mann=9,-1,0
  4354.9    0.05       0  4410.7    0.12       0  4529.6    0.05       0
  4864.9    0.12       0  4963.7    0.05       0  4996.8    0.05       0
  5000.8    0.05       0  5063.7    0.12       0  5285.6    0.05       0
Bank Sta=4996.8,5000.8
Exp/Cntr=0.3,0.1

Type RM Length L Ch R = 1,19000,500,500,500
BEGIN DESCRIPTION:
SOUTH WILLOW CREEK 38.0
END DESCRIPTION:
XS GIS Cut Line= 3
      2745555.70     10246703.07      2745753.16     10246284.40
      2745655.69     10245303.13
#Sta/Elev= 30
  4537.1 1298.51  4564.3 1297.14  4603.4 1295.59  4716.2 1288.00  4725.0 1288.55
  4756.2 1286.63  4784.5 1286.31  4830.1 1282.86  4949.5 1277.79  4989.5 1273.93
  4995.0 1272.82  4995.9 1271.34  4996.2 1270.84  4999.9 1271.34  5011.3 1272.04
  5020.7 1273.93  5025.7 1272.49  5031.4 1275.24  5041.5 1277.04  5051.5 1277.35
  5192.2 1278.60  5242.5 1277.35  5322.9 1280.97  5443.5 1283.32  5473.6 1285.54
  5523.9 1285.91  5845.8 1295.85  5855.9 1296.15  5865.5 1297.45  5986.1 1300.40
#Mann=6,-1,0
  4537.1    0.12       0  4564.3    0.05       0  4995.9    0.05       0
  4999.9    0.05       0  5845.8    0.12       0  5855.9    0.05       0
Bank Sta=4995.9,4999.9
Exp/Cntr=0.3,0.1

Type RM Length L Ch R = 1,18500,500,500,500
BEGIN DESCRIPTION:
SOUTH WILLOW CREEK 37.0
END DESCRIPTION:
XS GIS Cut Line= 3
      2745905.67     10246753.14      2746178.71     10246228.88
      2745905.70     10245703.14
#Sta/Elev= 30
  4408.9 1289.59  4511.2 1287.36  4610.4 1283.56  4638.2 1283.43  4726.6 1280.68
  4765.1 1278.76  4831.4 1277.85  4847.9 1276.62  4919.8 1274.85  4936.3 1273.09
  4941.9 1274.39  4950.1 1273.13  4958.4 1270.56  4964.0 1272.68  4972.7 1268.21
  4984.1 1267.70  4984.4 1267.20  4988.1 1267.70  5000.0 1268.25  5014.8 1271.98
  5020.4 1272.50  5051.6 1272.78  5074.1 1271.16  5103.2 1273.08  5213.8 1274.24
  5378.3 1281.39  5400.9 1281.49  5451.5 1284.12  5468.0 1284.08  5592.4 1288.58
#Mann=3,-1,0
  4408.9    0.05       0  4984.1    0.05       0  4988.1    0.05       0
Bank Sta=4984.1,4988.1
Exp/Cntr=0.3,0.1

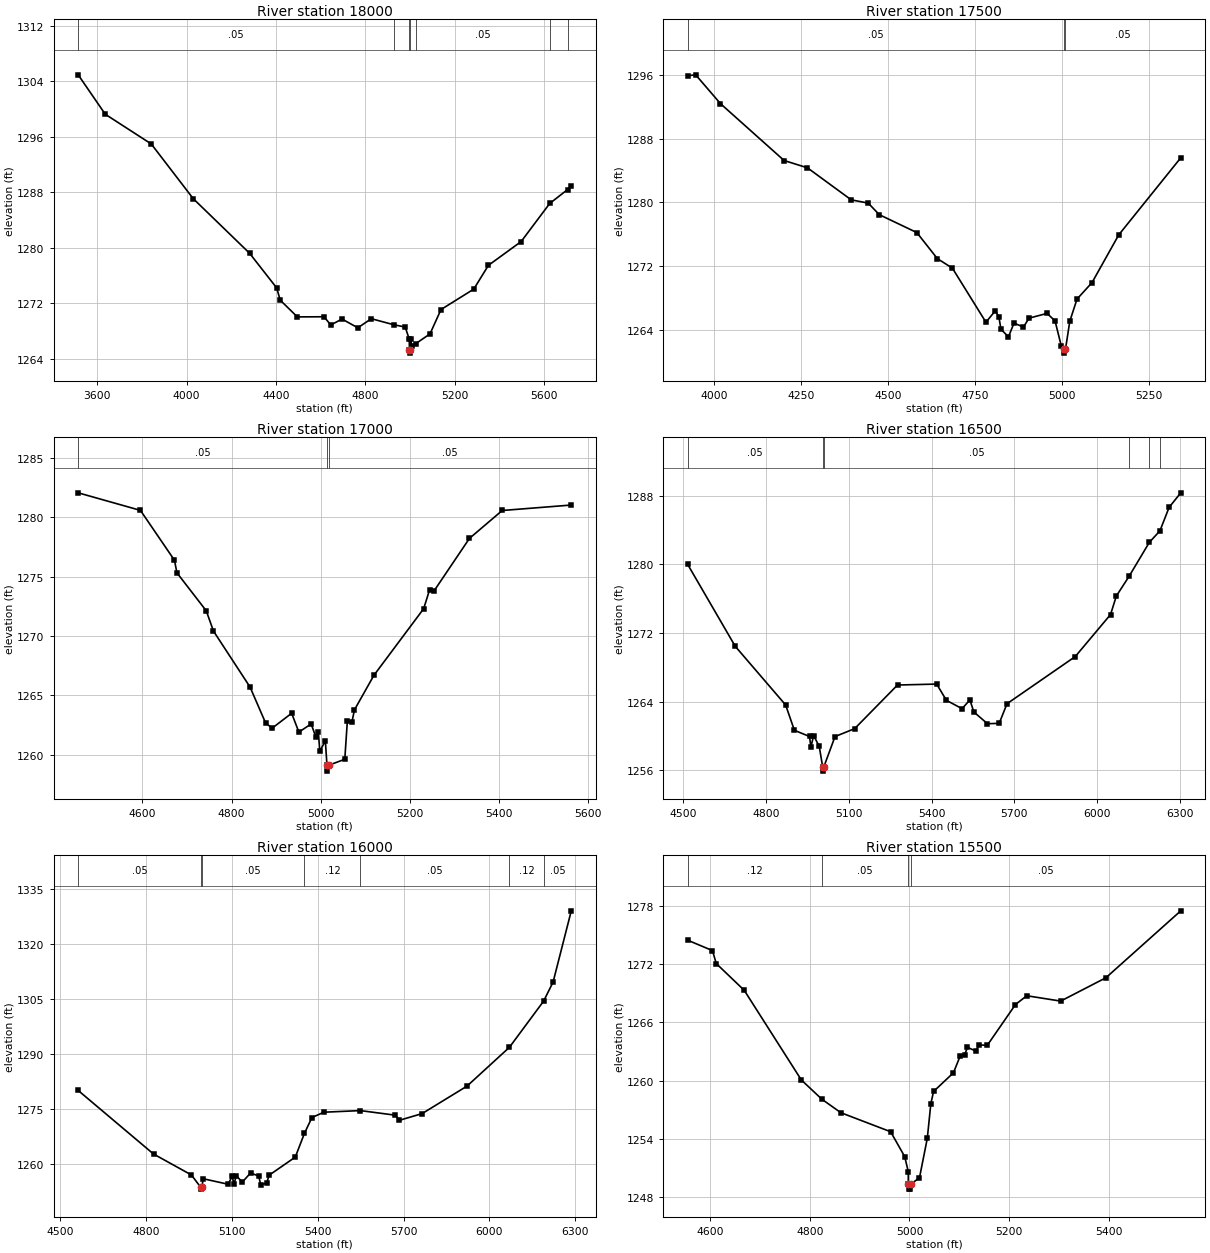
Type RM Length L Ch R = 1,18000,500,500,500
BEGIN DESCRIPTION:
SOUTH WILLOW CREEK 36.0
END DESCRIPTION:
XS GIS Cut Line= 3
      2746405.68     10247503.16      2746610.80     10246031.69
      2746508.92     10245316.91
#Sta/Elev= 30
  3514.3 1304.91  3635.5 1299.23  3841.4 1294.95  4029.3 1287.07  4281.7 1279.20
  4402.9 1274.21  4418.9 1272.44  4495.5 1270.03  4614.9 1270.05  4645.2 1268.87
  4695.7 1269.72  4766.3 1268.46  4826.9 1269.77  4927.3 1268.90  4978.4 1268.57
  4996.4 1266.84  4997.6 1265.31  4997.8 1264.81  5001.6 1265.31  5002.2 1266.84
  5008.7 1265.78  5026.3 1266.19  5089.5 1267.58  5138.7 1271.09  5285.4 1274.03
  5351.1 1277.46  5497.7 1280.89  5625.4 1286.37  5705.6 1288.38  5722.0 1288.91
#Mann=7,-1,0
  3514.3    0.05       0  4927.3    0.12       0  4997.6    0.07       0
  5001.6    0.12       0  5026.3    0.05       0  5625.4    0.12       0
  5705.6    0.05       0
Bank Sta=4997.6,5001.6
Exp/Cntr=0.3,0.1

Type RM Length L Ch R = 1,17500,500,500,500
BEGIN DESCRIPTION:
SOUTH WILLOW CREEK 35.0
END DESCRIPTION:
XS GIS Cut Line= 3
      2746455.69     10247253.10      2746987.26     10246316.54
      2747255.66     10246103.13
#Sta/Elev= 30
  3923.1 1295.92  3946.1 1296.03  4017.5 1292.41  4200.7 1285.27  4268.0 1284.35
  4394.0 1280.33  4443.0 1279.92  4474.7 1278.47  4582.9 1276.22  4642.0 1272.95
  4685.3 1271.75  4781.9 1264.96  4809.3 1266.42  4819.4 1265.57  4825.2 1264.07
  4846.8 1263.13  4862.7 1264.85  4890.0 1264.35  4905.9 1265.47  4957.9 1266.07
  4980.9 1265.13  4999.1 1261.94  5006.9 1261.58  5007.2 1261.08  5011.0 1261.58
  5023.4 1265.09  5044.2 1267.87  5087.4 1269.94  5164.3 1275.93  5342.9 1285.61
#Mann=3,-1,0
  3923.1    0.05       0  5006.9    0.05       0  5011.0    0.05       0
Bank Sta=5006.9,5011
Exp/Cntr=0.3,0.1

Type RM Length L Ch R = 1,17000,500,500,500
BEGIN DESCRIPTION:
SOUTH WILLOW CREEK 34.0
END DESCRIPTION:
XS GIS Cut Line= 3
      2746705.67     10246953.12      2747184.75     10246695.19
      2747455.67     10246203.14
#Sta/Elev= 30
  4455.9 1282.07  4595.5 1280.59  4671.7 1276.39  4677.4 1275.32  4743.1 1272.12
  4759.3 1270.41  4841.3 1265.69  4876.1 1262.67  4890.8 1262.22  4934.6 1263.48
  4950.8 1261.89  4978.4 1262.58  4988.9 1261.47  4994.6 1261.87  4997.7 1260.27
  5010.2 1261.16  5013.8 1259.10  5014.1 1258.60  5018.0 1259.10  5053.8 1259.60
  5059.5 1262.82  5069.8 1262.75  5075.5 1263.77  5119.1 1266.68  5230.7 1272.30
  5244.1 1273.91  5253.5 1273.77  5333.4 1278.23  5406.9 1280.58  5561.7 1281.04
#Mann=3,-1,0
  4455.9    0.05       0  5013.8    0.05       0  5018.0    0.05       0
Bank Sta=5013.8,5018
Exp/Cntr=0.3,0.1

Type RM Length L Ch R = 1,16500,500,500,500
BEGIN DESCRIPTION:
SOUTH WILLOW CREEK 33.0
END DESCRIPTION:
XS GIS Cut Line= 3
      2746805.64     10247253.12      2747282.82     10247170.94
      2748255.70     10246303.10
#Sta/Elev= 30
  4515.8 1280.00  4688.3 1270.45  4871.0 1263.61  4902.7 1260.66  4957.5 1259.94
  4962.6 1258.71  4972.5 1260.05  4992.8 1258.78  5005.2 1256.40  5005.5 1255.90
  5009.5 1256.40  5050.0 1259.93  5121.1 1260.85  5276.6 1265.94  5418.7 1266.05
  5453.8 1264.16  5510.7 1263.18  5539.1 1264.21  5553.3 1262.80  5602.7 1261.43
  5645.3 1261.47  5673.7 1263.76  5921.2 1269.26  6049.1 1274.16  6070.0 1276.31
  6116.0 1278.60  6189.9 1282.58  6228.2 1283.92  6261.5 1286.66  6303.7 1288.35
#Mann=6,-1,0
  4515.8    0.05       0  5005.2    0.05       0  5009.5    0.05       0
  6116.0    0.12       0  6189.9    0.05       0  6228.2    0.12       0
Bank Sta=5005.2,5009.5
Exp/Cntr=0.3,0.1

Type RM Length L Ch R = 1,16000,500,500,500
BEGIN DESCRIPTION:
SOUTH WILLOW CREEK 32.0
END DESCRIPTION:
XS GIS Cut Line= 3
      2747505.68     10247703.12      2747728.58     10247327.70
      2748505.71     10246303.07
#Sta/Elev= 30
  4563.4 1280.16  4826.5 1262.83  4958.8 1257.12  4991.5 1253.75  4991.8 1253.25
  4996.0 1253.75  4999.8 1256.09  5086.8 1254.59  5101.3 1256.70  5107.6 1254.64
  5115.9 1256.89  5136.7 1255.16  5165.8 1257.67  5194.0 1256.81  5201.2 1254.43
  5222.0 1254.93  5230.3 1257.04  5321.9 1261.99  5353.6 1268.43  5380.0 1272.78
  5421.7 1274.23  5549.3 1274.67  5671.3 1273.42  5685.9 1272.03  5764.9 1273.85
  5922.0 1281.36  6070.0 1291.94  6189.4 1304.53  6222.5 1309.73  6286.0 1329.16
#Mann=7,-1,0
  4563.4    0.05       0  4991.5    0.03       0  4996.0    0.05       0
  5353.6    0.12       0  5549.3    0.05       0  6070.0    0.12       0
  6189.4    0.05       0
Bank Sta=4991.5,4996
Exp/Cntr=0.3,0.1

Type RM Length L Ch R = 1,15500,500,500,500
BEGIN DESCRIPTION:
SOUTH WILLOW CREEK 31.0
END DESCRIPTION:
XS GIS Cut Line= 3
      2747905.69     10247603.10      2748171.62     10247245.43
      2748405.67     10246753.14
#Sta/Elev= 30
  4554.3 1274.44  4604.1 1273.37  4611.7 1272.04  4667.9 1269.29  4782.7 1260.07
  4824.0 1258.09  4862.0 1256.71  4962.1 1254.75  4990.4 1252.19  4997.5 1250.66
  4997.7 1249.35  4998.1 1248.85  5002.0 1248.85  5002.3 1249.35  5020.1 1250.02
  5035.8 1254.08  5042.9 1257.64  5048.4 1258.89  5088.3 1260.81  5102.2 1262.58
  5111.0 1262.68  5116.5 1263.43  5133.7 1263.03  5139.3 1263.67  5156.4 1263.64
  5213.0 1267.83  5235.7 1268.73  5303.8 1268.18  5394.7 1270.58  5545.1 1277.46
#Mann=4,-1,0
  4554.3    0.12       0  4824.0    0.05       0  4997.7    0.05       0
  5002.3    0.05       0
Bank Sta=4997.7,5002.3
Exp/Cntr=0.3,0.1

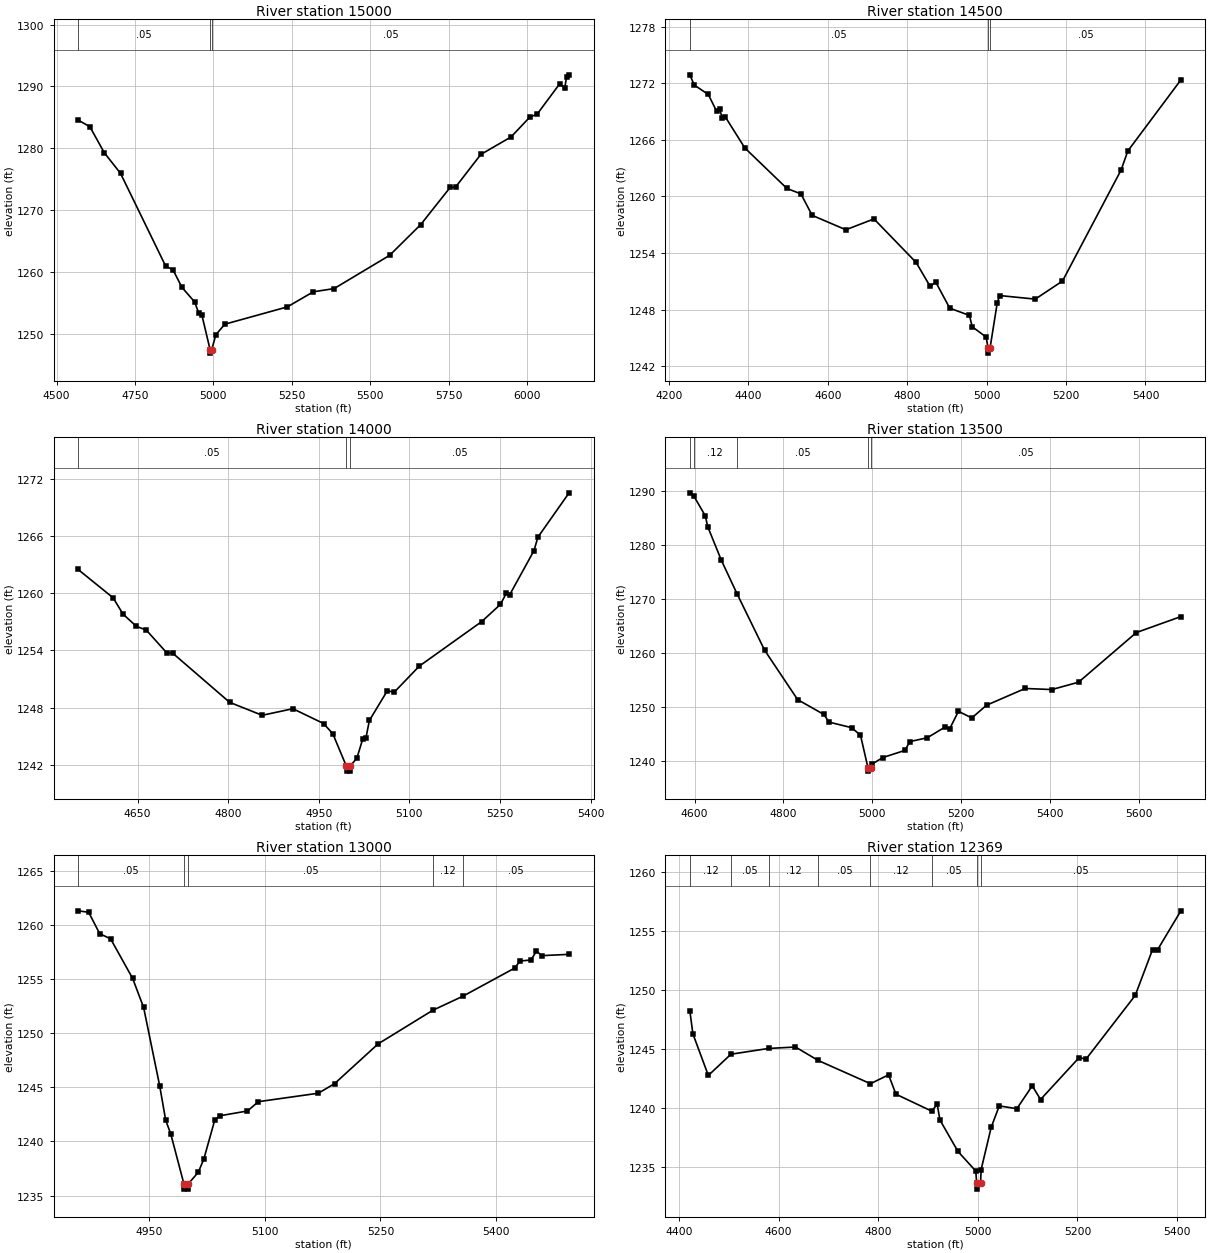
Type RM Length L Ch R = 1,15000,500,500,500
BEGIN DESCRIPTION:
SOUTH WILLOW CREEK 30.0
END DESCRIPTION:
XS GIS Cut Line= 3
      2748255.67     10248053.15      2748433.53     10247660.23
      2748955.67     10246653.14
#Sta/Elev= 30
  4568.7 1284.56  4606.1 1283.50  4652.3 1279.27  4704.0 1275.94  4848.1 1260.92
  4871.2 1260.35  4899.8 1257.50  4940.5 1255.13  4952.9 1253.39  4963.6 1252.98
  4989.9 1247.36  4990.3 1246.86  4994.5 1247.36  5008.0 1249.84  5036.7 1251.54
  5235.9 1254.34  5318.7 1256.78  5385.1 1257.30  5562.1 1262.68  5661.3 1267.66
  5755.7 1273.70  5772.2 1273.71  5852.8 1279.00  5949.2 1281.83  6009.9 1285.08
  6032.0 1285.48  6104.1 1290.41  6120.6 1289.78  6126.2 1291.51  6134.4 1291.88
#Mann=3,-1,0
  4568.7    0.05       0  4989.9    0.05       0  4994.5    0.05       0
Bank Sta=4989.9,4994.5
Exp/Cntr=0.3,0.1

Type RM Length L Ch R = 1,14500,500,500,500
BEGIN DESCRIPTION:
SOUTH WILLOW CREEK 29.0
END DESCRIPTION:
XS GIS Cut Line= 3
      2748356.07     10248199.17      2748892.89     10247679.00
      2749005.69     10247203.08
#Sta/Elev= 30
  4252.5 1272.91  4263.7 1271.82  4298.9 1270.83  4320.2 1269.02  4327.2 1269.32
  4334.4 1268.29  4341.4 1268.47  4391.0 1265.15  4497.0 1260.85  4532.2 1260.28
  4560.5 1258.00  4645.4 1256.47  4716.2 1257.62  4822.4 1253.00  4857.6 1250.47
  4871.8 1250.92  4907.0 1248.15  4956.7 1247.38  4963.6 1246.18  4998.5 1245.09
  5003.8 1243.88  5004.1 1243.38  5008.4 1243.88  5026.6 1248.70  5032.8 1249.49
  5122.4 1249.11  5191.0 1251.03  5338.7 1262.82  5355.5 1264.83  5489.1 1272.37
#Mann=3,-1,0
  4252.5    0.05       0  5003.8    0.05       0  5008.4    0.05       0
Bank Sta=5003.8,5008.4
Exp/Cntr=0.3,0.1

Type RM Length L Ch R = 1,14000,500,500,500
BEGIN DESCRIPTION:
SOUTH WILLOW CREEK 28.0
END DESCRIPTION:
XS GIS Cut Line= 3
      2749155.69     10248003.11      2749363.78     10247605.69
      2749455.69     10247253.08
#Sta/Elev= 30
  4551.4 1262.49  4609.4 1259.52  4625.8 1257.81  4647.9 1256.53  4664.3 1256.14
  4698.1 1253.76  4708.4 1253.70  4802.3 1248.57  4856.2 1247.21  4907.0 1247.90
  4957.8 1246.35  4973.2 1245.27  4995.7 1241.86  4996.2 1241.36  5001.1 1241.36
  5001.5 1241.86  5013.0 1242.72  5022.8 1244.75  5027.9 1244.81  5033.7 1246.67
  5063.3 1249.77  5075.0 1249.64  5116.3 1252.36  5219.7 1257.03  5250.7 1258.83
  5260.6 1260.02  5265.7 1259.80  5306.2 1264.46  5312.7 1265.87  5364.4 1270.52
#Mann=3,-1,0
  4551.4    0.05       0  4995.7    0.05       0  5001.5    0.05       0
Bank Sta=4995.7,5001.5
Exp/Cntr=0.3,0.1

Type RM Length L Ch R = 1,13500,500,500,500
BEGIN DESCRIPTION:
SOUTH WILLOW CREEK 27.0
END DESCRIPTION:
XS GIS Cut Line= 3
      2749505.69     10248403.10      2749566.14     10247997.08
      2749605.68     10247303.10
#Sta/Elev= 30
  4589.5 1289.57  4598.1 1289.02  4624.2 1285.33  4629.9 1283.28  4660.3 1277.13
  4695.5 1270.95  4757.8 1260.48  4832.2 1251.34  4891.4 1248.59  4902.9 1247.18
  4953.5 1246.16  4973.7 1244.77  4990.9 1238.62  4991.4 1238.12  4996.8 1238.62
  4999.5 1239.41  5024.0 1240.63  5074.1 1241.96  5084.5 1243.57  5124.2 1244.29
  5164.2 1246.27  5174.2 1245.89  5194.3 1249.18  5224.3 1247.95  5257.5 1250.30
  5344.5 1253.40  5404.6 1253.20  5464.7 1254.56  5594.9 1263.74  5695.1 1266.69
#Mann=5,-1,0
  4589.5    0.05       0  4598.1    0.12       0  4695.5    0.05       0
  4990.9    0.05       0  4996.8    0.05       0
Bank Sta=4990.9,4996.8
Exp/Cntr=0.3,0.1

Type RM Length L Ch R = 1,13000,631,631,631
BEGIN DESCRIPTION:
SOUTH WILLOW CREEK 26.0
END DESCRIPTION:
XS GIS Cut Line= 3
      2750105.67     10248103.10      2749997.80     10248010.60
      2749655.69     10247653.12
#Sta/Elev= 30
  4857.9 1261.31  4871.6 1261.18  4885.9 1259.20  4900.1 1258.72  4928.7 1255.06
  4942.9 1252.38  4963.8 1245.12  4971.5 1241.97  4978.1 1240.70  4995.1 1236.10
  4995.6 1235.60  5000.5 1235.60  5001.0 1236.10  5013.8 1237.16  5021.0 1238.38
  5035.2 1241.99  5042.1 1242.38  5077.6 1242.82  5091.8 1243.68  5169.5 1244.46
  5190.5 1245.34  5247.1 1249.02  5317.9 1252.12  5357.0 1253.42  5424.2 1256.02
  5431.1 1256.67  5445.3 1256.77  5452.5 1257.59  5459.4 1257.17  5494.8 1257.29
#Mann=5,-1,0
  4857.9    0.05       0  4995.1    0.05       0  5001.0    0.05       0
  5317.9    0.12       0  5357.0    0.05       0
Bank Sta=4995.1,5001
Exp/Cntr=0.3,0.1

Type RM Length L Ch R = 1,12369,193,193,193
BEGIN DESCRIPTION:
Mapping XS 93235312
END DESCRIPTION:
XS GIS Cut Line= 4
      2750414.36     10248199.15      2750372.16     10247824.09
      2750456.56     10247481.83      2750569.10     10247252.05
#Sta/Elev= 30
  4421.8 1248.23  4427.9 1246.28  4458.9 1242.75  4504.3 1244.55  4579.8 1245.04
  4633.9 1245.16  4679.5 1244.02  4784.4 1242.05  4820.8 1242.80  4835.6 1241.16
  4907.1 1239.73  4918.5 1240.30  4923.8 1238.98  4960.0 1236.31  4995.9 1234.64
  4997.6 1233.61  4998.1 1233.11  5005.4 1233.61  5006.6 1234.77  5026.8 1238.35
  5043.0 1240.17  5078.3 1239.93  5109.2 1241.87  5125.9 1240.71  5203.5 1244.27
  5217.1 1244.13  5316.0 1249.54  5350.7 1253.42  5361.0 1253.42  5407.6 1256.71
#Mann=8,-1,0
  4421.8    0.12       0  4504.3    0.05       0  4579.8    0.12       0
  4679.5    0.05       0  4784.4    0.12       0  4907.1    0.05       0
  4997.6    0.05       0  5005.4    0.05       0
Bank Sta=4997.6,5005.4
Exp/Cntr=0.3,0.1

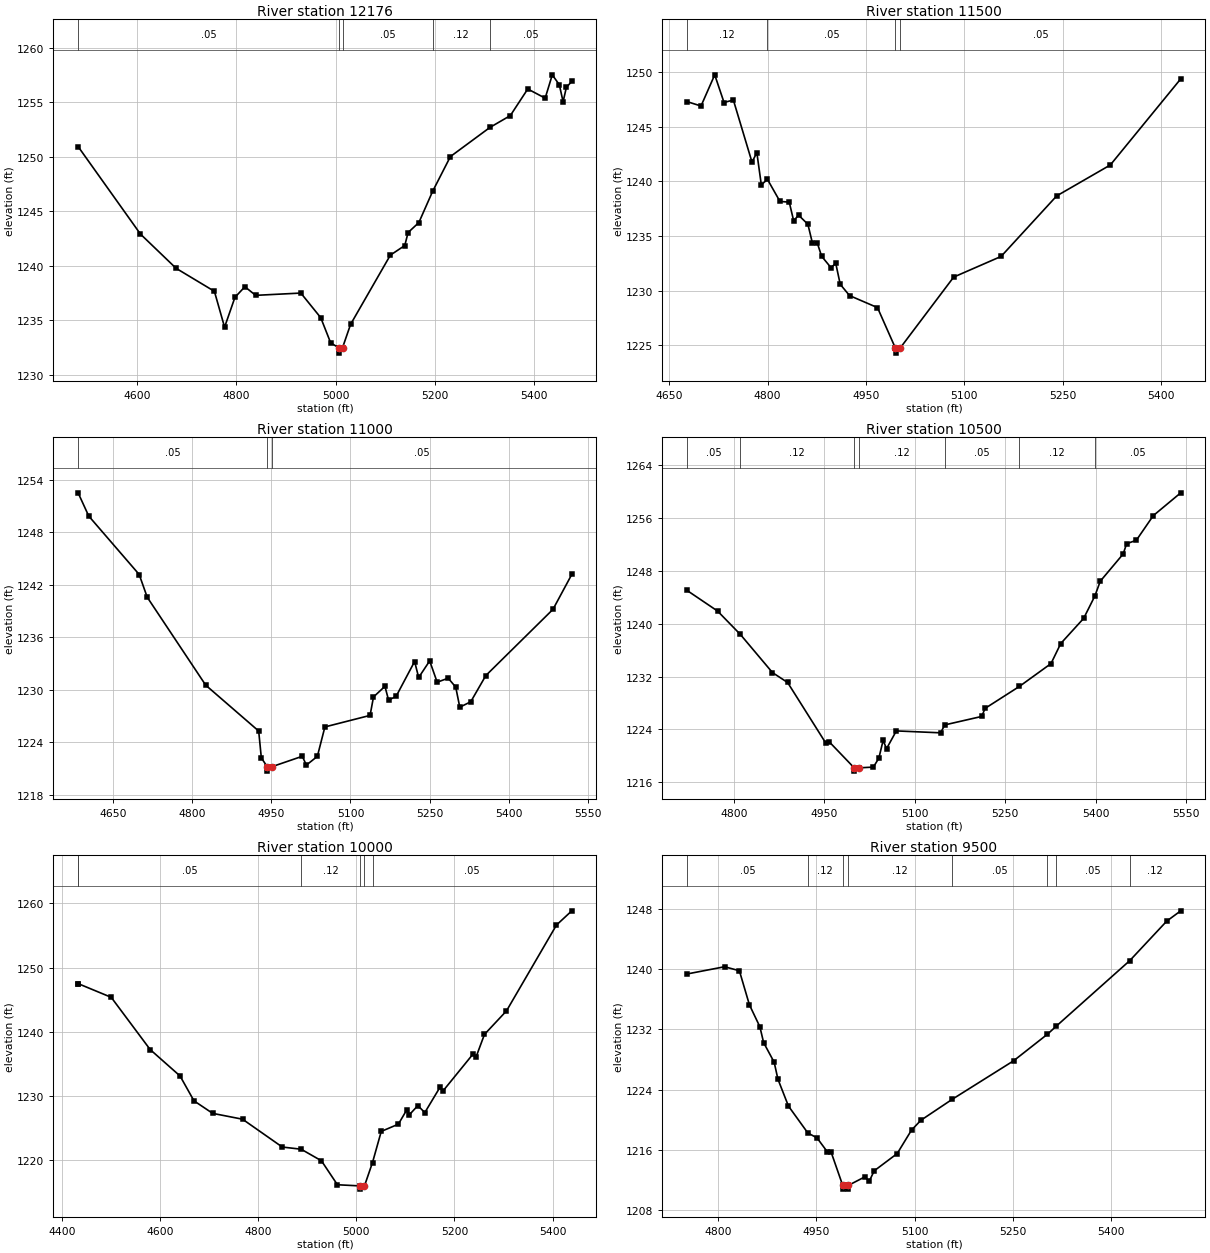
Type RM Length L Ch R = 1,12176,676,676,676
BEGIN DESCRIPTION:
Mapping XS 50581a0c
END DESCRIPTION:
XS GIS Cut Line= 5
      2750676.93     10248246.09      2750569.08     10247880.36
      2750583.15     10247613.11      2750714.43     10247467.76
      2750826.96     10247369.30
#Sta/Elev= 30
  4481.5 1250.92  4607.1 1242.89  4678.9 1239.75  4756.0 1237.64  4776.5 1234.35
  4797.4 1237.09  4817.4 1238.06  4839.1 1237.27  4930.1 1237.48  4970.2 1235.22
  4990.2 1232.91  5006.3 1232.47  5006.8 1231.97  5014.1 1232.47  5030.3 1234.61
  5110.4 1240.96  5139.4 1241.84  5146.1 1243.03  5167.8 1243.95  5195.4 1246.80
  5231.3 1250.00  5311.1 1252.68  5352.0 1253.76  5387.1 1256.20  5422.2 1255.36
  5436.5 1257.50  5450.7 1256.59  5458.3 1255.03  5464.9 1256.35  5475.8 1256.90
#Mann=5,-1,0
  4481.5    0.05       0  5006.3    0.05       0  5014.1    0.05       0
  5195.4    0.12       0  5311.1    0.05       0
Bank Sta=5006.3,5014.1
Exp/Cntr=0.3,0.1

Type RM Length L Ch R = 1,11500,500,500,500
BEGIN DESCRIPTION:
SOUTH WILLOW CREEK 23.0
END DESCRIPTION:
XS GIS Cut Line= 3
      2750955.68     10248253.12      2751172.57     10248014.17
      2751405.70     10247653.09
#Sta/Elev= 30
  4677.3 1247.28  4698.6 1246.88  4719.5 1249.73  4733.7 1247.20  4747.9 1247.43
  4776.3 1241.75  4783.7 1242.62  4790.5 1239.68  4799.9 1240.17  4818.9 1238.16
  4833.1 1238.09  4839.8 1236.39  4847.3 1236.90  4861.5 1236.07  4868.2 1234.40
  4875.6 1234.40  4882.4 1233.15  4896.6 1232.11  4904.0 1232.49  4910.8 1230.58
  4925.0 1229.55  4967.6 1228.45  4994.6 1224.79  4995.1 1224.29  5002.6 1224.79
  5083.7 1231.24  5156.0 1233.13  5240.7 1238.66  5322.5 1241.49  5429.8 1249.36
#Mann=4,-1,0
  4677.3    0.12       0  4799.9    0.05       0  4994.6    0.05       0
  5002.6    0.05       0
Bank Sta=4994.6,5002.6
Exp/Cntr=0.3,0.1

Type RM Length L Ch R = 1,11000,500,500,500
BEGIN DESCRIPTION:
SOUTH WILLOW CREEK 22.0
END DESCRIPTION:
XS GIS Cut Line= 3
      2751405.68     10248753.13      2751459.68     10248339.95
      2751855.70     10248003.10
#Sta/Elev= 30
  4583.3 1252.54  4603.5 1249.88  4699.2 1243.19  4714.4 1240.59  4825.4 1230.52
  4925.9 1225.27  4930.9 1222.20  4942.1 1221.18  4942.6 1220.68  4950.7 1221.18
  5008.6 1222.38  5016.4 1221.37  5037.2 1222.37  5051.5 1225.74  5137.2 1227.06
  5143.7 1229.17  5165.4 1230.39  5172.3 1228.81  5186.6 1229.24  5221.7 1233.23
  5229.4 1231.40  5250.3 1233.30  5264.5 1230.86  5285.4 1231.32  5299.7 1230.30
  5307.4 1228.00  5328.2 1228.62  5356.8 1231.62  5484.2 1239.20  5519.9 1243.20
#Mann=3,-1,0
  4583.3    0.05       0  4942.1    0.03       0  4950.7    0.05       0
Bank Sta=4942.1,4950.7
Exp/Cntr=0.3,0.1

Type RM Length L Ch R = 1,10500,500,500,500
BEGIN DESCRIPTION:
SOUTH WILLOW CREEK 21.0
END DESCRIPTION:
XS GIS Cut Line= 3
      2751805.68     10248803.16      2751847.36     10248528.51
      2752105.66     10248053.15
#Sta/Elev= 30
  4722.2 1245.04  4772.8 1241.92  4810.7 1238.37  4863.9 1232.60  4889.0 1231.10
  4952.7 1221.87  4957.7 1222.15  4999.4 1218.18  4999.9 1217.68  5008.0 1218.18
  5031.2 1218.29  5040.3 1219.63  5047.4 1222.33  5053.1 1221.08  5069.3 1223.77
  5142.7 1223.48  5149.7 1224.68  5210.9 1225.96  5216.5 1227.18  5273.5 1230.51
  5325.8 1233.96  5342.0 1237.00  5380.0 1240.81  5398.7 1244.22  5407.5 1246.43
  5445.6 1250.57  5451.2 1252.11  5467.4 1252.64  5495.5 1256.37  5541.0 1259.82
#Mann=7,-1,0
  4722.2    0.05       0  4810.7    0.12       0  4999.4    0.07       0
  5008.0    0.12       0  5149.7    0.05       0  5273.5    0.12       0
  5398.7    0.05       0
Bank Sta=4999.4,5008
Exp/Cntr=0.3,0.1

Type RM Length L Ch R = 1,10000,500,500,500
BEGIN DESCRIPTION:
SOUTH WILLOW CREEK 20.0
END DESCRIPTION:
XS GIS Cut Line= 3
      2751755.69     10248853.11      2752259.97     10248593.47
      2752655.67     10248403.12
#Sta/Elev= 30
  4432.8 1247.52  4432.9 1247.52  4500.3 1245.39  4579.7 1237.26  4640.6 1233.15
  4669.0 1229.28  4707.1 1227.33  4768.0 1226.42  4849.0 1222.09  4887.5 1221.75
  4928.8 1219.95  4961.4 1216.22  5007.8 1216.04  5008.3 1215.54  5016.5 1216.04
  5032.9 1219.68  5050.7 1224.52  5085.6 1225.65  5102.6 1227.86  5108.2 1227.13
  5125.3 1228.54  5139.5 1227.45  5170.5 1231.40  5176.1 1230.77  5238.4 1236.62
  5244.0 1236.11  5261.1 1239.62  5306.0 1243.28  5407.9 1256.64  5439.1 1258.85
#Mann=6,-1,0
  4432.8    0.12       0  4432.9    0.05       0  4887.5    0.12       0
  5007.8    0.07       0  5016.5    0.12       0  5032.9    0.05       0
Bank Sta=5007.8,5016.5
Exp/Cntr=0.3,0.1

Type RM Length L Ch R = 1,9500,500,500,500
BEGIN DESCRIPTION:
SOUTH WILLOW CREEK 19.0
END DESCRIPTION:
XS GIS Cut Line= 3
      2752105.68     10249203.11      2752322.30     10249083.81
      2752705.68     10248753.11
#Sta/Elev= 30
  4752.7 1239.33  4810.0 1240.29  4832.6 1239.76  4847.9 1235.24  4863.9 1232.32
  4869.6 1230.22  4885.7 1227.62  4891.4 1225.38  4907.5 1221.80  4937.1 1218.23
  4951.1 1217.58  4967.1 1215.70  4972.8 1215.65  4990.3 1211.28  4990.8 1210.78
  4998.5 1210.78  4999.0 1211.28  5024.2 1212.41  5030.9 1211.84  5038.4 1213.21
  5073.5 1215.50  5095.4 1218.62  5109.7 1219.92  5157.5 1222.70  5251.2 1227.81
  5302.9 1231.34  5316.0 1232.38  5428.6 1241.11  5484.9 1246.34  5506.3 1247.71
#Mann=8,-1,0
  4752.7    0.05       0  4937.1    0.12       0  4990.3    0.07       0
  4999.0    0.12       0  5157.5    0.05       0  5302.9    0.12       0
  5316.0    0.05       0  5428.6    0.12       0
Bank Sta=4990.3,4999
Exp/Cntr=0.3,0.1