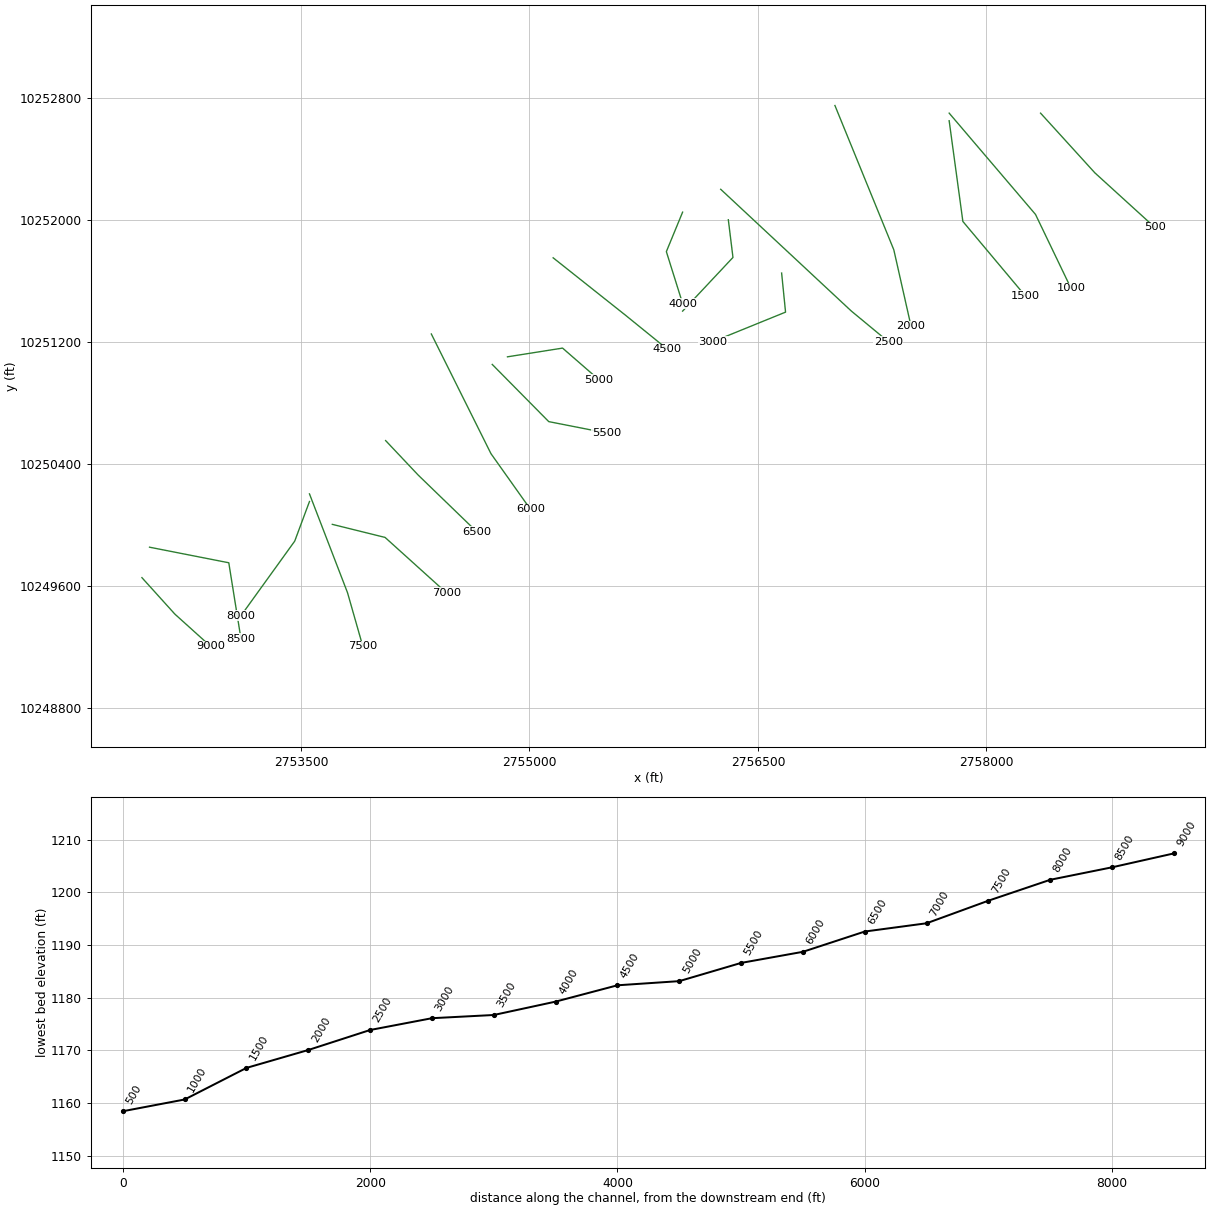
HEC-RAS study SOUTH WILLOW CREEK.prj: SOUTH WILLOW CREEK Base Level Engineering

--- SOUTH WILLOW CREEK.g01 (geometry) --- (continued)

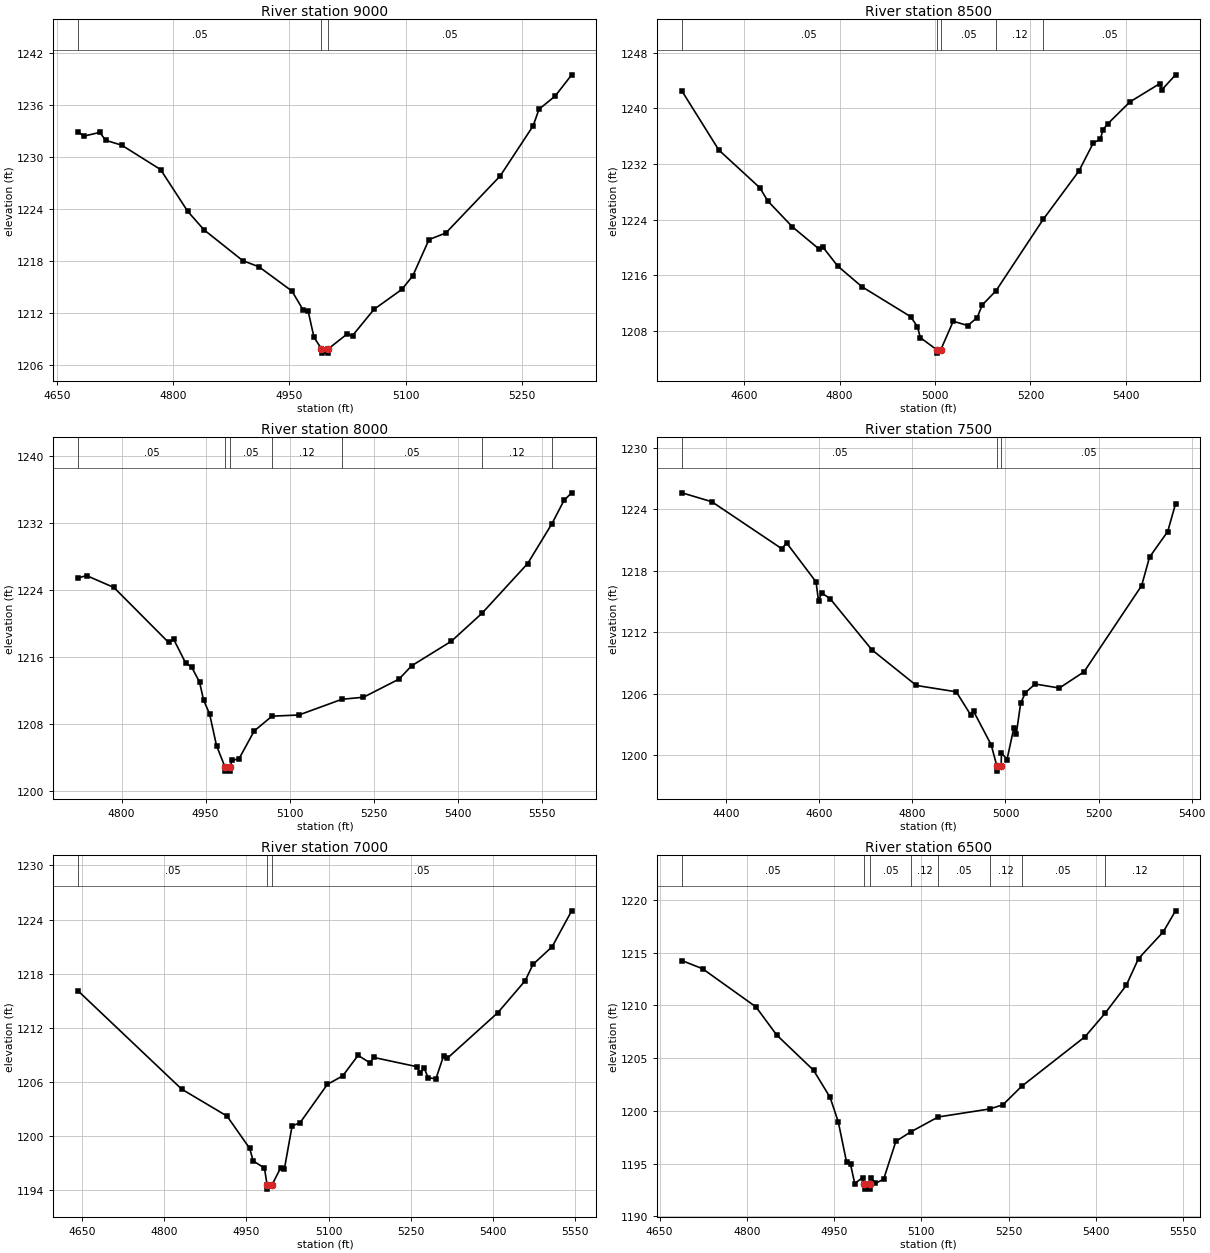
Type RM Length L Ch R = 1,9000,500,500,500
BEGIN DESCRIPTION:
SOUTH WILLOW CREEK 18.0
END DESCRIPTION:
XS GIS Cut Line= 3
      2752455.69     10249653.10      2752672.22     10249413.56
      2752905.67     10249203.12
#Sta/Elev= 30
  4677.1 1232.96  4684.2 1232.44  4705.1 1232.88  4712.6 1231.97  4733.5 1231.40
  4783.6 1228.59  4818.7 1223.76  4839.6 1221.64  4889.7 1218.08  4910.6 1217.37
  4953.2 1214.57  4967.4 1212.43  4974.1 1212.26  4981.6 1209.24  4991.3 1207.91
  4991.8 1207.41  4999.7 1207.41  5000.2 1207.91  5024.0 1209.59  5031.4 1209.43
  5059.1 1212.46  5095.0 1214.76  5109.2 1216.33  5130.1 1220.51  5151.8 1221.27
  5222.0 1227.85  5264.6 1233.64  5272.1 1235.55  5293.0 1237.07  5314.3 1239.52
#Mann=3,-1,0
  4677.1    0.05       0  4991.3    0.05       0  5000.2    0.05       0
Bank Sta=4991.3,5000.2
Exp/Cntr=0.3,0.1

Type RM Length L Ch R = 1,8500,500,500,500
BEGIN DESCRIPTION:
SOUTH WILLOW CREEK 17.0
END DESCRIPTION:
XS GIS Cut Line= 3
      2752505.65     10249853.12      2753025.90     10249750.91
      2753105.69     10249253.06
#Sta/Elev= 30
  4469.8 1242.49  4547.0 1234.01  4632.9 1228.58  4649.8 1226.66  4701.2 1222.95
  4757.7 1219.72  4765.4 1220.01  4796.0 1217.32  4846.9 1214.33  4948.8 1210.03
  4963.4 1208.58  4969.2 1207.01  5003.4 1205.27  5003.9 1204.77  5012.3 1205.27
  5038.3 1209.36  5068.7 1208.74  5088.6 1209.89  5099.0 1211.70  5127.9 1213.74
  5226.7 1224.01  5301.6 1230.97  5332.0 1235.04  5346.7 1235.56  5352.2 1236.94
  5362.4 1237.80  5408.7 1240.94  5470.6 1243.54  5475.7 1242.69  5504.2 1244.83
#Mann=5,-1,0
  4469.8    0.05       0  5003.4    0.03       0  5012.3    0.05       0
  5127.9    0.12       0  5226.7    0.05       0
Bank Sta=5003.4,5012.3
Exp/Cntr=0.3,0.1

Type RM Length L Ch R = 1,8000,500,500,500
BEGIN DESCRIPTION:
SOUTH WILLOW CREEK 16.0
END DESCRIPTION:
XS GIS Cut Line= 3
      2753555.69     10250153.12      2753458.80     10249892.87
      2753105.67     10249403.09
#Sta/Elev= 30
  4722.3 1225.46  4737.5 1225.74  4786.3 1224.32  4883.8 1217.77  4893.0 1218.14
  4914.4 1215.30  4925.0 1214.83  4939.2 1213.03  4946.4 1210.88  4957.1 1209.24
  4969.5 1205.44  4984.6 1202.90  4985.1 1202.40  4993.1 1202.40  4993.6 1202.90
  4997.3 1203.67  5009.9 1203.90  5036.9 1207.20  5068.6 1208.96  5116.6 1209.10
  5193.6 1210.98  5232.0 1211.22  5295.6 1213.39  5317.9 1214.97  5389.0 1217.91
  5443.6 1221.24  5525.2 1227.18  5568.6 1231.94  5590.3 1234.74  5603.8 1235.62
#Mann=7,-1,0
  4722.3    0.05       0  4984.6    0.03       0  4993.6    0.05       0
  5068.6    0.12       0  5193.6    0.05       0  5443.6    0.12       0
  5568.6    0.05       0
Bank Sta=4984.6,4993.6
Exp/Cntr=0.3,0.1

Type RM Length L Ch R = 1,7500,500,500,500
BEGIN DESCRIPTION:
SOUTH WILLOW CREEK 15.0
END DESCRIPTION:
XS GIS Cut Line= 3
      2753555.70     10250203.08      2753805.45     10249554.50
      2753905.68     10249203.12
#Sta/Elev= 30
  4305.0 1225.59  4369.2 1224.72  4519.3 1220.14  4530.0 1220.69  4593.0 1216.90
  4598.4 1215.03  4605.0 1215.82  4623.0 1215.27  4713.0 1210.27  4808.6 1206.79
  4894.3 1206.17  4926.1 1203.86  4931.5 1204.27  4969.3 1201.00  4981.5 1198.93
  4982.0 1198.43  4990.7 1198.93  4991.4 1200.22  5003.3 1199.56  5018.1 1202.67
  5023.3 1202.06  5032.6 1205.05  5043.0 1206.10  5063.8 1206.93  5115.8 1206.54
  5169.0 1208.13  5292.6 1216.54  5309.5 1219.31  5348.5 1221.81  5365.4 1224.52
#Mann=3,-1,0
  4305.0    0.05       0  4981.5    0.05       0  4990.7    0.05       0
Bank Sta=4981.5,4990.7
Exp/Cntr=0.3,0.1

Type RM Length L Ch R = 1,7000,500,500,500
BEGIN DESCRIPTION:
SOUTH WILLOW CREEK 14.0
END DESCRIPTION:
XS GIS Cut Line= 3
      2753705.68     10250003.11      2754052.12     10249917.33
      2754455.67     10249553.12
#Sta/Elev= 30
  4643.1 1216.10  4832.0 1205.22  4914.8 1202.23  4956.2 1198.65  4962.5 1197.26
  4983.1 1196.48  4987.8 1194.64  4988.3 1194.14  4997.1 1194.64  5012.6 1196.49
  5019.4 1196.36  5033.6 1201.16  5047.8 1201.47  5097.8 1205.74  5126.0 1206.69
  5153.9 1208.96  5175.6 1208.13  5182.3 1208.73  5260.7 1207.71  5267.5 1207.02
  5274.2 1207.59  5281.7 1206.49  5295.9 1206.36  5310.1 1208.94  5316.8 1208.64
  5408.9 1213.69  5458.8 1217.23  5473.0 1219.03  5508.1 1221.01  5543.6 1224.97
#Mann=3,-1,0
  4643.1    0.05       0  4987.8    0.05       0  4997.1    0.05       0
Bank Sta=4987.8,4997.1
Exp/Cntr=0.3,0.1

Type RM Length L Ch R = 1,6500,500,500,500
BEGIN DESCRIPTION:
SOUTH WILLOW CREEK 13.0
END DESCRIPTION:
XS GIS Cut Line= 3
      2754055.70     10250553.10      2754269.55     10250326.60
      2754655.67     10249953.12
#Sta/Elev= 30
  4688.5 1214.24  4723.9 1213.47  4815.7 1209.85  4851.3 1207.19  4914.8 1203.84
  4943.2 1201.27  4957.3 1198.94  4971.5 1195.14  4978.3 1194.93  4985.6 1193.10
  4999.0 1193.67  5002.2 1193.07  5002.7 1192.57  5011.1 1192.57  5011.6 1193.07
  5013.9 1193.61  5021.0 1193.12  5035.2 1193.50  5056.3 1197.10  5082.0 1198.00
  5128.9 1199.41  5217.3 1200.17  5240.2 1200.56  5272.4 1202.31  5381.7 1207.03
  5415.8 1209.23  5452.4 1211.89  5473.5 1214.43  5516.0 1216.96  5537.2 1218.96
#Mann=8,-1,0
  4688.5    0.05       0  5002.2    0.03       0  5011.6    0.05       0
  5082.0    0.12       0  5128.9    0.05       0  5217.3    0.12       0
  5272.4    0.05       0  5415.8    0.12       0
Bank Sta=5002.2,5011.6
Exp/Cntr=0.3,0.1

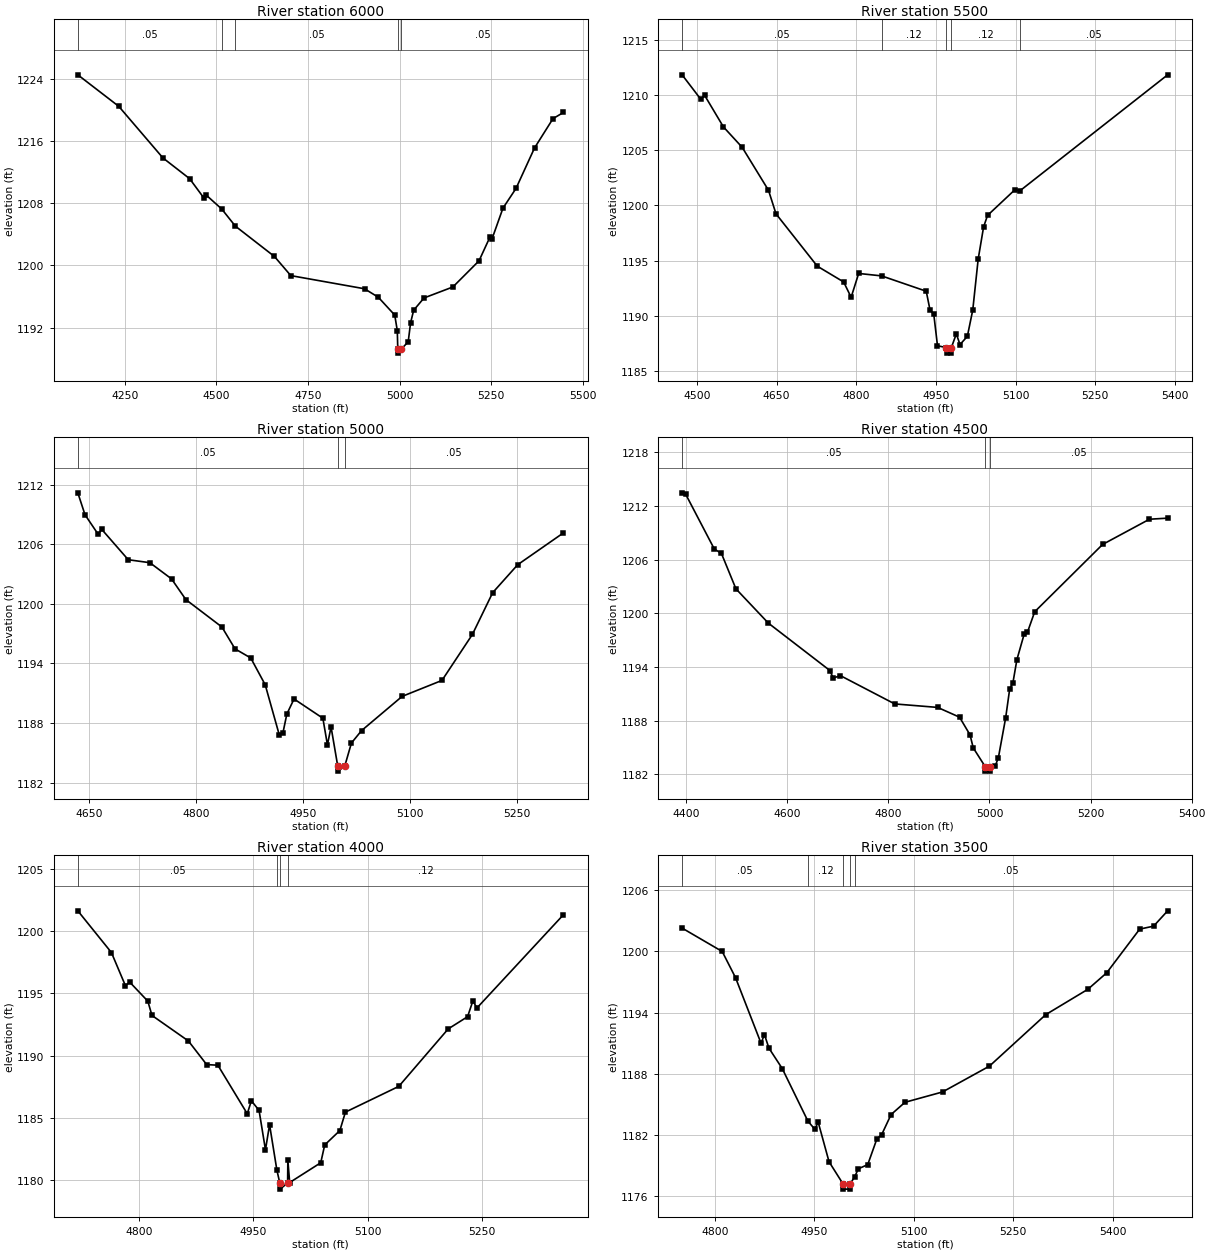
Type RM Length L Ch R = 1,6000,500,500,500
BEGIN DESCRIPTION:
SOUTH WILLOW CREEK 12.0
END DESCRIPTION:
XS GIS Cut Line= 3
      2754355.69     10251253.11      2754747.38     10250467.21
      2755005.67     10250103.12
#Sta/Elev= 30
  4121.9 1224.48  4233.6 1220.43  4354.1 1213.80  4426.8 1211.14  4466.0 1208.64
  4471.6 1209.05  4514.4 1207.24  4551.6 1205.04  4658.2 1201.14  4702.9 1198.68
  4904.0 1196.99  4941.6 1195.90  4986.4 1193.61  4993.4 1191.61  4994.7 1189.22
  4995.2 1188.72  5004.2 1189.22  5023.2 1190.19  5029.5 1192.58  5038.0 1194.23
  5066.3 1195.81  5145.0 1197.22  5216.3 1200.58  5245.9 1203.61  5252.0 1203.42
  5281.6 1207.35  5317.2 1209.88  5367.7 1215.08  5418.1 1218.85  5446.4 1219.64
#Mann=5,-1,0
  4121.9    0.05       0  4514.4    0.12       0  4551.6    0.05       0
  4994.7    0.05       0  5004.2    0.05       0
Bank Sta=4994.7,5004.2
Exp/Cntr=0.3,0.1

Type RM Length L Ch R = 1,5500,500,500,500
BEGIN DESCRIPTION:
SOUTH WILLOW CREEK 11.0
END DESCRIPTION:
XS GIS Cut Line= 3
      2754755.69     10251053.11      2755126.65     10250677.67
      2755505.69     10250603.11
#Sta/Elev= 30
  4472.2 1211.83  4507.6 1209.60  4514.6 1209.97  4550.0 1207.11  4585.3 1205.26
  4634.8 1201.37  4649.0 1199.23  4726.7 1194.49  4776.3 1193.06  4790.4 1191.67
  4804.6 1193.83  4847.7 1193.61  4931.8 1192.22  4938.9 1190.52  4946.0 1190.13
  4953.0 1187.28  4969.5 1187.11  4970.0 1186.61  4978.6 1186.61  4979.1 1187.11
  4988.4 1188.35  4995.4 1187.39  5009.2 1188.13  5019.4 1190.52  5029.6 1195.13
  5039.8 1198.05  5047.2 1199.09  5098.6 1201.41  5108.2 1201.32  5386.3 1211.83
#Mann=5,-1,0
  4472.2    0.05       0  4847.7    0.12       0  4969.5    0.07       0
  4979.1    0.12       0  5108.2    0.05       0
Bank Sta=4969.5,4979.1
Exp/Cntr=0.3,0.1

Type RM Length L Ch R = 1,5000,500,500,500
BEGIN DESCRIPTION:
SOUTH WILLOW CREEK 10.0
END DESCRIPTION:
XS GIS Cut Line= 3
      2754855.73     10251103.12      2755217.43     10251160.34
      2755455.71     10250953.09
#Sta/Elev= 30
  4633.8 1211.19  4643.9 1208.98  4662.4 1207.01  4667.5 1207.50  4704.6 1204.45
  4735.0 1204.15  4765.4 1202.52  4785.6 1200.43  4836.2 1197.67  4854.6 1195.47
  4876.7 1194.55  4897.0 1191.85  4917.0 1186.74  4922.0 1187.04  4927.4 1188.90
  4937.5 1190.42  4978.0 1188.48  4984.4 1185.80  4989.5 1187.60  4998.9 1183.65
  4999.4 1183.15  5008.7 1183.65  5018.1 1185.98  5032.3 1187.23  5089.3 1190.68
  5145.3 1192.29  5188.0 1196.92  5216.5 1201.13  5251.7 1203.95  5315.8 1207.15
#Mann=3,-1,0
  4633.8    0.05       0  4998.9    0.03       0  5008.7    0.05       0
Bank Sta=4998.9,5008.7
Exp/Cntr=0.3,0.1

Type RM Length L Ch R = 1,4500,500,500,500
BEGIN DESCRIPTION:
SOUTH WILLOW CREEK 9.0
END DESCRIPTION:
XS GIS Cut Line= 3
      2755155.70     10251753.10      2755631.92     10251375.12
      2755905.71     10251153.09
#Sta/Elev= 30
  4392.0 1213.46  4399.2 1213.29  4455.8 1207.17  4469.7 1206.70  4498.5 1202.73
  4562.6 1198.90  4684.4 1193.60  4690.8 1192.76  4705.2 1193.03  4812.6 1189.87
  4897.5 1189.48  4940.8 1188.39  4961.6 1186.41  4967.9 1184.96  4991.6 1182.86
  4992.1 1182.36  5001.4 1182.36  5001.9 1182.86  5011.2 1182.90  5017.7 1183.88
  5032.0 1188.30  5040.0 1191.53  5046.4 1192.23  5054.3 1194.82  5068.7 1197.68
  5075.1 1197.87  5089.5 1200.17  5223.8 1207.69  5316.5 1210.51  5352.5 1210.63
#Mann=3,-1,0
  4392.0    0.05       0  4991.6    0.03       0  5001.9    0.05       0
Bank Sta=4991.6,5001.9
Exp/Cntr=0.3,0.1

Type RM Length L Ch R = 1,4000,500,500,500
BEGIN DESCRIPTION:
SOUTH WILLOW CREEK 8.0
END DESCRIPTION:
XS GIS Cut Line= 3
      2756005.70     10252053.15      2755898.84     10251793.81
      2756005.70     10251453.07
#Sta/Elev= 30
  4719.5 1201.63  4763.6 1198.28  4782.1 1195.60  4787.5 1195.91  4811.4 1194.37
  4816.9 1193.22  4864.7 1191.17  4888.7 1189.27  4903.4 1189.22  4942.0 1185.32
  4947.4 1186.36  4957.5 1185.59  4965.9 1182.42  4971.3 1184.44  4980.9 1180.79
  4984.7 1179.76  4985.2 1179.26  4995.0 1179.76  4995.3 1181.58  4997.7 1179.79
  5038.5 1181.38  5043.7 1182.81  5063.6 1183.97  5070.9 1185.45  5141.0 1187.52
  5205.9 1192.14  5231.3 1193.12  5238.3 1194.39  5243.6 1193.82  5357.1 1201.31
#Mann=4,-1,0
  4719.5    0.05       0  4980.9    0.12       0  4984.7    0.07       0
  4995.0    0.12       0
Bank Sta=4984.7,4995
Exp/Cntr=0.3,0.1

Type RM Length L Ch R = 1,3500,500,500,500
BEGIN DESCRIPTION:
SOUTH WILLOW CREEK 7.0
END DESCRIPTION:
XS GIS Cut Line= 3
      2756305.68     10252003.11      2756336.25     10251755.59
      2756005.71     10251403.14
#Sta/Elev= 30
  4750.6 1202.27  4811.1 1199.98  4831.2 1197.42  4869.7 1191.00  4874.8 1191.85
  4881.6 1190.52  4901.7 1188.52  4940.4 1183.38  4950.8 1182.58  4955.9 1183.28
  4972.3 1179.40  4993.5 1177.22  4994.0 1176.72  5003.4 1176.72  5003.9 1177.22
  5010.8 1177.90  5016.5 1178.71  5030.7 1179.12  5044.5 1181.64  5051.7 1182.05
  5065.9 1184.02  5086.9 1185.22  5143.5 1186.23  5214.3 1188.76  5299.3 1193.80
  5362.8 1196.28  5391.2 1197.89  5441.0 1202.17  5462.0 1202.46  5483.2 1203.96
#Mann=5,-1,0
  4750.6    0.05       0  4940.4    0.12       0  4993.5    0.07       0
  5003.9    0.12       0  5010.8    0.05       0
Bank Sta=4993.5,5003.9
Exp/Cntr=0.3,0.1

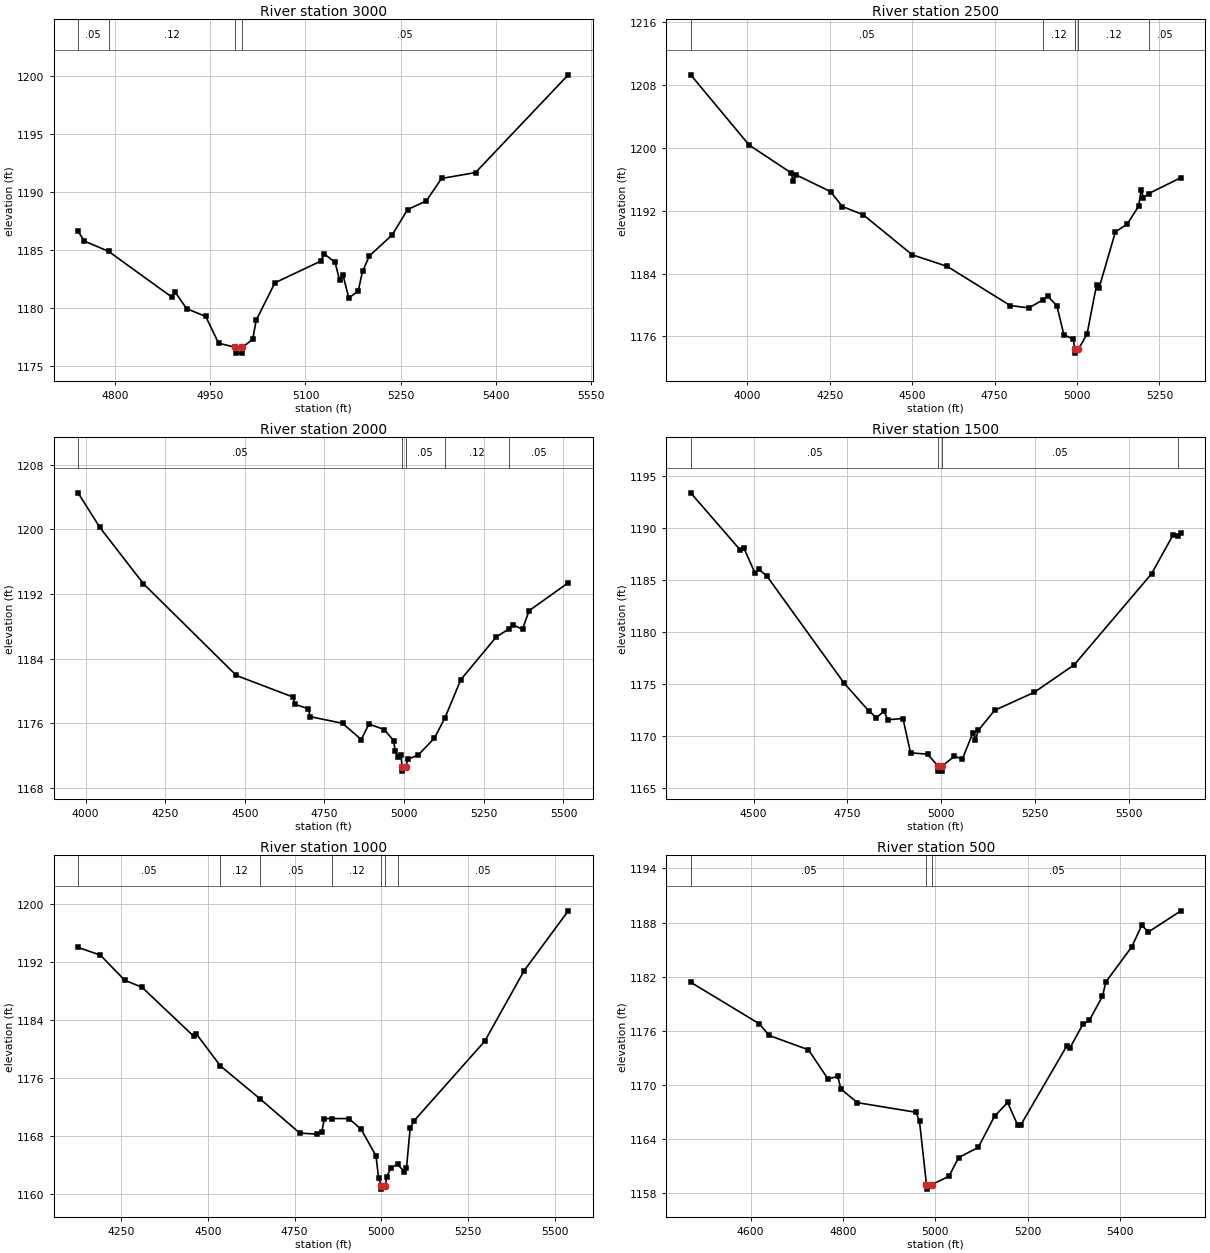
Type RM Length L Ch R = 1,3000,500,500,500
BEGIN DESCRIPTION:
SOUTH WILLOW CREEK 6.0
END DESCRIPTION:
XS GIS Cut Line= 3
      2756655.68     10251653.13      2756681.51     10251396.53
      2756205.71     10251203.12
#Sta/Elev= 30
  4742.1 1186.60  4752.2 1185.76  4790.1 1184.88  4889.9 1180.93  4894.9 1181.37
  4913.0 1179.94  4943.1 1179.27  4963.2 1176.97  4989.8 1176.61  4990.3 1176.11
  4999.9 1176.11  5000.4 1176.61  5017.0 1177.29  5022.4 1178.94  5051.9 1182.17
  5124.1 1184.04  5129.5 1184.67  5146.6 1183.93  5153.6 1182.44  5159.0 1182.86
  5168.2 1180.86  5183.0 1181.46  5189.8 1183.15  5200.6 1184.49  5236.6 1186.30
  5260.7 1188.48  5290.1 1189.22  5314.2 1191.16  5367.7 1191.67  5513.6 1200.09
#Mann=4,-1,0
  4742.1    0.05       0  4790.1    0.12       0  4989.8    0.05       0
  5000.4    0.05       0
Bank Sta=4989.8,5000.4
Exp/Cntr=0.3,0.1

Type RM Length L Ch R = 1,2500,500,500,500
BEGIN DESCRIPTION:
SOUTH WILLOW CREEK 5.0
END DESCRIPTION:
XS GIS Cut Line= 3
      2756255.69     10252203.11      2757112.87     10251404.00
      2757355.65     10251203.14
#Sta/Elev= 30
  3828.1 1209.28  4005.2 1200.35  4132.2 1196.82  4139.6 1195.77  4146.4 1196.58
  4252.4 1194.42  4288.1 1192.52  4351.6 1191.47  4500.1 1186.38  4606.6 1184.90
  4797.6 1179.92  4853.8 1179.63  4895.7 1180.62  4910.5 1181.14  4938.8 1179.91
  4960.3 1176.18  4988.7 1175.67  4992.8 1174.37  4993.3 1173.87  5004.2 1174.37
  5030.5 1176.32  5059.2 1182.54  5067.0 1182.18  5116.5 1189.31  5151.7 1190.26
  5186.8 1192.56  5194.7 1194.66  5201.2 1193.66  5217.5 1194.17  5315.1 1196.20
#Mann=5,-1,0
  3828.1    0.05       0  4895.7    0.12       0  4992.8    0.07       0
  5004.2    0.12       0  5217.5    0.05       0
Bank Sta=4992.8,5004.2
Exp/Cntr=0.3,0.1

Type RM Length L Ch R = 1,2000,500,500,500
BEGIN DESCRIPTION:
SOUTH WILLOW CREEK 4.0
END DESCRIPTION:
XS GIS Cut Line= 3
      2757005.69     10252753.09      2757392.35     10251805.54
      2757505.69     10251303.07
#Sta/Elev= 30
  3976.6 1204.51  4044.8 1200.24  4181.8 1193.26  4473.4 1181.91  4651.6 1179.23
  4657.0 1178.34  4699.6 1177.79  4705.0 1176.81  4806.6 1175.99  4865.4 1173.98
  4889.5 1175.89  4937.5 1175.22  4967.0 1173.84  4972.4 1172.52  4981.0 1171.81
  4991.0 1172.06  4992.9 1170.57  4993.4 1170.07  5004.3 1170.57  5012.7 1171.57
  5043.5 1172.04  5094.8 1174.13  5128.2 1176.67  5178.0 1181.40  5289.5 1186.69
  5327.7 1187.63  5340.8 1188.21  5371.5 1187.61  5392.0 1189.92  5515.1 1193.38
#Mann=5,-1,0
  3976.6    0.05       0  4992.9    0.05       0  5004.3    0.05       0
  5128.2    0.12       0  5327.7    0.05       0
Bank Sta=4992.9,5004.3
Exp/Cntr=0.3,0.1

Type RM Length L Ch R = 1,1500,500,500,500
BEGIN DESCRIPTION:
SOUTH WILLOW CREEK 3.0
END DESCRIPTION:
XS GIS Cut Line= 3
      2757755.68     10252653.12      2757845.67     10251991.91
      2758255.69     10251503.11
#Sta/Elev= 30
  4332.7 1193.43  4463.9 1187.96  4474.0 1188.13  4504.3 1185.69  4513.7 1186.07
  4534.6 1185.47  4741.0 1175.14  4807.0 1172.45  4827.2 1171.81  4847.4 1172.43
  4857.5 1171.61  4897.9 1171.73  4918.1 1168.43  4963.3 1168.30  4991.0 1167.17
  4991.5 1166.67  5002.2 1166.67  5002.7 1167.17  5035.0 1168.11  5055.8 1167.82
  5084.4 1170.38  5091.0 1169.70  5098.7 1170.59  5141.7 1172.51  5247.1 1174.24
  5353.8 1176.89  5559.7 1185.64  5616.5 1189.34  5630.6 1189.25  5638.0 1189.57
#Mann=4,-1,0
  4332.7    0.05       0  4991.0    0.05       0  5002.7    0.05       0
  5630.6    0.12       0
Bank Sta=4991,5002.7
Exp/Cntr=0.3,0.1

Type RM Length L Ch R = 1,1000,500,500,500
BEGIN DESCRIPTION:
SOUTH WILLOW CREEK 2.0
END DESCRIPTION:
XS GIS Cut Line= 3
      2757755.70     10252703.09      2758322.54     10252038.09
      2758555.68     10251553.12
#Sta/Elev= 30
  4126.2 1194.04  4190.4 1192.98  4260.7 1189.50  4310.1 1188.55  4459.4 1181.77
  4467.1 1182.09  4536.0 1177.69  4649.2 1173.18  4764.7 1168.41  4814.1 1168.26
  4828.4 1168.62  4835.7 1170.41  4858.3 1170.41  4906.3 1170.41  4941.4 1168.94
  4984.3 1165.27  4992.0 1162.16  4999.6 1161.17  5000.1 1160.67  5011.4 1161.17
  5014.9 1162.36  5027.7 1163.61  5046.7 1164.10  5065.8 1163.06  5072.1 1163.58
  5082.8 1169.10  5094.3 1170.12  5297.7 1181.10  5410.8 1190.81  5538.1 1199.09
#Mann=7,-1,0
  4126.2    0.05       0  4536.0    0.12       0  4649.2    0.05       0
  4858.3    0.12       0  4999.6    0.07       0  5011.4    0.12       0
  5046.7    0.05       0
Bank Sta=4999.6,5011.4
Exp/Cntr=0.3,0.1

Type RM Length L Ch R = 1,500,0,0,0
BEGIN DESCRIPTION:
SOUTH WILLOW CREEK 1.0
END DESCRIPTION:
XS GIS Cut Line= 3
      2758355.70     10252703.09      2758712.27     10252311.10
      2759105.67     10251953.12
#Sta/Elev= 30
  4470.1 1181.38  4618.8 1176.77  4640.0 1175.48  4725.2 1173.89  4767.5 1170.65
  4788.7 1170.95  4795.4 1169.54  4831.2 1168.03  4958.3 1166.96  4965.7 1165.95
  4980.8 1158.94  4981.3 1158.44  4992.6 1158.94  5029.5 1159.87  5050.5 1161.94
  5093.0 1163.07  5128.2 1166.52  5156.6 1168.05  5178.2 1165.55  5184.9 1165.54
  5284.3 1174.28  5291.0 1174.05  5319.4 1176.70  5333.6 1177.16  5362.0 1179.83
  5369.4 1181.42  5425.5 1185.31  5447.1 1187.69  5461.3 1186.95  5531.9 1189.30
#Mann=3,-1,0
  4470.1    0.05       0  4980.8    0.05       0  4992.6    0.05       0
Bank Sta=4980.8,4992.6
Exp/Cntr=0.3,0.1

Chan Stop Cuts=-1