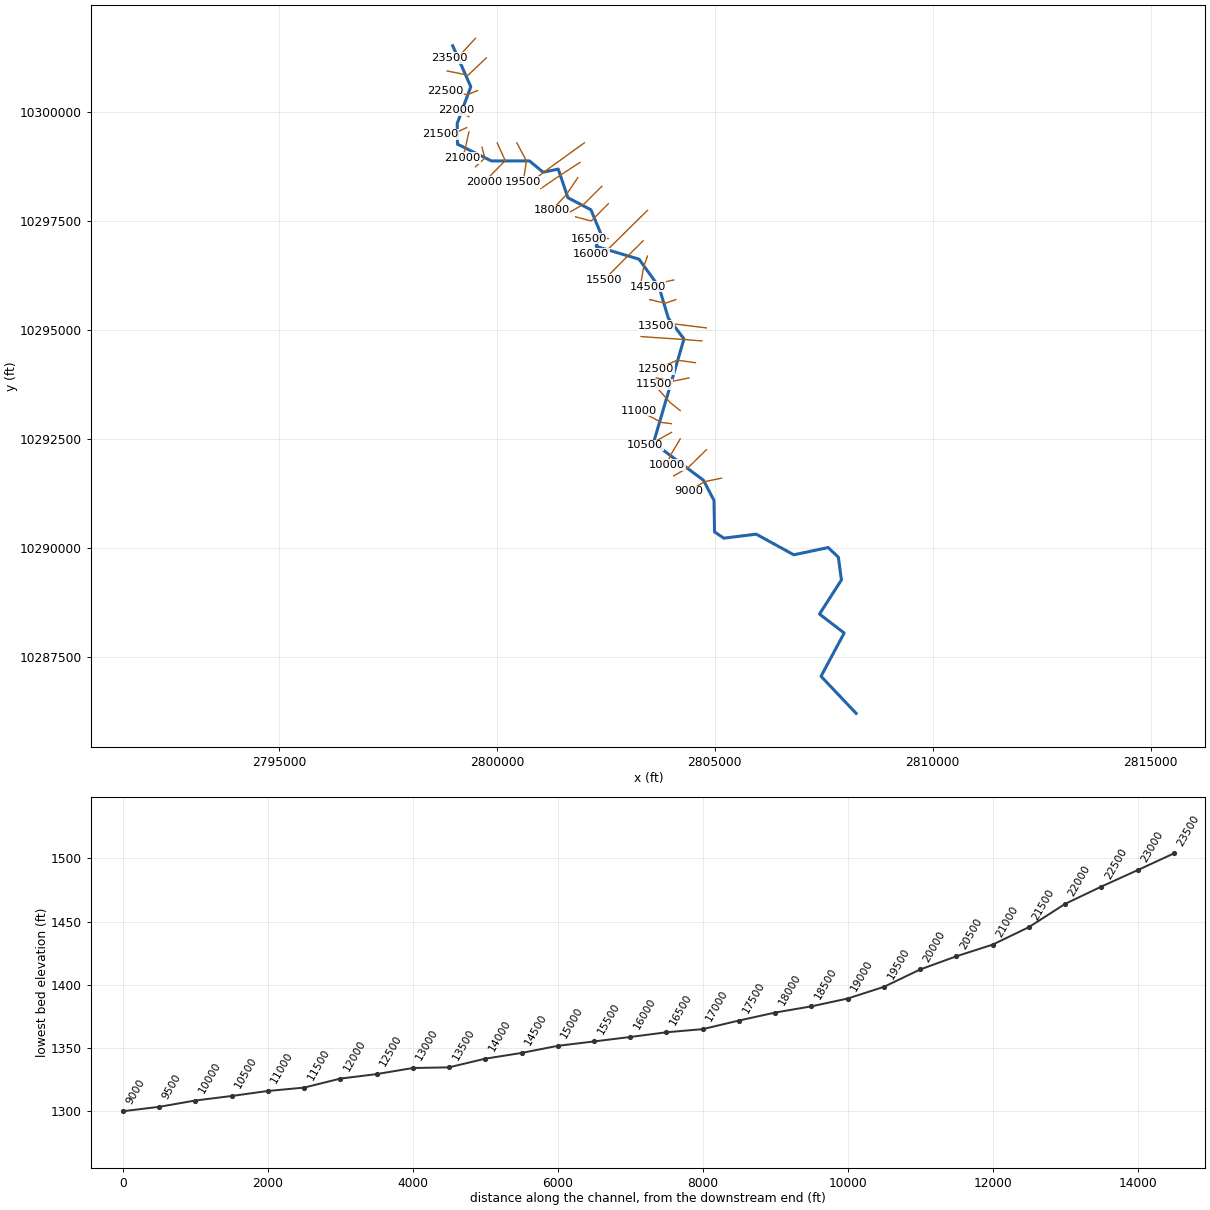
--- WOLF CREEK.prj (project) ---

Proj Title=WOLF CREEK Base Level Engineering
Current Plan=p01
Default Exp/Contr=0.3,0.1
English Units
Geom File=g01
Flow File=f01
Plan File=p01
BEGIN DESCRIPTION:
WOLF CREEK
END DESCRIPTION:

--- WOLF CREEK.p01 (plan) ---

Plan Title=Multiple Run
Short Identifier=Multiple
Geom File=g01
Flow File=f01
Subcritical Flow
K Sum by GR= 0
Std Step Tol= 0.01
Critical Tol= 0.01
Num of Std Step Trials= 20
Max Error Tol= 0.3
Flow Tol Ratio= 0.001
Split Flow NTrial= 30
Split Flow Tol= 0.02
Split Flow Ratio= 0.02
Log Output Level= 0
Friction Slope Method= 1
Unsteady Friction Slope Method= 2
Unsteady Bridges Friction Slope Method= 1
Parabolic Critical Depth
Global Vel Dist=  1 , 1 , 1
Global Log Level= 0
CheckData=True
Encroach Param= -1, 0, 0, 0
BEGIN DESCRIPTION:
Multiple Run
END DESCRIPTION:

--- WOLF CREEK.f01 (steady flow) ---

Flow Title=Multiple
Number of Profiles=7
Profile Names=10-year,25-year,50-year,1pct_min,100-year,1pct_plu,500-year
River Rch & RM= WOLF CREEK,Reach-1,23500
     209     323     580     390     785    1581    1133
River Rch & RM= WOLF CREEK,Reach-1,18500
     561     913    1836    1134    2568    5816    3649
River Rch & RM= WOLF CREEK,Reach-1,15000
     655    1080    2130    1419    2990    6298    4239
River Rch & RM= WOLF CREEK,Reach-1,13000
     786    1307    2653    1575    3747    8917    5297
River Rch & RM= WOLF CREEK,Reach-1,12000
    1129    1938    3621    2791    5146    9489    7246
River Rch & RM= WOLF CREEK,Reach-1,4500
    1367    2383    4461    3463    6391   11798    9021
Boundary for River Rch & Prof#=WOLF CREEK,Reach-1,1
Up Type=0
Dn Type=3
Dn Slope=0.005
Boundary for River Rch & Prof#=WOLF CREEK,Reach-1,2
Up Type=0
Dn Type=3
Dn Slope=0.005
Boundary for River Rch & Prof#=WOLF CREEK,Reach-1,3
Up Type=0
Dn Type=3
Dn Slope=0.005
Boundary for River Rch & Prof#=WOLF CREEK,Reach-1,4
Up Type=0
Dn Type=3
Dn Slope=0.005
Boundary for River Rch & Prof#=WOLF CREEK,Reach-1,5
Up Type=0
Dn Type=3
Dn Slope=0.005
Boundary for River Rch & Prof#=WOLF CREEK,Reach-1,6
Up Type=0
Dn Type=3
Dn Slope=0.005
Boundary for River Rch & Prof#=WOLF CREEK,Reach-1,7
Up Type=0
Dn Type=3
Dn Slope=0.005

--- WOLF CREEK.g01 (geometry) ---

Geom Title=Existing Conditions

River Reach=WOLF CREEK,Reach-1
Reach XY= 30
      2798984.00     10301532.00      2799399.25     10300592.00
      2799087.75     10299746.00      2799093.75     10299272.00
      2799876.25     10298886.00      2800747.00     10298887.00
      2801059.50     10298628.00      2801406.25     10298700.00
      2801629.00     10298042.00      2802156.75     10297765.00
      2802375.50     10297239.00      2802278.25     10296924.00
      2803261.00     10296631.00      2803717.75     10295997.00
      2803934.50     10295272.00      2804292.25     10294799.00
      2803592.50     10292412.00      2804740.25     10291553.00
      2804981.50     10291089.00      2804993.75     10290367.00
      2805207.25     10290223.00      2805950.25     10290315.00
      2806813.00     10289841.00      2807602.25     10290008.00
      2807835.75     10289785.00      2807906.00     10289263.00
      2807402.50     10288480.00      2807969.25     10288045.00
      2807438.00     10287051.00      2808243.75     10286199.00

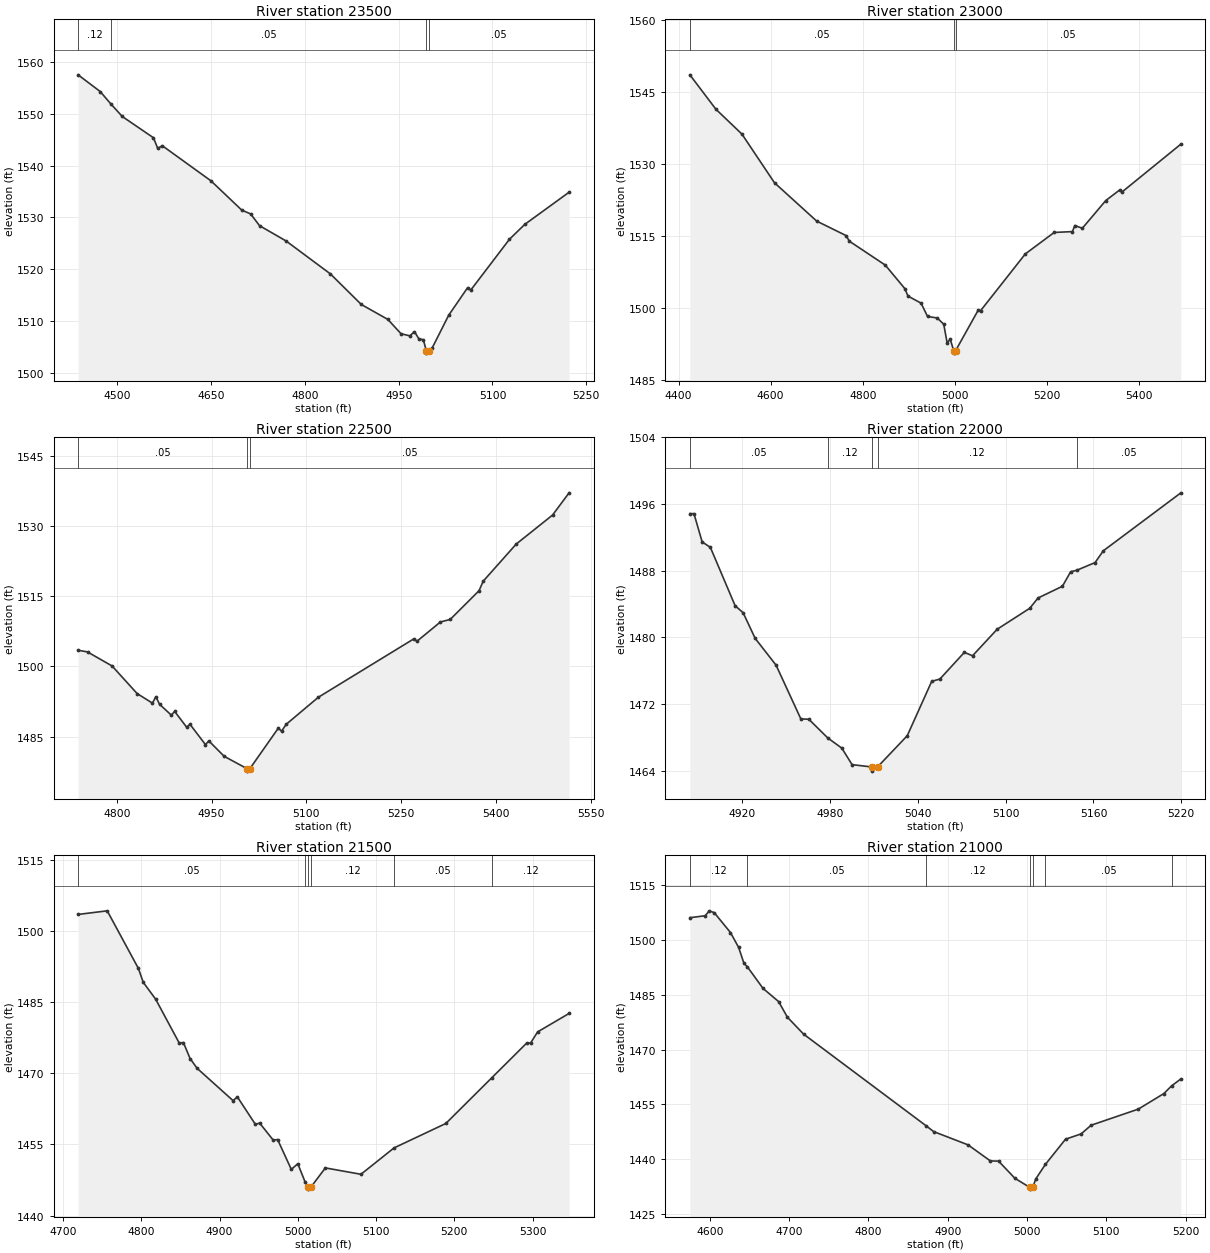
Type RM Length L Ch R = 1,23500,500,500,500
BEGIN DESCRIPTION:
WOLF CREEK 47.0
END DESCRIPTION:
XS GIS Cut Line= 3
      2799505.65     10301703.08      2799125.35     10301288.49
      2798905.68     10301253.11
#Sta/Elev= 30
  4437.4 1557.52  4472.8 1554.29  4490.3 1551.83  4508.0 1549.48  4557.9 1545.37
  4564.7 1543.33  4572.1 1543.83  4649.8 1537.06  4699.1 1531.40  4713.3 1530.67
  4727.5 1528.40  4770.0 1525.44  4840.9 1519.08  4890.3 1513.18  4932.8 1510.29
  4953.8 1507.53  4967.9 1507.13  4975.3 1507.94  4982.1 1506.58  4989.5 1506.36
  4994.1 1504.29  4994.3 1503.79  4998.1 1504.29  5003.5 1504.77  5030.0 1511.11
  5060.3 1516.43  5065.3 1515.97  5127.2 1525.78  5151.6 1528.64  5222.5 1534.86
#Mann=4,-1,0
  4437.4    0.12       0  4490.3    0.05       0  4994.1    0.05       0
  4998.1    0.05       0
Bank Sta=4994.1,4998.1
Exp/Cntr=0.3,0.1

Type RM Length L Ch R = 1,23000,500,500,500
BEGIN DESCRIPTION:
WOLF CREEK 46.0
END DESCRIPTION:
XS GIS Cut Line= 3
      2799755.70     10301253.12      2799337.49     10300857.63
      2798855.66     10300953.12
#Sta/Elev= 30
  4424.4 1548.64  4480.9 1541.47  4537.5 1536.28  4608.3 1526.12  4700.1 1518.12
  4764.0 1515.10  4770.9 1513.94  4849.0 1508.95  4891.5 1504.04  4898.3 1502.49
  4926.7 1501.02  4940.8 1498.24  4961.9 1497.92  4976.0 1496.62  4983.3 1492.77
  4990.2 1493.47  4997.7 1491.09  4997.9 1490.59  5001.7 1491.09  5050.8 1499.54
  5055.9 1499.42  5153.2 1511.28  5215.9 1515.76  5255.6 1515.94  5260.7 1517.21
  5277.1 1516.64  5328.1 1522.42  5358.1 1524.61  5363.2 1524.19  5491.2 1534.18
#Mann=3,-1,0
  4424.4    0.05       0  4997.7    0.05       0  5001.7    0.05       0
Bank Sta=4997.7,5001.7
Exp/Cntr=0.3,0.1

Type RM Length L Ch R = 1,22500,500,500,500
BEGIN DESCRIPTION:
WOLF CREEK 45.0
END DESCRIPTION:
XS GIS Cut Line= 3
      2799555.70     10300503.12      2799312.75     10300407.20
      2798805.64     10300503.12
#Sta/Elev= 30
  4738.8 1503.47  4753.7 1503.10  4792.6 1500.10  4832.2 1494.20  4856.5 1492.15
  4861.9 1493.52  4867.8 1491.90  4886.3 1489.59  4891.7 1490.37  4910.6 1487.01
  4916.0 1487.61  4940.4 1483.28  4945.8 1484.06  4970.1 1480.77  5006.6 1478.10
  5006.8 1477.60  5010.6 1478.10  5055.8 1486.80  5060.9 1486.14  5068.3 1487.62
  5119.1 1493.40  5270.3 1505.90  5275.4 1505.40  5312.5 1509.52  5327.8 1510.04
  5373.6 1516.21  5380.1 1518.23  5432.4 1526.18  5489.9 1532.38  5516.1 1537.14
#Mann=3,-1,0
  4738.8    0.05       0  5006.6    0.05       0  5010.6    0.05       0
Bank Sta=5006.6,5010.6
Exp/Cntr=0.3,0.1

Type RM Length L Ch R = 1,22000,500,500,500
BEGIN DESCRIPTION:
WOLF CREEK 44.0
END DESCRIPTION:
XS GIS Cut Line= 3
      2799355.66     10299903.12      2799251.91     10299954.32
      2799055.67     10300053.12
#Sta/Elev= 30
  4884.3 1494.83  4887.1 1494.83  4892.7 1491.44  4898.3 1490.79  4915.2 1483.79
  4920.7 1482.94  4928.9 1479.87  4943.2 1476.65  4960.1 1470.21  4965.6 1470.16
  4978.5 1467.92  4988.1 1466.70  4995.1 1464.72  5008.5 1464.44  5008.7 1463.94
  5012.5 1464.44  5032.8 1468.19  5049.5 1474.71  5055.1 1474.99  5071.8 1478.19
  5077.4 1477.78  5094.2 1480.96  5116.5 1483.48  5122.1 1484.71  5138.8 1486.12
  5144.4 1487.86  5148.6 1488.04  5161.1 1488.96  5166.7 1490.37  5219.7 1497.33
#Mann=5,-1,0
  4884.3    0.05       0  4978.5    0.12       0  5008.5    0.07       0
  5012.5    0.12       0  5148.6    0.05       0
Bank Sta=5008.5,5012.5
Exp/Cntr=0.3,0.1

Type RM Length L Ch R = 1,21500,500,500,500
BEGIN DESCRIPTION:
WOLF CREEK 43.0
END DESCRIPTION:
XS GIS Cut Line= 3
      2799305.71     10299653.13      2799050.73     10299535.75
      2798705.67     10299503.11
#Sta/Elev= 30
  4719.3 1503.44  4756.5 1504.20  4796.4 1492.05  4802.5 1489.15  4818.4 1485.58
  4848.4 1476.38  4853.9 1476.43  4862.4 1473.07  4871.4 1471.01  4917.3 1464.21
  4922.8 1464.99  4945.8 1459.21  4951.3 1459.47  4968.7 1455.87  4974.2 1456.01
  4991.7 1449.72  5000.0 1450.91  5009.3 1447.08  5013.1 1446.06  5013.4 1445.56
  5017.1 1446.06  5035.2 1450.03  5080.7 1448.69  5122.9 1454.24  5189.1 1459.39
  5248.2 1469.08  5292.4 1476.33  5297.4 1476.34  5306.4 1478.69  5346.6 1482.58
#Mann=6,-1,0
  4719.3    0.05       0  5009.3    0.12       0  5013.1    0.05       0
  5017.1    0.12       0  5122.9    0.05       0  5248.2    0.12       0
Bank Sta=5013.1,5017.1
Exp/Cntr=0.3,0.1

Type RM Length L Ch R = 1,21000,500,500,500
BEGIN DESCRIPTION:
WOLF CREEK 42.0
END DESCRIPTION:
XS GIS Cut Line= 3
      2799355.69     10299553.16      2799264.18     10299138.13
      2799205.70     10298953.15
#Sta/Elev= 30
  4575.0 1506.15  4594.3 1506.68  4599.5 1508.03  4605.8 1507.51  4626.2 1502.08
  4636.5 1498.00  4643.2 1493.63  4647.5 1492.69  4667.2 1486.78  4686.9 1483.16
  4697.9 1478.90  4718.4 1474.24  4872.7 1449.15  4882.3 1447.54  4925.8 1443.89
  4953.9 1439.49  4964.2 1439.45  4984.7 1434.75  5003.3 1432.27  5003.5 1431.77
  5007.3 1432.27  5011.1 1434.58  5023.3 1438.57  5048.6 1445.45  5068.2 1446.90
  5080.9 1449.28  5140.3 1453.69  5172.6 1457.96  5182.3 1460.07  5194.0 1461.96
#Mann=7,-1,0
  4575.0    0.12       0  4647.5    0.05       0  4872.7    0.12       0
  5003.3    0.07       0  5007.3    0.12       0  5023.3    0.05       0
  5182.3    0.12       0
Bank Sta=5003.3,5007.3
Exp/Cntr=0.3,0.1

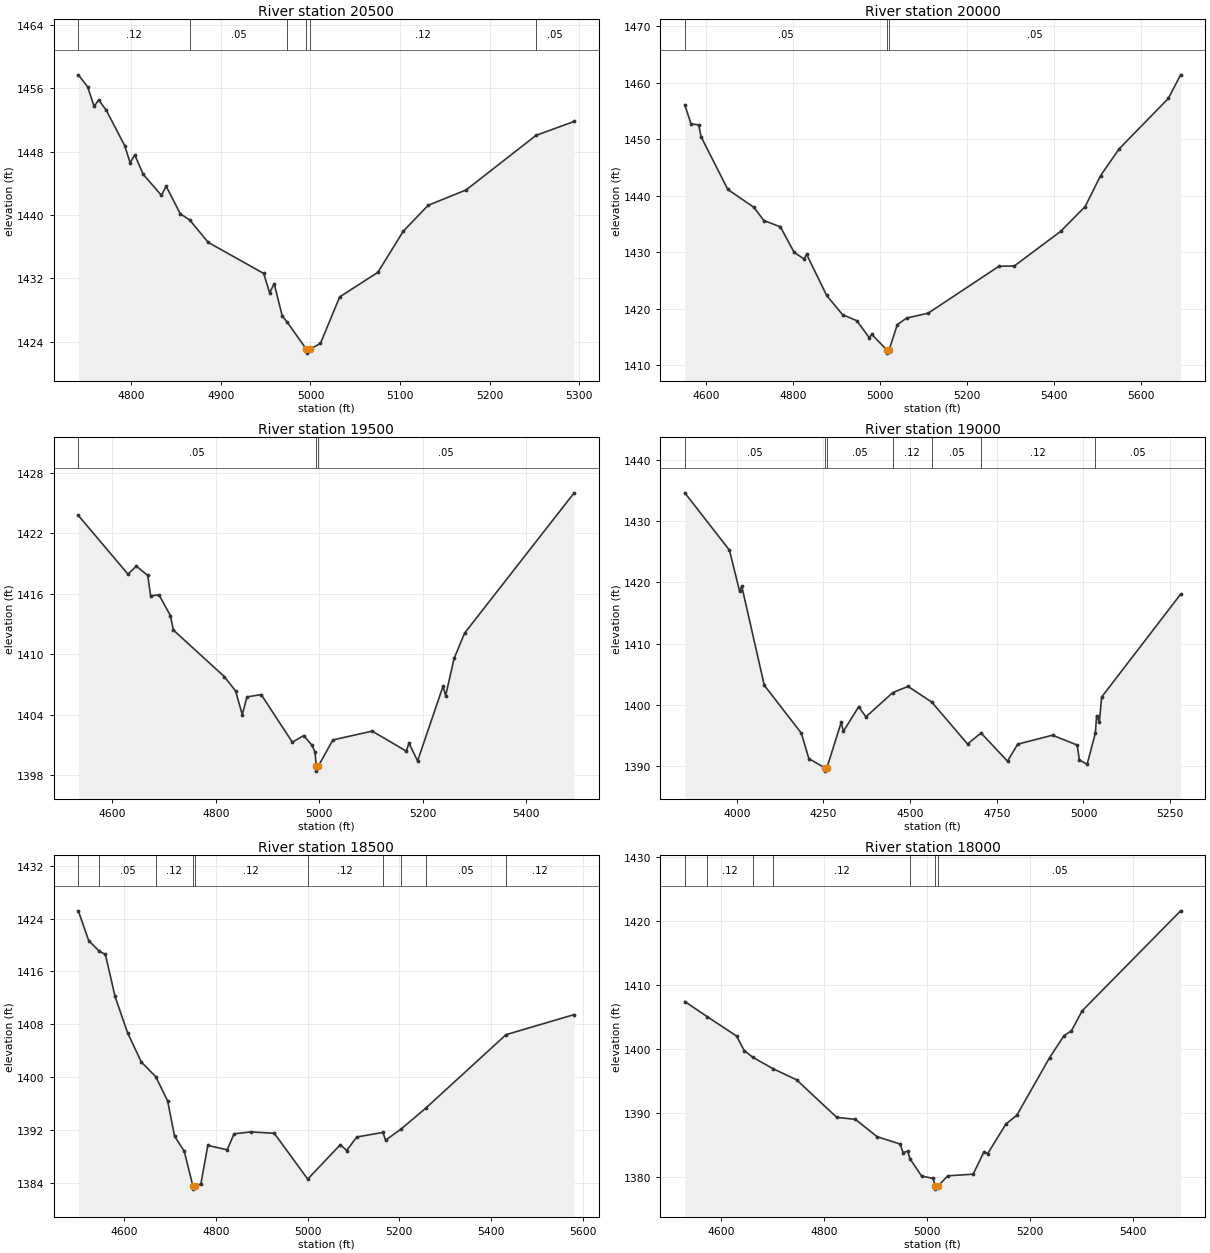
Type RM Length L Ch R = 1,20500,500,500,500
BEGIN DESCRIPTION:
WOLF CREEK 41.0
END DESCRIPTION:
XS GIS Cut Line= 3
      2799655.67     10299203.15      2799722.02     10298952.69
      2799505.71     10298753.14
#Sta/Elev= 30
  4740.9 1457.70  4751.3 1456.19  4758.5 1453.72  4763.6 1454.52  4772.0 1453.24
  4792.7 1448.75  4798.7 1446.60  4803.9 1447.58  4813.4 1445.12  4833.7 1442.48
  4838.9 1443.64  4854.7 1440.15  4865.1 1439.39  4885.8 1436.55  4947.8 1432.62
  4954.4 1430.19  4959.5 1431.32  4968.5 1427.25  4973.9 1426.49  4995.4 1423.06
  4995.6 1422.56  4999.4 1423.06  5011.1 1423.78  5032.6 1429.66  5075.2 1432.76
  5103.5 1437.94  5131.3 1441.22  5173.8 1443.17  5251.8 1450.06  5294.3 1451.81
#Mann=6,-1,0
  4740.9    0.12       0  4865.1    0.05       0  4973.9    0.12       0
  4995.4    0.07       0  4999.4    0.12       0  5251.8    0.05       0
Bank Sta=4995.4,4999.4
Exp/Cntr=0.3,0.1

Type RM Length L Ch R = 1,20000,500,500,500
BEGIN DESCRIPTION:
WOLF CREEK 40.0
END DESCRIPTION:
XS GIS Cut Line= 3
      2800005.67     10299303.13      2800190.32     10298894.52
      2799705.67     10298403.10
#Sta/Elev= 30
  4551.6 1456.08  4565.9 1452.71  4583.6 1452.53  4589.0 1450.43  4650.4 1441.10
  4710.1 1437.95  4733.2 1435.61  4771.1 1434.49  4802.6 1429.98  4825.7 1428.79
  4831.2 1429.65  4877.4 1422.34  4913.8 1418.96  4946.7 1417.87  4975.4 1414.85
  4980.8 1415.47  5016.4 1412.64  5016.6 1412.14  5020.4 1412.64  5039.6 1417.18
  5060.8 1418.34  5110.4 1419.21  5273.0 1427.51  5308.4 1427.57  5414.4 1433.67
  5471.0 1438.08  5506.4 1443.55  5548.8 1448.27  5661.9 1457.21  5690.2 1461.39
#Mann=3,-1,0
  4551.6    0.05       0  5016.4    0.05       0  5020.4    0.05       0
Bank Sta=5016.4,5020.4
Exp/Cntr=0.3,0.1

Type RM Length L Ch R = 1,19500,500,500,500
BEGIN DESCRIPTION:
WOLF CREEK 39.0
END DESCRIPTION:
XS GIS Cut Line= 3
      2800455.70     10299303.08      2800674.77     10298891.67
      2800605.69     10298403.13
#Sta/Elev= 30
  4533.9 1423.75  4629.9 1417.94  4646.2 1418.73  4668.2 1417.81  4673.8 1415.79
  4690.1 1415.88  4712.1 1413.83  4717.8 1412.40  4816.3 1407.80  4838.2 1406.37
  4851.1 1404.03  4860.2 1405.78  4887.8 1406.01  4948.1 1401.29  4970.0 1401.95
  4986.3 1400.98  4992.0 1400.30  4994.3 1398.93  4994.6 1398.43  4998.3 1398.93
  5026.5 1401.52  5102.6 1402.39  5168.6 1400.41  5173.7 1401.21  5190.4 1399.44
  5239.7 1406.84  5244.7 1405.91  5261.1 1409.59  5281.3 1412.09  5493.4 1425.99
#Mann=3,-1,0
  4533.9    0.05       0  4994.3    0.05       0  4998.3    0.05       0
Bank Sta=4994.3,4998.3
Exp/Cntr=0.3,0.1

Type RM Length L Ch R = 1,19000,500,500,500
BEGIN DESCRIPTION:
WOLF CREEK 38.0
END DESCRIPTION:
XS GIS Cut Line= 3
      2802005.68     10299303.11      2801073.81     10298629.06
      2800855.72     10298453.14
#Sta/Elev= 30
  3849.9 1434.58  3978.7 1425.23  4008.1 1418.51  4014.2 1419.36  4079.2 1403.19
  4186.0 1395.39  4207.8 1391.23  4254.8 1389.69  4255.2 1389.19  4259.5 1389.69
  4301.2 1397.15  4307.4 1395.67  4351.5 1399.70  4372.4 1398.04  4449.8 1402.00
  4493.8 1403.01  4562.3 1400.45  4665.5 1393.62  4704.5 1395.41  4780.8 1390.81
  4810.2 1393.59  4910.7 1395.05  4981.9 1393.44  4988.0 1391.03  5010.4 1390.30
  5034.1 1395.35  5038.0 1398.24  5045.9 1397.21  5052.3 1401.27  5280.2 1418.05
#Mann=7,-1,0
  3849.9    0.05       0  4254.8    0.07       0  4259.5    0.05       0
  4449.8    0.12       0  4562.3    0.05       0  4704.5    0.12       0
  5034.1    0.05       0
Bank Sta=4254.8,4259.5
Exp/Cntr=0.3,0.1

Type RM Length L Ch R = 1,18500,500,500,500
BEGIN DESCRIPTION:
WOLF CREEK 37.0
END DESCRIPTION:
XS GIS Cut Line= 3
      2801905.71     10298853.13      2801486.22     10298580.86
      2801005.65     10298253.09
#Sta/Elev= 30
  4499.9 1425.19  4522.6 1420.67  4546.0 1419.04  4558.9 1418.60  4580.0 1412.22
  4607.2 1406.74  4637.4 1402.28  4668.8 1400.06  4694.7 1396.41  4709.9 1391.04
  4731.0 1388.78  4749.7 1383.53  4750.1 1383.03  4754.4 1383.53  4767.2 1383.80
  4782.4 1389.65  4824.6 1388.99  4839.7 1391.41  4876.0 1391.70  4927.4 1391.49
  5000.4 1384.55  5071.5 1389.76  5085.4 1388.88  5107.4 1390.93  5164.2 1391.62
  5170.4 1390.45  5204.6 1392.16  5257.6 1395.28  5433.1 1406.43  5581.7 1409.47
#Mann=10,-1,0
  4499.9    0.12       0  4546.0    0.05       0  4668.8    0.12       0
  4749.7    0.05       0  4754.4    0.12       0  5000.4    0.12       0
  5164.2    0.05       0  5204.6    0.12       0  5257.6    0.05       0
  5433.1    0.12       0
Bank Sta=4749.7,4754.4
Exp/Cntr=0.3,0.1

Type RM Length L Ch R = 1,18000,500,500,500
BEGIN DESCRIPTION:
WOLF CREEK 36.0
END DESCRIPTION:
XS GIS Cut Line= 3
      2801855.71     10298503.15      2801592.35     10298112.42
      2801255.67     10297753.10
#Sta/Elev= 30
  4528.8 1407.43  4572.4 1405.06  4629.3 1402.04  4644.3 1399.77  4660.4 1398.74
  4700.7 1396.91  4745.9 1395.20  4824.2 1389.32  4860.2 1389.02  4902.7 1386.30
  4947.1 1385.16  4953.1 1383.82  4962.1 1384.04  4966.3 1382.86  4989.1 1380.15
  5011.5 1379.78  5015.5 1378.61  5016.0 1378.11  5021.1 1378.61  5039.8 1380.19
  5089.2 1380.45  5110.2 1383.93  5117.5 1383.66  5152.7 1388.27  5174.1 1389.66
  5237.7 1398.65  5266.0 1402.11  5280.1 1402.84  5301.2 1405.99  5492.4 1421.60
#Mann=7,-1,0
  4528.8    0.05       0  4572.4    0.12       0  4660.4    0.05       0
  4700.7    0.12       0  4966.3    0.05       0  5015.5    0.05       0
  5021.1    0.05       0
Bank Sta=5015.5,5021.1
Exp/Cntr=0.3,0.1

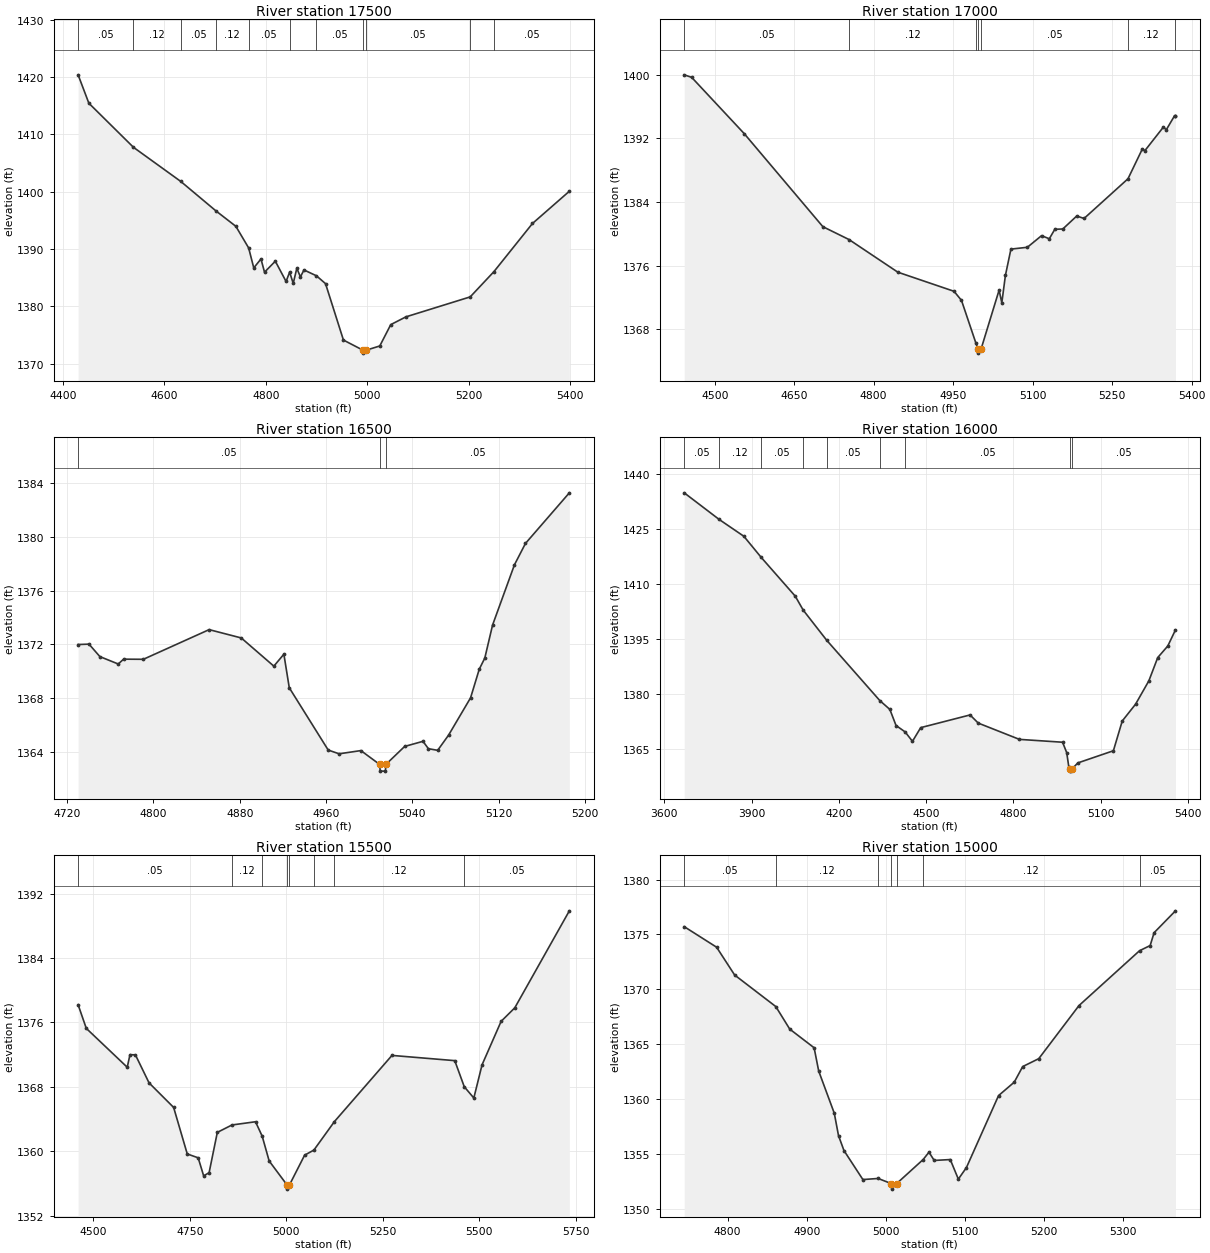
Type RM Length L Ch R = 1,17500,500,500,500
BEGIN DESCRIPTION:
WOLF CREEK 35.0
END DESCRIPTION:
XS GIS Cut Line= 3
      2802405.65     10298303.08      2802001.85     10297900.36
      2801655.70     10297703.12
#Sta/Elev= 30
  4429.7 1420.37  4450.9 1415.42  4538.8 1407.73  4632.2 1401.77  4701.4 1396.64
  4740.8 1393.94  4766.0 1390.17  4776.1 1386.69  4790.3 1388.25  4797.3 1385.94
  4818.6 1387.86  4839.8 1384.32  4846.8 1385.95  4853.9 1383.99  4861.0 1386.62
  4868.1 1385.12  4875.1 1386.33  4899.7 1385.31  4917.6 1383.94  4952.9 1374.10
  4991.7 1372.32  4992.1 1371.82  4997.4 1372.32  5024.6 1373.07  5046.2 1376.79
  5076.2 1378.15  5202.9 1381.63  5249.7 1386.04  5325.7 1394.44  5398.4 1400.06
#Mann=11,-1,0
  4429.7    0.05       0  4538.8    0.12       0  4632.2    0.05       0
  4701.4    0.12       0  4766.0    0.05       0  4846.8    0.12       0
  4899.7    0.05       0  4991.7    0.05       0  4997.4    0.05       0
  5202.9    0.12       0  5249.7    0.05       0
Bank Sta=4991.7,4997.4
Exp/Cntr=0.3,0.1

Type RM Length L Ch R = 1,17000,500,500,500
BEGIN DESCRIPTION:
WOLF CREEK 34.0
END DESCRIPTION:
XS GIS Cut Line= 3
      2802555.69     10297903.11      2802162.66     10297507.72
      2801805.69     10297603.11
#Sta/Elev= 30
  4442.5 1399.99  4456.6 1399.67  4555.6 1392.61  4704.1 1380.91  4753.5 1379.29
  4845.6 1375.19  4951.6 1372.79  4965.7 1371.65  4993.1 1366.24  4996.9 1365.52
  4997.3 1365.02  5002.6 1365.52  5036.7 1372.94  5041.8 1371.34  5048.6 1374.79
  5059.0 1378.09  5090.0 1378.32  5116.8 1379.78  5131.4 1379.39  5141.8 1380.58
  5156.9 1380.62  5183.2 1382.25  5197.0 1381.94  5279.9 1386.93  5306.8 1390.65
  5312.0 1390.48  5346.9 1393.44  5352.1 1393.08  5367.8 1394.85  5369.5 1394.85
#Mann=7,-1,0
  4442.5    0.05       0  4753.5    0.12       0  4993.1    0.05       0
  4996.9    0.05       0  5002.6    0.05       0  5279.9    0.12       0
  5367.8    0.05       0
Bank Sta=4996.9,5002.6
Exp/Cntr=0.3,0.1

Type RM Length L Ch R = 1,16500,500,500,500
BEGIN DESCRIPTION:
WOLF CREEK 33.0
END DESCRIPTION:
XS GIS Cut Line= 3
      2802555.71     10297103.11      2802288.04     10297137.72
      2802105.69     10297103.11
#Sta/Elev= 30
  4730.1 1371.98  4740.2 1372.01  4750.3 1371.08  4767.3 1370.53  4772.3 1370.89
  4790.6 1370.88  4851.6 1373.09  4881.4 1372.47  4911.6 1370.37  4920.9 1371.26
  4925.9 1368.76  4962.0 1364.12  4972.1 1363.84  4992.3 1364.08  5009.7 1363.05
  5010.2 1362.55  5015.0 1362.55  5015.5 1363.05  5032.9 1364.39  5049.9 1364.77
  5054.9 1364.22  5063.5 1364.10  5073.6 1365.23  5094.0 1368.01  5102.1 1370.15
  5107.2 1370.97  5114.4 1373.43  5134.7 1377.92  5144.9 1379.51  5185.6 1383.28
#Mann=3,-1,0
  4730.1    0.05       0  5009.7    0.05       0  5015.5    0.05       0
Bank Sta=5009.7,5015.5
Exp/Cntr=0.3,0.1

Type RM Length L Ch R = 1,16000,500,500,500
BEGIN DESCRIPTION:
WOLF CREEK 32.0
END DESCRIPTION:
XS GIS Cut Line= 3
      2803455.67     10297753.10      2802507.54     10296818.26
      2802155.72     10296753.12
#Sta/Elev= 30
  3668.5 1434.90  3788.5 1427.63  3873.6 1423.02  3933.3 1417.24  4050.3 1406.65
  4077.8 1402.82  4158.4 1394.60  4340.9 1378.12  4375.6 1375.69  4396.9 1371.29
  4428.0 1369.55  4453.4 1366.97  4481.7 1370.71  4651.4 1374.18  4679.6 1371.95
  4821.1 1367.50  4969.6 1366.72  4983.8 1363.87  4990.8 1360.08  4994.9 1359.32
  4995.4 1358.82  5000.7 1359.32  5022.2 1361.07  5144.3 1364.39  5174.8 1372.53
  5220.5 1377.11  5266.3 1383.51  5296.8 1389.86  5331.4 1393.03  5357.8 1397.43
#Mann=9,-1,0
  3668.5    0.05       0  3788.5    0.12       0  3933.3    0.05       0
  4077.8    0.12       0  4158.4    0.05       0  4340.9    0.12       0
  4428.0    0.05       0  4994.9    0.03       0  5000.7    0.05       0
Bank Sta=4994.9,5000.7
Exp/Cntr=0.3,0.1

Type RM Length L Ch R = 1,15500,500,500,500
BEGIN DESCRIPTION:
WOLF CREEK 31.0
END DESCRIPTION:
XS GIS Cut Line= 3
      2803355.70     10297053.13      2802972.02     10296674.28
      2802455.71     10296153.13
#Sta/Elev= 30
  4460.8 1378.21  4482.0 1375.27  4588.1 1370.44  4595.2 1372.00  4609.3 1371.98
  4644.6 1368.50  4708.3 1365.45  4743.6 1359.67  4771.9 1359.19  4786.1 1356.95
  4800.2 1357.34  4821.5 1362.35  4859.5 1363.27  4920.5 1363.67  4937.8 1361.87
  4955.8 1358.80  5002.4 1355.80  5002.8 1355.30  5008.2 1355.80  5047.7 1359.52
  5071.7 1360.15  5124.9 1363.69  5274.0 1371.91  5436.7 1371.26  5461.3 1368.02
  5486.1 1366.62  5507.4 1370.74  5556.8 1376.14  5592.2 1377.82  5733.6 1389.87
#Mann=8,-1,0
  4460.8    0.05       0  4859.5    0.12       0  4937.8    0.05       0
  5002.4    0.05       0  5008.2    0.05       0  5071.7    0.05       0
  5124.9    0.12       0  5461.3    0.05       0
Bank Sta=5002.4,5008.2
Exp/Cntr=0.3,0.1

Type RM Length L Ch R = 1,15000,500,500,500
BEGIN DESCRIPTION:
WOLF CREEK 30.0
END DESCRIPTION:
XS GIS Cut Line= 3
      2803455.69     10296703.13      2803369.98     10296463.18
      2803305.68     10296103.08
#Sta/Elev= 30
  4745.2 1375.71  4786.1 1373.84  4808.9 1371.31  4860.9 1368.44  4878.5 1366.39
  4909.3 1364.69  4915.1 1362.57  4934.8 1358.73  4940.1 1356.70  4947.0 1355.34
  4970.9 1352.70  4990.2 1352.80  5006.9 1352.33  5007.4 1351.83  5013.5 1352.33
  5047.0 1354.52  5054.4 1355.19  5061.0 1354.44  5081.3 1354.52  5091.5 1352.74
  5101.7 1353.79  5142.3 1360.34  5162.1 1361.56  5172.8 1362.98  5193.1 1363.70
  5243.9 1368.53  5320.4 1373.52  5333.8 1373.99  5338.8 1375.16  5365.8 1377.15
#Mann=7,-1,0
  4745.2    0.05       0  4860.9    0.12       0  4990.2    0.05       0
  5006.9    0.05       0  5013.5    0.05       0  5047.0    0.12       0
  5320.4    0.05       0
Bank Sta=5006.9,5013.5
Exp/Cntr=0.3,0.1

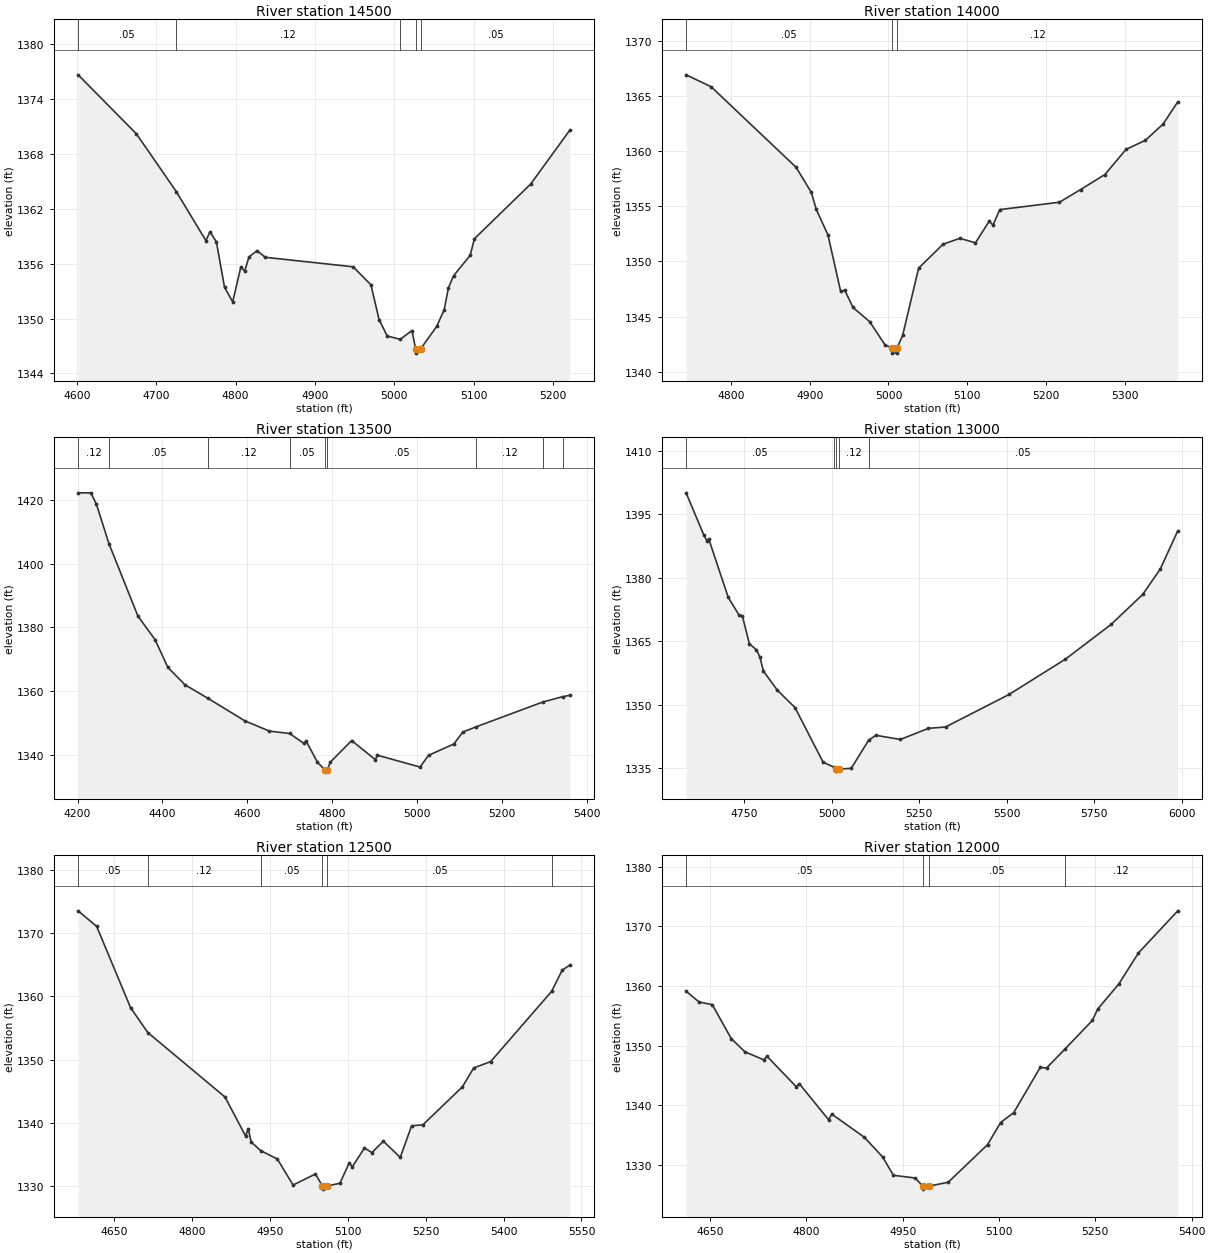
Type RM Length L Ch R = 1,14500,500,500,500
BEGIN DESCRIPTION:
WOLF CREEK 29.0
END DESCRIPTION:
XS GIS Cut Line= 3
      2804055.73     10296153.12      2803666.82     10296067.62
      2803455.65     10296003.10
#Sta/Elev= 30
  4601.8 1376.68  4675.2 1370.22  4725.3 1363.91  4762.7 1358.53  4767.8 1359.51
  4775.9 1358.39  4786.1 1353.44  4796.4 1351.83  4806.5 1355.60  4811.6 1355.23
  4816.9 1356.75  4827.1 1357.44  4837.3 1356.71  4948.0 1355.67  4970.4 1353.70
  4980.7 1349.89  4990.9 1348.10  5007.3 1347.73  5022.1 1348.69  5026.6 1346.72
  5027.1 1346.22  5033.3 1346.72  5053.5 1349.18  5062.7 1350.98  5068.0 1353.36
  5074.4 1354.68  5095.3 1356.91  5100.8 1358.75  5171.6 1364.73  5220.8 1370.62
#Mann=5,-1,0
  4601.8    0.05       0  4725.3    0.12       0  5007.3    0.05       0
  5026.6    0.07       0  5033.3    0.05       0
Bank Sta=5026.6,5033.3
Exp/Cntr=0.3,0.1

Type RM Length L Ch R = 1,14000,500,500,500
BEGIN DESCRIPTION:
WOLF CREEK 28.0
END DESCRIPTION:
XS GIS Cut Line= 3
      2804105.70     10295703.12      2803863.16     10295618.13
      2803505.72     10295703.10
#Sta/Elev= 30
  4743.0 1366.90  4774.8 1365.82  4882.6 1358.53  4902.0 1356.26  4908.3 1354.71
  4923.2 1352.39  4939.3 1347.28  4944.6 1347.38  4954.9 1345.83  4976.1 1344.54
  4996.0 1342.40  5004.2 1342.19  5004.7 1341.69  5010.6 1341.69  5011.1 1342.19
  5018.0 1343.29  5038.3 1349.39  5069.4 1351.56  5090.7 1352.09  5110.5 1351.68
  5127.8 1353.63  5132.9 1353.30  5141.3 1354.69  5217.2 1355.36  5244.1 1356.51
  5274.9 1357.87  5301.6 1360.14  5326.3 1360.97  5348.9 1362.45  5367.4 1364.45
#Mann=3,-1,0
  4743.0    0.05       0  5004.2    0.05       0  5011.1    0.12       0
Bank Sta=5004.2,5011.1
Exp/Cntr=0.3,0.1

Type RM Length L Ch R = 1,13500,500,500,500
BEGIN DESCRIPTION:
WOLF CREEK 27.0
END DESCRIPTION:
XS GIS Cut Line= 3
      2804805.69     10295053.11      2804012.79     10295149.97
      2803655.65     10295103.11
#Sta/Elev= 30
  4201.2 1422.27  4231.4 1422.26  4244.5 1418.62  4273.9 1406.29  4342.2 1383.53
  4382.5 1376.17  4412.8 1367.42  4453.1 1361.97  4507.9 1357.67  4594.1 1350.65
  4652.1 1347.42  4699.7 1346.67  4733.7 1343.53  4738.7 1344.30  4765.4 1337.64
  4782.0 1335.35  4782.5 1334.85  4789.0 1335.35  4795.6 1337.67  4846.0 1344.46
  4901.8 1338.45  4906.8 1339.85  5007.2 1336.13  5027.3 1339.82  5087.0 1343.38
  5108.0 1347.13  5138.7 1348.73  5297.1 1356.59  5343.6 1358.24  5360.2 1358.67
#Mann=9,-1,0
  4201.2    0.12       0  4273.9    0.05       0  4507.9    0.12       0
  4699.7    0.05       0  4782.0    0.03       0  4789.0    0.05       0
  5138.7    0.12       0  5297.1    0.05       0  5343.6    0.12       0
Bank Sta=4782,4789
Exp/Cntr=0.3,0.1

Type RM Length L Ch R = 1,13000,500,500,500
BEGIN DESCRIPTION:
WOLF CREEK 26.0
END DESCRIPTION:
XS GIS Cut Line= 3
      2804705.70     10294753.11      2804291.28     10294785.68
      2803305.68     10294853.11
#Sta/Elev= 30
  4584.3 1400.12  4634.5 1390.21  4643.8 1388.75  4648.8 1389.26  4704.7 1375.38
  4734.8 1371.30  4744.8 1371.05  4764.9 1364.43  4784.9 1363.01  4795.0 1361.31
  4805.0 1357.96  4845.1 1353.42  4895.3 1349.33  4975.5 1336.42  5005.9 1335.27
  5010.9 1334.81  5011.4 1334.31  5020.3 1334.81  5055.7 1334.97  5105.2 1341.59
  5125.9 1342.78  5196.1 1341.80  5276.2 1344.43  5325.0 1344.75  5506.8 1352.46
  5667.2 1360.79  5797.5 1368.99  5887.7 1376.08  5937.8 1382.07  5987.9 1391.13
#Mann=5,-1,0
  4584.3    0.05       0  5005.9    0.12       0  5010.9    0.05       0
  5020.3    0.12       0  5105.2    0.05       0
Bank Sta=5010.9,5020.3
Exp/Cntr=0.3,0.1

Type RM Length L Ch R = 1,12500,500,500,500
BEGIN DESCRIPTION:
WOLF CREEK 25.0
END DESCRIPTION:
XS GIS Cut Line= 3
      2804555.66     10294253.12      2804140.55     10294310.79
      2803655.65     10294103.10
#Sta/Elev= 30
  4580.9 1373.53  4616.7 1371.06  4681.8 1358.22  4715.0 1354.28  4863.6 1344.08
  4903.4 1337.89  4908.4 1339.07  4914.0 1336.96  4932.3 1335.60  4964.5 1334.26
  4994.8 1330.15  5037.9 1331.90  5051.2 1330.00  5051.7 1329.50  5060.6 1330.00
  5084.9 1330.43  5103.1 1333.68  5108.5 1333.00  5132.1 1336.00  5146.7 1335.28
  5168.5 1337.09  5201.1 1334.52  5222.9 1339.52  5244.6 1339.67  5320.8 1345.69
  5342.5 1348.67  5375.2 1349.68  5492.5 1360.79  5513.0 1364.16  5527.5 1364.94
#Mann=6,-1,0
  4580.9    0.05       0  4715.0    0.12       0  4932.3    0.05       0
  5051.2    0.03       0  5060.6    0.05       0  5492.5    0.12       0
Bank Sta=5051.2,5060.6
Exp/Cntr=0.3,0.1

Type RM Length L Ch R = 1,12000,500,500,500
BEGIN DESCRIPTION:
WOLF CREEK 24.0
END DESCRIPTION:
XS GIS Cut Line= 3
      2804405.64     10293903.10      2804026.00     10293825.43
      2803655.66     10293903.12
#Sta/Elev= 30
  4612.5 1359.13  4632.6 1357.33  4653.3 1356.88  4683.0 1351.16  4704.3 1348.96
  4733.5 1347.64  4738.6 1348.22  4784.0 1343.13  4789.1 1343.60  4834.4 1337.59
  4839.5 1338.52  4890.0 1334.66  4918.7 1331.34  4935.4 1328.27  4969.7 1327.81
  4981.0 1326.45  4981.5 1325.95  4990.6 1326.45  5020.8 1327.10  5082.1 1333.41
  5102.5 1337.12  5122.9 1338.78  5164.1 1346.35  5174.0 1346.26  5202.3 1349.39
  5245.5 1354.25  5253.6 1356.13  5286.4 1360.32  5317.1 1365.54  5378.4 1372.61
#Mann=4,-1,0
  4612.5    0.05       0  4981.0    0.05       0  4990.6    0.05       0
  5202.3    0.12       0
Bank Sta=4981,4990.6
Exp/Cntr=0.3,0.1

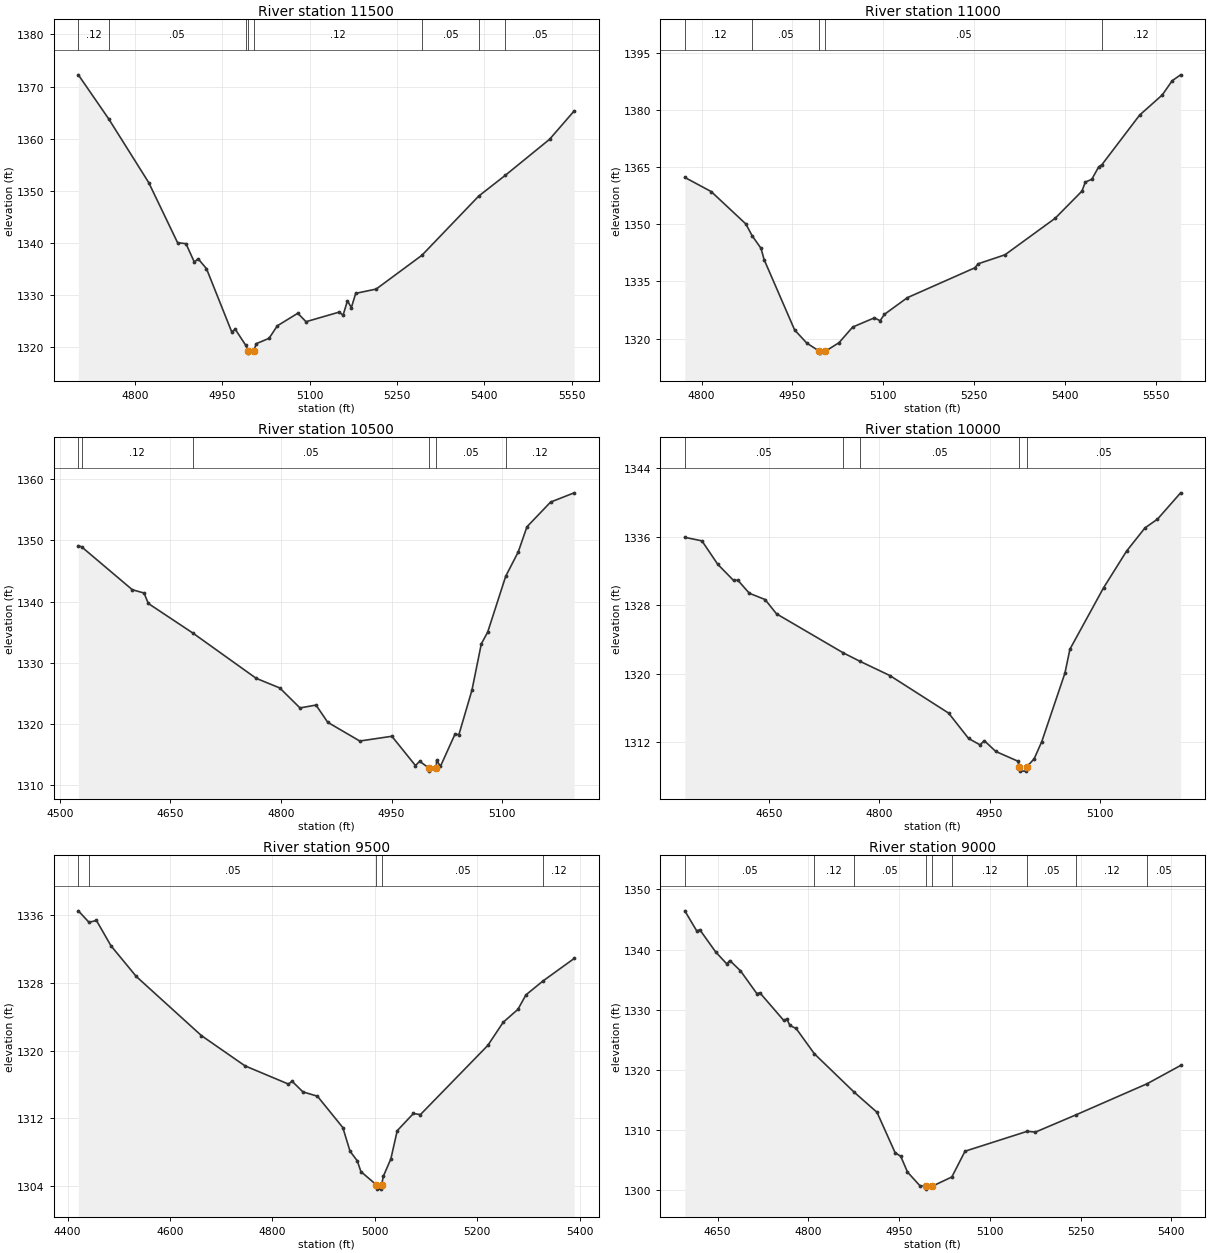
Type RM Length L Ch R = 1,11500,500,500,500
BEGIN DESCRIPTION:
WOLF CREEK 23.0
END DESCRIPTION:
XS GIS Cut Line= 3
      2804205.69     10293153.11      2803974.18     10293339.00
      2803605.70     10293753.09
#Sta/Elev= 30
  4703.1 1372.25  4755.2 1363.80  4823.9 1351.58  4873.5 1340.04  4887.9 1339.85
  4902.3 1336.31  4908.7 1336.96  4923.1 1335.06  4966.3 1322.96  4972.7 1323.40
  4990.5 1320.35  4994.4 1319.35  4994.9 1318.85  5004.2 1319.35  5008.7 1320.67
  5030.5 1321.69  5044.7 1324.09  5079.8 1326.50  5094.0 1324.88  5150.9 1326.72
  5157.6 1326.13  5165.1 1328.89  5171.8 1327.58  5179.3 1330.32  5214.4 1331.14
  5293.0 1337.63  5390.4 1348.98  5436.0 1352.96  5512.1 1359.88  5554.3 1365.32
#Mann=8,-1,0
  4703.1    0.12       0  4755.2    0.05       0  4990.5    0.12       0
  4994.4    0.07       0  5004.2    0.12       0  5293.0    0.05       0
  5390.4    0.12       0  5436.0    0.05       0
Bank Sta=4994.4,5004.2
Exp/Cntr=0.3,0.1

Type RM Length L Ch R = 1,11000,500,500,500
BEGIN DESCRIPTION:
WOLF CREEK 22.0
END DESCRIPTION:
XS GIS Cut Line= 3
      2804005.64     10292853.12      2803779.57     10292880.26
      2803255.67     10293153.12
#Sta/Elev= 30
  4772.3 1362.34  4815.9 1358.61  4873.0 1350.12  4883.5 1347.00  4898.1 1343.71
  4903.2 1340.75  4953.6 1322.26  4973.7 1318.81  4994.5 1316.68  4995.0 1316.18
  5004.4 1316.68  5026.9 1318.93  5049.5 1323.04  5085.4 1325.46  5094.6 1324.68
  5101.9 1326.38  5139.7 1330.75  5251.0 1338.59  5256.6 1339.65  5300.8 1342.01
  5383.6 1351.60  5427.8 1358.73  5433.4 1361.10  5444.1 1361.85  5455.5 1365.11
  5460.9 1365.71  5523.0 1378.70  5560.3 1383.98  5576.8 1387.74  5590.7 1389.28
#Mann=5,-1,0
  4772.3    0.12       0  4883.5    0.05       0  4994.5    0.05       0
  5004.4    0.05       0  5460.9    0.12       0
Bank Sta=4994.5,5004.4
Exp/Cntr=0.3,0.1

Type RM Length L Ch R = 1,10500,500,500,500
BEGIN DESCRIPTION:
WOLF CREEK 21.0
END DESCRIPTION:
XS GIS Cut Line= 3
      2804005.68     10292653.11      2803590.96     10292421.94
      2803405.73     10292353.13
#Sta/Elev= 30
  4525.2 1349.14  4529.6 1348.96  4598.4 1341.93  4614.3 1341.39  4620.1 1339.68
  4680.2 1334.86  4766.4 1327.42  4798.4 1325.84  4825.8 1322.57  4847.5 1323.04
  4863.5 1320.21  4906.9 1317.15  4950.4 1317.93  4982.4 1313.13  4988.1 1313.83
  5000.7 1312.72  5001.2 1312.22  5010.6 1312.72  5011.0 1314.01  5016.3 1313.01
  5036.0 1318.28  5041.3 1318.20  5059.0 1325.48  5071.7 1333.07  5080.3 1334.98
  5104.8 1344.14  5121.8 1348.13  5133.6 1352.24  5165.6 1356.28  5197.6 1357.80
#Mann=6,-1,0
  4525.2    0.05       0  4529.6    0.12       0  4680.2    0.05       0
  5000.7    0.05       0  5010.6    0.05       0  5104.8    0.12       0
Bank Sta=5000.7,5010.6
Exp/Cntr=0.3,0.1

Type RM Length L Ch R = 1,10000,500,500,500
BEGIN DESCRIPTION:
WOLF CREEK 20.0
END DESCRIPTION:
XS GIS Cut Line= 3
      2804205.69     10292503.12      2803969.11     10292103.27
      2803905.67     10291903.08
#Sta/Elev= 30
  4535.4 1335.91  4558.7 1335.50  4580.3 1332.76  4601.7 1330.89  4607.5 1330.92
  4623.2 1329.39  4644.6 1328.66  4660.2 1326.99  4751.0 1322.44  4773.4 1321.47
  4814.3 1319.80  4894.3 1315.42  4921.5 1312.46  4937.1 1311.71  4942.9 1312.20
  4958.6 1310.94  4988.6 1309.81  4990.7 1309.15  4991.2 1308.65  5000.1 1308.65
  5000.6 1309.15  5010.7 1310.08  5021.1 1312.10  5052.6 1320.08  5059.4 1322.87
  5105.1 1330.02  5136.5 1334.31  5161.5 1337.01  5178.5 1338.03  5210.0 1341.10
#Mann=5,-1,0
  4535.4    0.05       0  4751.0    0.12       0  4773.4    0.05       0
  4990.7    0.05       0  5000.6    0.05       0
Bank Sta=4990.7,5000.6
Exp/Cntr=0.3,0.1

Type RM Length L Ch R = 1,9500,500,500,500
BEGIN DESCRIPTION:
WOLF CREEK 19.0
END DESCRIPTION:
XS GIS Cut Line= 3
      2804805.69     10292253.12      2804392.74     10291847.42
      2804055.73     10291653.14
#Sta/Elev= 30
  4421.1 1336.48  4441.9 1335.13  4456.5 1335.34  4484.8 1332.36  4534.2 1328.74
  4661.5 1321.76  4746.4 1318.20  4831.2 1316.05  4838.4 1316.38  4859.5 1315.13
  4887.8 1314.62  4937.4 1310.92  4951.5 1308.13  4965.6 1307.00  4972.7 1305.73
  5003.0 1304.16  5003.5 1303.66  5012.8 1303.66  5013.3 1304.16  5016.3 1305.15
  5031.2 1307.23  5043.6 1310.55  5075.2 1312.58  5088.9 1312.45  5220.3 1320.60
  5250.5 1323.34  5279.2 1324.86  5294.9 1326.57  5328.2 1328.21  5389.0 1330.86
#Mann=5,-1,0
  4421.1    0.12       0  4441.9    0.05       0  5003.0    0.05       0
  5013.3    0.05       0  5328.2    0.12       0
Bank Sta=5003,5013.3
Exp/Cntr=0.3,0.1

Type RM Length L Ch R = 1,9000,500,500,500
BEGIN DESCRIPTION:
WOLF CREEK 18.0
END DESCRIPTION:
XS GIS Cut Line= 3
      2805155.65     10291603.11      2804760.25     10291519.21
      2804405.71     10291303.13
#Sta/Elev= 30
  4595.8 1346.43  4615.5 1343.10  4620.6 1343.29  4646.9 1339.59  4665.1 1337.62
  4670.2 1338.17  4687.8 1336.47  4714.8 1332.69  4719.9 1332.81  4759.3 1328.22
  4764.4 1328.44  4769.6 1327.38  4779.8 1326.88  4810.0 1322.67  4875.8 1316.29
  4913.4 1312.96  4943.3 1306.26  4952.8 1305.62  4963.8 1303.03  4984.2 1300.77
  4994.5 1300.69  4995.0 1300.19  5005.1 1300.69  5037.1 1302.21  5058.9 1306.49
  5161.8 1309.80  5175.1 1309.66  5242.0 1312.52  5360.0 1317.71  5415.2 1320.74
#Mann=9,-1,0
  4595.8    0.05       0  4810.0    0.12       0  4875.8    0.05       0
  4994.5    0.05       0  5005.1    0.05       0  5037.1    0.12       0
  5161.8    0.05       0  5242.0    0.12       0  5360.0    0.05       0
Bank Sta=4994.5,5005.1
Exp/Cntr=0.3,0.1