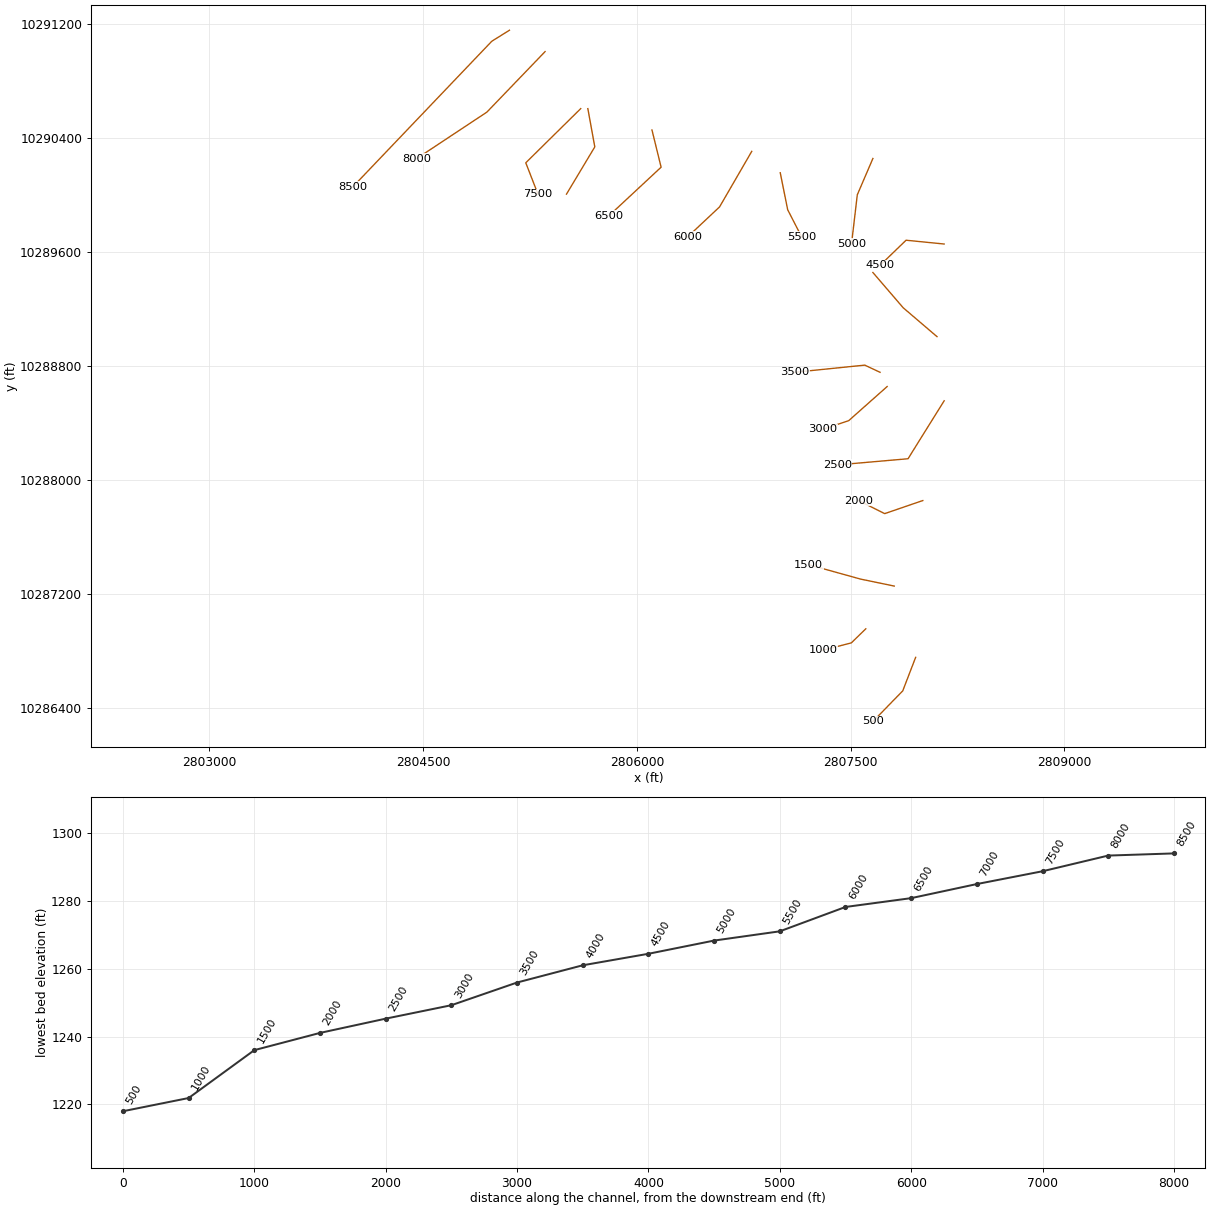
HEC-RAS study WOLF CREEK.prj: WOLF CREEK Base Level Engineering

--- WOLF CREEK.g01 (geometry) --- (continued)

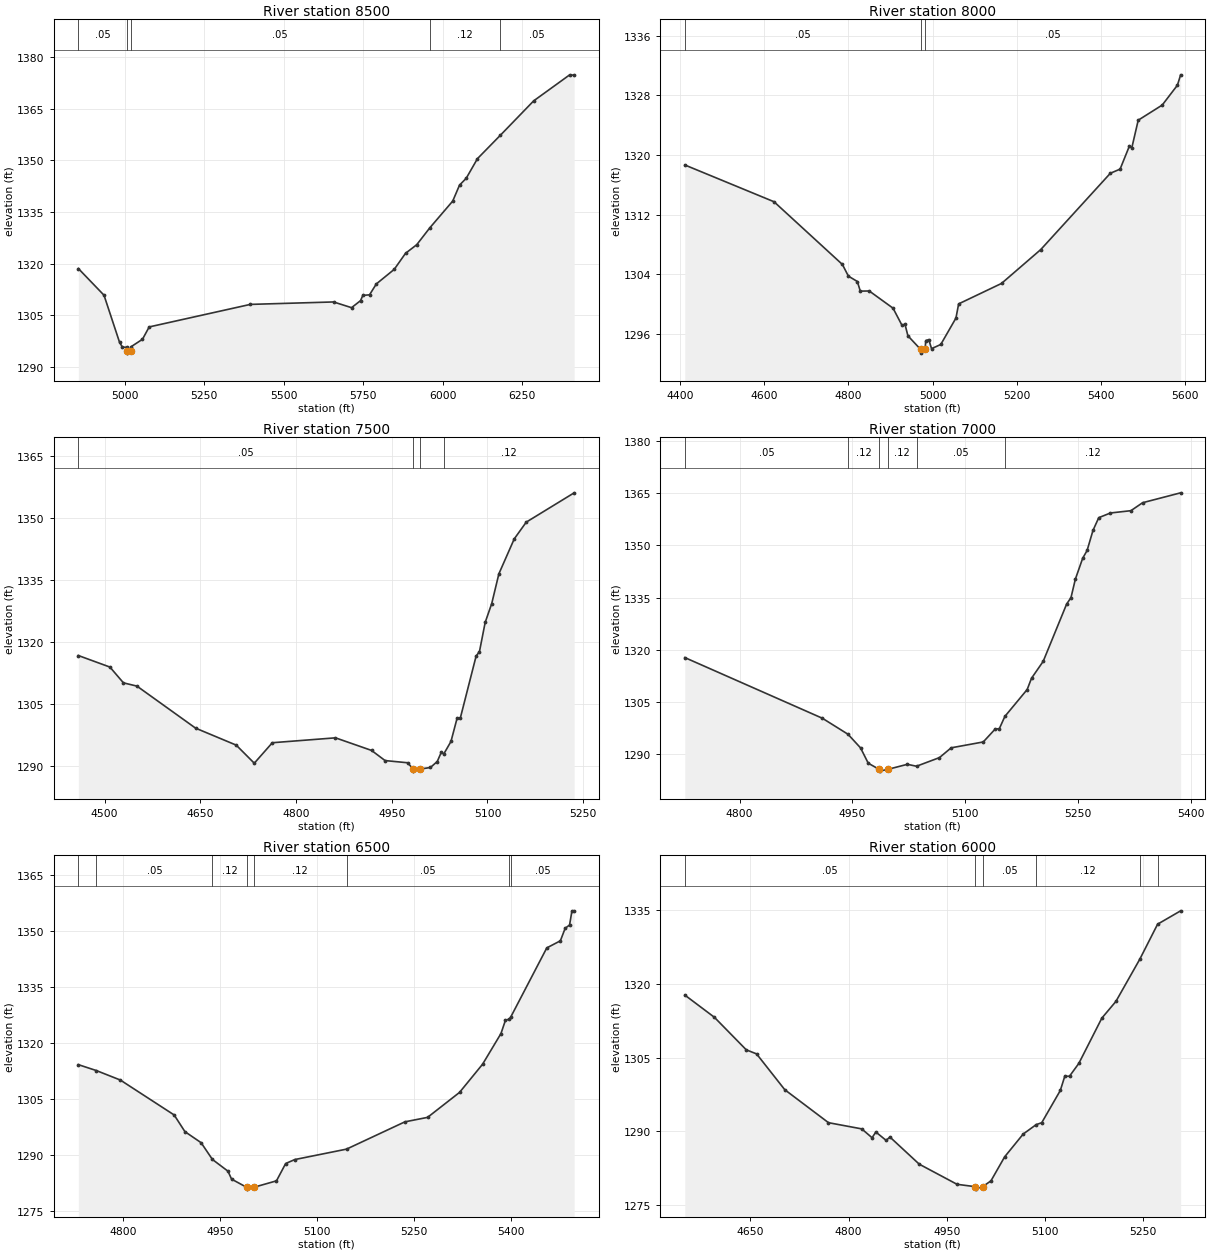
Type RM Length L Ch R = 1,8500,500,500,500
BEGIN DESCRIPTION:
WOLF CREEK 17.0
END DESCRIPTION:
XS GIS Cut Line= 3
      2805105.67     10291153.10      2804981.50     10291075.55
      2804005.66     10290053.09
#Sta/Elev= 30
  4853.6 1318.63  4934.4 1310.88  4983.3 1297.21  4992.2 1295.82  5005.7 1295.77
  5007.7 1294.58  5008.2 1294.08  5018.3 1294.58  5019.9 1295.96  5055.4 1298.10
  5076.5 1301.68  5394.8 1308.22  5656.5 1308.93  5713.1 1307.27  5741.4 1309.31
  5748.6 1310.83  5769.7 1311.00  5791.1 1314.16  5847.4 1318.39  5882.9 1323.04
  5918.2 1325.54  5958.9 1330.39  6031.4 1338.20  6052.8 1342.83  6073.8 1344.81
  6109.2 1350.51  6181.2 1357.29  6286.1 1367.28  6399.4 1374.83  6413.4 1374.71
#Mann=5,-1,0
  4853.6    0.05       0  5007.7    0.05       0  5018.3    0.05       0
  5958.9    0.12       0  6181.2    0.05       0
Bank Sta=5007.7,5018.3
Exp/Cntr=0.3,0.1

Type RM Length L Ch R = 1,8000,500,500,500
BEGIN DESCRIPTION:
WOLF CREEK 16.0
END DESCRIPTION:
XS GIS Cut Line= 3
      2805355.68     10291003.11      2804947.48     10290578.64
      2804455.66     10290253.10
#Sta/Elev= 30
  4411.1 1318.66  4623.2 1313.73  4785.8 1305.32  4800.0 1303.76  4821.3 1303.04
  4828.3 1301.75  4849.6 1301.77  4906.2 1299.46  4927.3 1297.18  4934.5 1297.31
  4941.5 1295.76  4971.7 1293.94  4972.2 1293.44  4982.3 1293.94  4983.9 1295.12
  4991.1 1295.25  4997.7 1294.04  5019.6 1294.60  5055.7 1298.14  5062.1 1300.04
  5164.0 1302.78  5257.3 1307.32  5422.8 1317.55  5445.9 1318.10  5467.9 1321.18
  5473.9 1320.99  5489.0 1324.66  5546.1 1326.69  5582.2 1329.35  5589.8 1330.74
#Mann=3,-1,0
  4411.1    0.05       0  4971.7    0.05       0  4982.3    0.05       0
Bank Sta=4971.7,4982.3
Exp/Cntr=0.3,0.1

Type RM Length L Ch R = 1,7500,500,500,500
BEGIN DESCRIPTION:
WOLF CREEK 15.0
END DESCRIPTION:
XS GIS Cut Line= 3
      2805605.67     10290603.10      2805220.28     10290223.00
      2805305.69     10290003.10
#Sta/Elev= 30
  4458.7 1316.73  4508.2 1313.94  4529.4 1310.13  4550.6 1309.34  4642.5 1299.19
  4706.2 1295.09  4734.5 1290.72  4762.8 1295.67  4861.8 1296.85  4918.3 1293.81
  4939.5 1291.36  4974.9 1290.83  4983.5 1289.31  4984.0 1288.81  4994.6 1289.31
  5010.6 1289.69  5021.3 1291.13  5027.7 1293.39  5031.5 1292.95  5042.8 1295.97
  5052.3 1301.53  5057.6 1301.71  5082.2 1316.58  5087.5 1317.70  5096.4 1324.71
  5106.7 1329.28  5117.9 1336.46  5142.0 1344.90  5160.8 1348.94  5235.9 1356.02
#Mann=4,-1,0
  4458.7    0.05       0  4983.5    0.03       0  4994.6    0.05       0
  5031.5    0.12       0
Bank Sta=4983.5,4994.6
Exp/Cntr=0.3,0.1

Type RM Length L Ch R = 1,7000,500,500,500
BEGIN DESCRIPTION:
WOLF CREEK 14.0
END DESCRIPTION:
XS GIS Cut Line= 3
      2805655.68     10290603.14      2805704.46     10290334.53
      2805505.66     10290003.08
#Sta/Elev= 30
  4727.0 1317.72  4910.0 1300.25  4944.1 1295.64  4960.8 1291.71  4971.0 1287.31
  4985.6 1285.53  4986.1 1285.03  4996.9 1285.53  5023.0 1286.99  5035.2 1286.44
  5065.7 1288.92  5081.3 1291.74  5124.0 1293.43  5139.6 1297.09  5145.4 1297.27
  5152.7 1300.77  5182.4 1308.52  5188.2 1311.78  5203.7 1316.63  5234.8 1333.08
  5240.7 1335.00  5246.5 1340.30  5256.2 1346.29  5262.1 1348.54  5269.9 1354.30
  5277.6 1357.99  5293.2 1359.34  5320.4 1360.00  5335.9 1362.29  5386.5 1365.14
#Mann=6,-1,0
  4727.0    0.05       0  4944.1    0.12       0  4985.6    0.07       0
  4996.9    0.12       0  5035.2    0.05       0  5152.7    0.12       0
Bank Sta=4985.6,4996.9
Exp/Cntr=0.3,0.1

Type RM Length L Ch R = 1,6500,500,500,500
BEGIN DESCRIPTION:
WOLF CREEK 13.0
END DESCRIPTION:
XS GIS Cut Line= 3
      2806105.69     10290453.08      2806169.72     10290192.02
      2805805.67     10289853.10
#Sta/Elev= 30
  4731.2 1314.21  4759.0 1312.63  4796.1 1310.09  4879.3 1300.73  4895.9 1296.27
  4920.9 1293.31  4938.4 1288.82  4962.4 1285.68  4968.0 1283.55  4991.2 1281.37
  4991.7 1280.87  5002.6 1281.37  5037.4 1283.09  5051.6 1287.73  5065.7 1288.79
  5145.6 1291.58  5235.8 1298.89  5270.9 1300.09  5320.3 1306.78  5355.9 1314.33
  5384.3 1322.54  5391.1 1326.04  5397.2 1326.44  5399.1 1326.86  5455.1 1345.48
  5476.1 1347.38  5483.5 1350.73  5490.3 1351.62  5494.0 1355.41  5497.4 1355.41
#Mann=8,-1,0
  4731.2    0.12       0  4759.0    0.05       0  4938.4    0.12       0
  4991.2    0.07       0  5002.6    0.12       0  5145.6    0.05       0
  5397.2    0.12       0  5399.1    0.05       0
Bank Sta=4991.2,5002.6
Exp/Cntr=0.3,0.1

Type RM Length L Ch R = 1,6000,500,500,500
BEGIN DESCRIPTION:
WOLF CREEK 12.0
END DESCRIPTION:
XS GIS Cut Line= 3
      2806805.69     10290303.12      2806579.88     10289913.52
      2806355.66     10289703.09
#Sta/Elev= 30
  4549.7 1317.75  4594.9 1313.23  4643.7 1306.60  4659.4 1305.78  4702.5 1298.49
  4769.3 1291.78  4820.1 1290.52  4835.9 1288.72  4841.7 1289.88  4857.4 1288.18
  4863.2 1288.86  4908.0 1283.34  4965.8 1279.24  4993.5 1278.76  4994.0 1278.26
  5004.9 1278.76  5017.6 1279.94  5038.6 1284.84  5066.9 1289.47  5086.8 1291.39
  5095.2 1291.77  5123.6 1298.33  5130.4 1301.21  5137.7 1301.24  5151.9 1303.84
  5187.1 1313.06  5208.6 1316.46  5245.2 1325.07  5272.3 1332.17  5307.5 1334.89
#Mann=6,-1,0
  4549.7    0.05       0  4993.5    0.05       0  5004.9    0.05       0
  5086.8    0.12       0  5245.2    0.05       0  5272.3    0.12       0
Bank Sta=4993.5,5004.9
Exp/Cntr=0.3,0.1

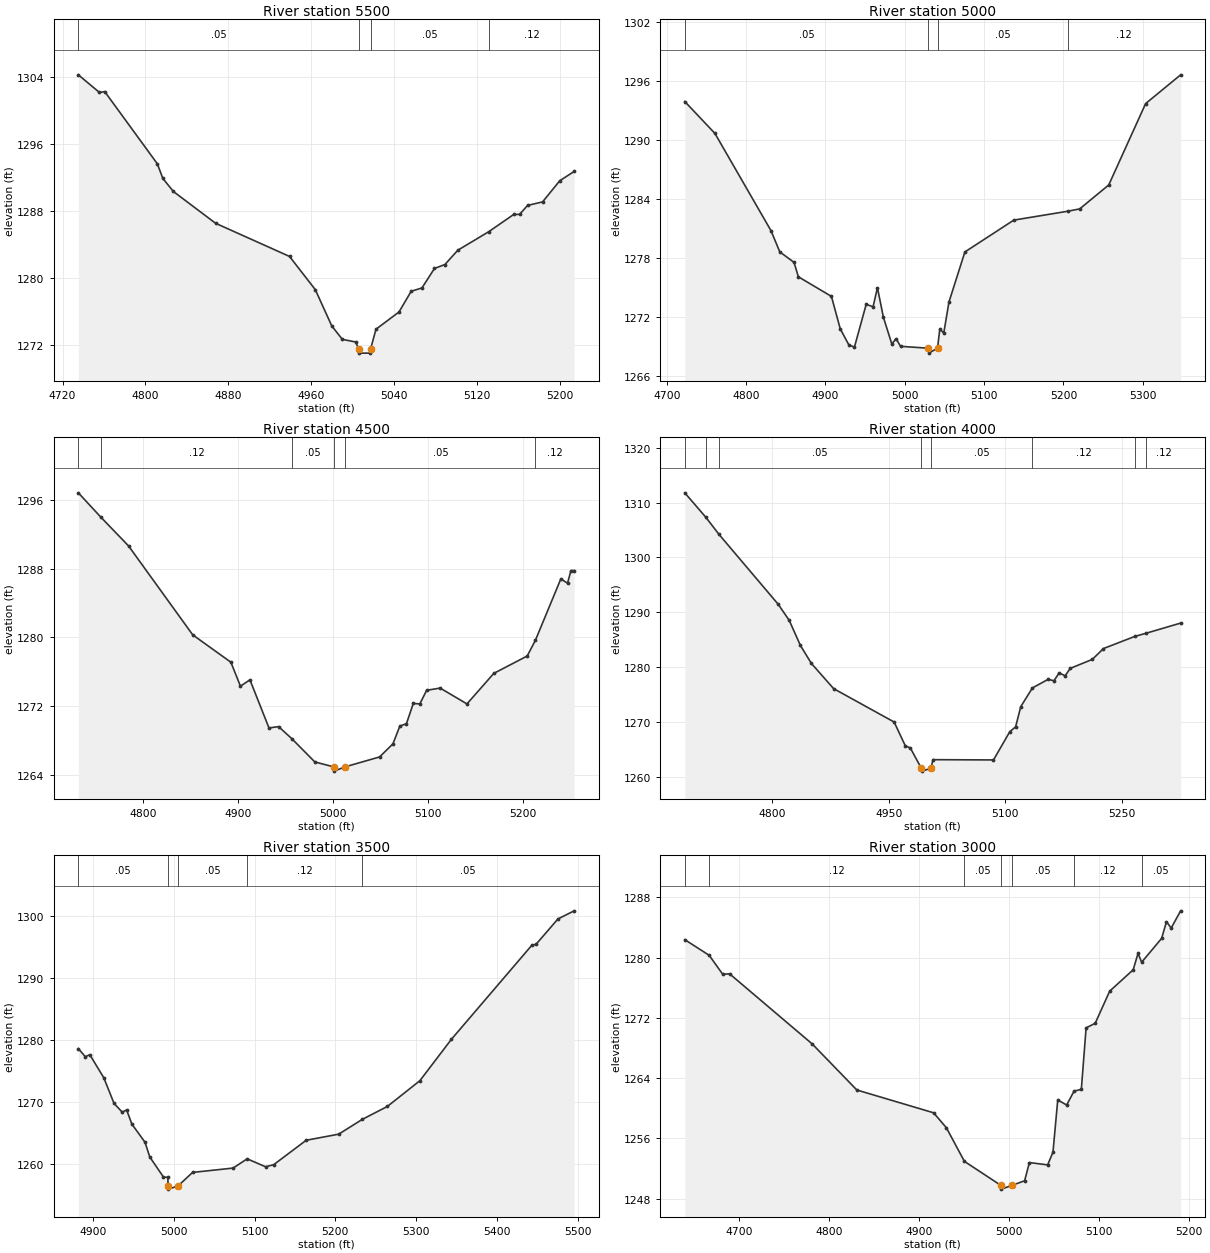
Type RM Length L Ch R = 1,5500,500,500,500
BEGIN DESCRIPTION:
WOLF CREEK 11.0
END DESCRIPTION:
XS GIS Cut Line= 3
      2807005.68     10290153.14      2807057.87     10289893.54
      2807155.69     10289703.09
#Sta/Elev= 30
  4735.2 1304.23  4755.6 1302.13  4760.7 1302.23  4811.5 1293.63  4816.8 1291.89
  4827.0 1290.33  4867.8 1286.54  4939.2 1282.59  4964.1 1278.63  4980.0 1274.31
  4990.2 1272.71  5003.0 1272.40  5006.0 1271.57  5006.5 1271.07  5017.0 1271.07
  5017.5 1271.57  5022.7 1273.92  5044.9 1275.97  5056.7 1278.44  5067.1 1278.84
  5079.2 1281.16  5089.3 1281.63  5101.7 1283.33  5131.5 1285.53  5155.8 1287.60
  5161.4 1287.60  5169.1 1288.67  5183.6 1289.09  5200.2 1291.61  5214.1 1292.72
#Mann=4,-1,0
  4735.2    0.05       0  5006.0    0.03       0  5017.5    0.05       0
  5131.5    0.12       0
Bank Sta=5006,5017.5
Exp/Cntr=0.3,0.1

Type RM Length L Ch R = 1,5000,500,500,500
BEGIN DESCRIPTION:
WOLF CREEK 10.0
END DESCRIPTION:
XS GIS Cut Line= 3
      2807655.68     10290253.11      2807546.26     10289998.41
      2807505.68     10289653.09
#Sta/Elev= 30
  4722.8 1293.88  4760.8 1290.64  4831.5 1280.76  4842.5 1278.62  4860.5 1277.55
  4865.9 1276.09  4907.6 1274.10  4918.7 1270.81  4929.6 1269.17  4936.6 1268.95
  4951.4 1273.29  4960.1 1273.05  4965.6 1274.98  4973.1 1271.98  4983.7 1269.27
  4989.1 1269.81  4994.7 1269.03  5029.8 1268.84  5030.3 1268.34  5041.3 1268.84
  5044.2 1270.78  5049.2 1270.38  5055.7 1273.52  5075.8 1278.61  5137.4 1281.84
  5205.9 1282.75  5220.5 1282.98  5257.1 1285.41  5303.6 1293.67  5347.7 1296.59
#Mann=4,-1,0
  4722.8    0.05       0  5029.8    0.05       0  5041.3    0.05       0
  5205.9    0.12       0
Bank Sta=5029.8,5041.3
Exp/Cntr=0.3,0.1

Type RM Length L Ch R = 1,4500,500,500,500
BEGIN DESCRIPTION:
WOLF CREEK 9.0
END DESCRIPTION:
XS GIS Cut Line= 3
      2808155.71     10289653.11      2807888.43     10289679.72
      2807705.71     10289503.14
#Sta/Elev= 30
  4731.4 1296.81  4755.3 1293.96  4784.3 1290.64  4852.0 1280.29  4892.2 1277.11
  4902.3 1274.32  4912.3 1275.06  4932.4 1269.46  4942.5 1269.62  4956.6 1268.20
  4980.7 1265.51  5000.4 1264.94  5000.9 1264.44  5012.7 1264.94  5049.0 1266.09
  5063.1 1267.62  5070.3 1269.67  5077.3 1269.96  5084.5 1272.31  5091.4 1272.26
  5098.6 1273.84  5112.8 1274.10  5141.1 1272.26  5169.4 1275.81  5204.6 1277.83
  5213.3 1279.67  5240.1 1286.81  5247.1 1286.29  5250.7 1287.76  5254.1 1287.76
#Mann=6,-1,0
  4731.4    0.05       0  4755.3    0.12       0  4956.6    0.05       0
  5000.4    0.05       0  5012.7    0.05       0  5213.3    0.12       0
Bank Sta=5000.4,5012.7
Exp/Cntr=0.3,0.1

Type RM Length L Ch R = 1,4000,500,500,500
BEGIN DESCRIPTION:
WOLF CREEK 8.0
END DESCRIPTION:
XS GIS Cut Line= 3
      2808105.69     10289003.11      2807868.06     10289206.06
      2807655.68     10289453.12
#Sta/Elev= 30
  4687.5 1311.78  4714.3 1307.37  4731.6 1304.19  4807.7 1291.47  4822.0 1288.51
  4836.3 1283.96  4850.5 1280.67  4879.1 1276.08  4957.0 1269.99  4971.3 1265.68
  4977.9 1265.25  4992.1 1261.54  4992.6 1261.04  5004.4 1261.54  5007.0 1263.13
  5084.9 1263.08  5105.8 1268.21  5113.4 1269.12  5120.0 1272.79  5135.0 1276.21
  5155.2 1277.77  5162.8 1277.52  5169.4 1278.95  5177.1 1278.42  5183.7 1279.77
  5212.2 1281.42  5226.5 1283.39  5266.8 1285.60  5281.4 1286.18  5325.8 1288.03
#Mann=8,-1,0
  4687.5    0.05       0  4714.3    0.12       0  4731.6    0.05       0
  4992.1    0.03       0  5004.4    0.05       0  5135.0    0.12       0
  5266.8    0.05       0  5281.4    0.12       0
Bank Sta=4992.1,5004.4
Exp/Cntr=0.3,0.1

Type RM Length L Ch R = 1,3500,500,500,500
BEGIN DESCRIPTION:
WOLF CREEK 7.0
END DESCRIPTION:
XS GIS Cut Line= 3
      2807705.70     10288753.10      2807598.72     10288803.37
      2807105.68     10288753.11
#Sta/Elev= 30
  4881.8 1278.58  4890.5 1277.27  4896.0 1277.60  4913.3 1273.89  4926.0 1269.76
  4936.1 1268.35  4941.6 1268.70  4948.1 1266.42  4964.4 1263.49  4970.2 1261.14
  4987.2 1257.89  4992.7 1257.84  4992.8 1256.45  4993.3 1255.95  5005.1 1256.45
  5023.2 1258.64  5073.4 1259.34  5090.8 1260.83  5113.6 1259.55  5123.7 1259.89
  5163.9 1263.82  5204.1 1264.80  5233.4 1267.19  5264.4 1269.27  5304.6 1273.41
  5343.7 1280.09  5443.3 1295.24  5448.3 1295.36  5475.5 1299.46  5495.6 1300.77
#Mann=5,-1,0
  4881.8    0.05       0  4992.8    0.03       0  5005.1    0.05       0
  5090.8    0.12       0  5233.4    0.05       0
Bank Sta=4992.8,5005.1
Exp/Cntr=0.3,0.1

Type RM Length L Ch R = 1,3000,500,500,500
BEGIN DESCRIPTION:
WOLF CREEK 6.0
END DESCRIPTION:
XS GIS Cut Line= 3
      2807755.66     10288653.09      2807486.26     10288413.85
      2807305.70     10288353.12
#Sta/Elev= 30
  4639.7 1282.39  4666.8 1280.31  4681.9 1277.78  4689.4 1277.86  4781.4 1268.52
  4830.8 1262.42  4916.1 1259.39  4930.3 1257.40  4950.3 1252.94  4990.8 1249.75
  4991.3 1249.25  5003.2 1249.75  5017.2 1250.36  5022.5 1252.78  5042.8 1252.47
  5048.7 1254.16  5054.0 1261.10  5063.9 1260.42  5072.1 1262.27  5080.2 1262.50
  5085.5 1270.67  5095.6 1271.28  5111.7 1275.55  5137.8 1278.39  5143.2 1280.57
  5147.2 1279.39  5169.4 1282.56  5174.8 1284.78  5180.0 1283.93  5190.5 1286.22
#Mann=7,-1,0
  4639.7    0.05       0  4666.8    0.12       0  4950.3    0.05       0
  4990.8    0.05       0  5003.2    0.05       0  5072.1    0.12       0
  5147.2    0.05       0
Bank Sta=4990.8,5003.2
Exp/Cntr=0.3,0.1

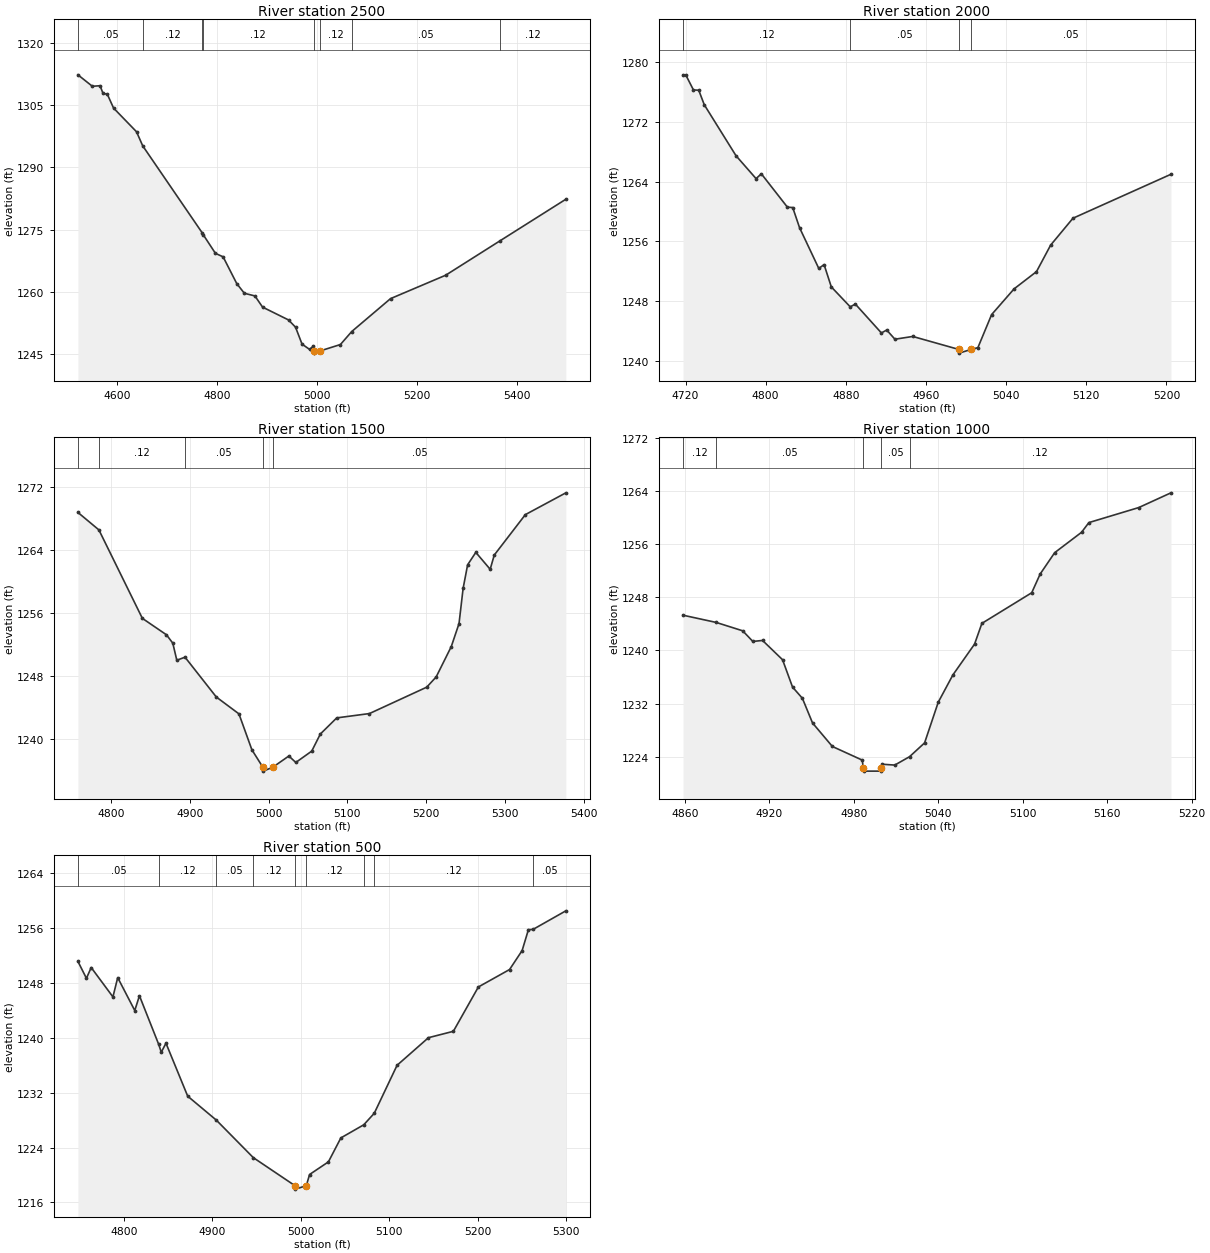
Type RM Length L Ch R = 1,2500,500,500,500
BEGIN DESCRIPTION:
WOLF CREEK 5.0
END DESCRIPTION:
XS GIS Cut Line= 3
      2808155.69     10288553.12      2807902.29     10288146.52
      2807405.68     10288103.11
#Sta/Elev= 30
  4520.9 1312.28  4549.8 1309.52  4565.2 1309.66  4571.1 1307.83  4579.8 1307.60
  4592.3 1304.27  4638.3 1298.57  4650.7 1295.18  4769.6 1274.29  4771.9 1273.79
  4796.4 1269.30  4811.8 1268.46  4839.1 1262.02  4854.3 1259.69  4875.5 1259.05
  4890.8 1256.36  4942.8 1253.27  4956.9 1251.52  4969.9 1247.45  4985.2 1246.16
  4992.2 1246.94  4992.9 1245.78  4993.4 1245.28  5005.3 1245.78  5046.8 1247.35
  5069.5 1250.48  5147.2 1258.40  5257.6 1264.03  5365.9 1272.27  5498.5 1282.33
#Mann=8,-1,0
  4520.9    0.05       0  4650.7    0.12       0  4769.6    0.05       0
  4771.9    0.12       0  4992.9    0.07       0  5005.3    0.12       0
  5069.5    0.05       0  5365.9    0.12       0
Bank Sta=4992.9,5005.3
Exp/Cntr=0.3,0.1

Type RM Length L Ch R = 1,2000,500,500,500
BEGIN DESCRIPTION:
WOLF CREEK 4.0
END DESCRIPTION:
XS GIS Cut Line= 3
      2808005.72     10287853.12      2807738.49     10287761.48
      2807555.67     10287853.12
#Sta/Elev= 30
  4717.5 1278.29  4720.2 1278.29  4727.9 1276.27  4733.2 1276.23  4738.7 1274.29
  4770.4 1267.47  4790.4 1264.41  4795.7 1265.05  4821.7 1260.59  4827.0 1260.54
  4833.8 1257.85  4853.0 1252.40  4858.3 1252.91  4865.5 1249.93  4884.4 1247.26
  4889.5 1247.63  4915.5 1243.77  4920.8 1244.16  4929.0 1242.93  4946.8 1243.30
  4992.6 1241.57  4993.1 1241.07  5005.1 1241.57  5011.8 1241.80  5025.5 1246.22
  5047.9 1249.66  5070.3 1251.97  5084.4 1255.51  5106.7 1259.11  5204.5 1264.99
#Mann=4,-1,0
  4717.5    0.12       0  4884.4    0.05       0  4992.6    0.03       0
  5005.1    0.05       0
Bank Sta=4992.6,5005.1
Exp/Cntr=0.3,0.1

Type RM Length L Ch R = 1,1500,500,500,500
BEGIN DESCRIPTION:
WOLF CREEK 3.0
END DESCRIPTION:
XS GIS Cut Line= 3
      2807805.67     10287253.11      2807569.00     10287302.19
      2807205.66     10287403.12
#Sta/Elev= 30
  4758.3 1268.83  4784.9 1266.61  4840.0 1255.38  4870.6 1253.29  4878.6 1252.23
  4883.7 1250.06  4894.1 1250.45  4933.8 1245.39  4962.5 1243.25  4978.9 1238.69
  4992.8 1236.48  4993.3 1235.98  5005.5 1236.48  5025.8 1237.90  5034.6 1237.08
  5054.8 1238.52  5065.7 1240.69  5086.5 1242.74  5128.0 1243.29  5200.6 1246.64
  5212.6 1247.94  5231.8 1251.80  5241.6 1254.72  5246.8 1259.19  5252.5 1262.18
  5262.9 1263.76  5281.1 1261.61  5286.3 1263.42  5325.7 1268.55  5377.1 1271.32
#Mann=5,-1,0
  4758.3    0.05       0  4784.9    0.12       0  4894.1    0.05       0
  4992.8    0.03       0  5005.5    0.05       0
Bank Sta=4992.8,5005.5
Exp/Cntr=0.3,0.1

Type RM Length L Ch R = 1,1000,500,500,500
BEGIN DESCRIPTION:
WOLF CREEK 2.0
END DESCRIPTION:
XS GIS Cut Line= 3
      2807605.71     10286953.14      2807504.36     10286854.55
      2807305.71     10286803.12
#Sta/Elev= 30
  4858.6 1245.31  4882.2 1244.22  4901.0 1242.96  4908.2 1241.36  4915.1 1241.51
  4929.3 1238.61  4936.4 1234.49  4943.4 1232.80  4950.6 1229.09  4964.7 1225.55
  4985.9 1223.50  4986.7 1222.34  4987.2 1221.84  4998.9 1221.84  4999.4 1222.34
  5000.0 1222.88  5009.0 1222.75  5019.5 1224.01  5030.2 1226.09  5039.9 1232.21
  5050.3 1236.32  5065.7 1240.96  5070.9 1244.08  5106.3 1248.69  5112.3 1251.51
  5122.6 1254.72  5141.7 1257.79  5146.9 1259.25  5182.3 1261.51  5205.2 1263.73
#Mann=5,-1,0
  4858.6    0.12       0  4882.2    0.05       0  4986.7    0.05       0
  4999.4    0.05       0  5019.5    0.12       0
Bank Sta=4986.7,4999.4
Exp/Cntr=0.3,0.1

Type RM Length L Ch R = 1,500,0,0,0
BEGIN DESCRIPTION:
WOLF CREEK 1.0
END DESCRIPTION:
XS GIS Cut Line= 3
      2807955.69     10286753.12      2807865.08     10286517.76
      2807655.66     10286303.09
#Sta/Elev= 30
  4747.8 1251.11  4757.4 1248.65  4762.8 1250.22  4787.4 1245.94  4792.8 1248.75
  4812.1 1243.96  4817.4 1246.11  4839.2 1239.02  4842.1 1237.88  4847.4 1239.20
  4872.0 1231.48  4904.4 1227.99  4946.2 1222.53  4993.4 1218.44  4993.9 1217.94
  5006.2 1218.44  5009.9 1220.07  5031.2 1221.91  5045.3 1225.40  5071.2 1227.31
  5083.1 1228.99  5108.9 1235.98  5144.4 1240.00  5172.6 1240.93  5200.9 1247.39
  5236.2 1249.93  5250.4 1252.69  5257.5 1255.73  5262.7 1255.77  5299.9 1258.48
#Mann=9,-1,0
  4747.8    0.05       0  4839.2    0.12       0  4904.4    0.05       0
  4946.2    0.12       0  4993.4    0.07       0  5006.2    0.12       0
  5071.2    0.05       0  5083.1    0.12       0  5262.7    0.05       0
Bank Sta=4993.4,5006.2
Exp/Cntr=0.3,0.1

Chan Stop Cuts=-1